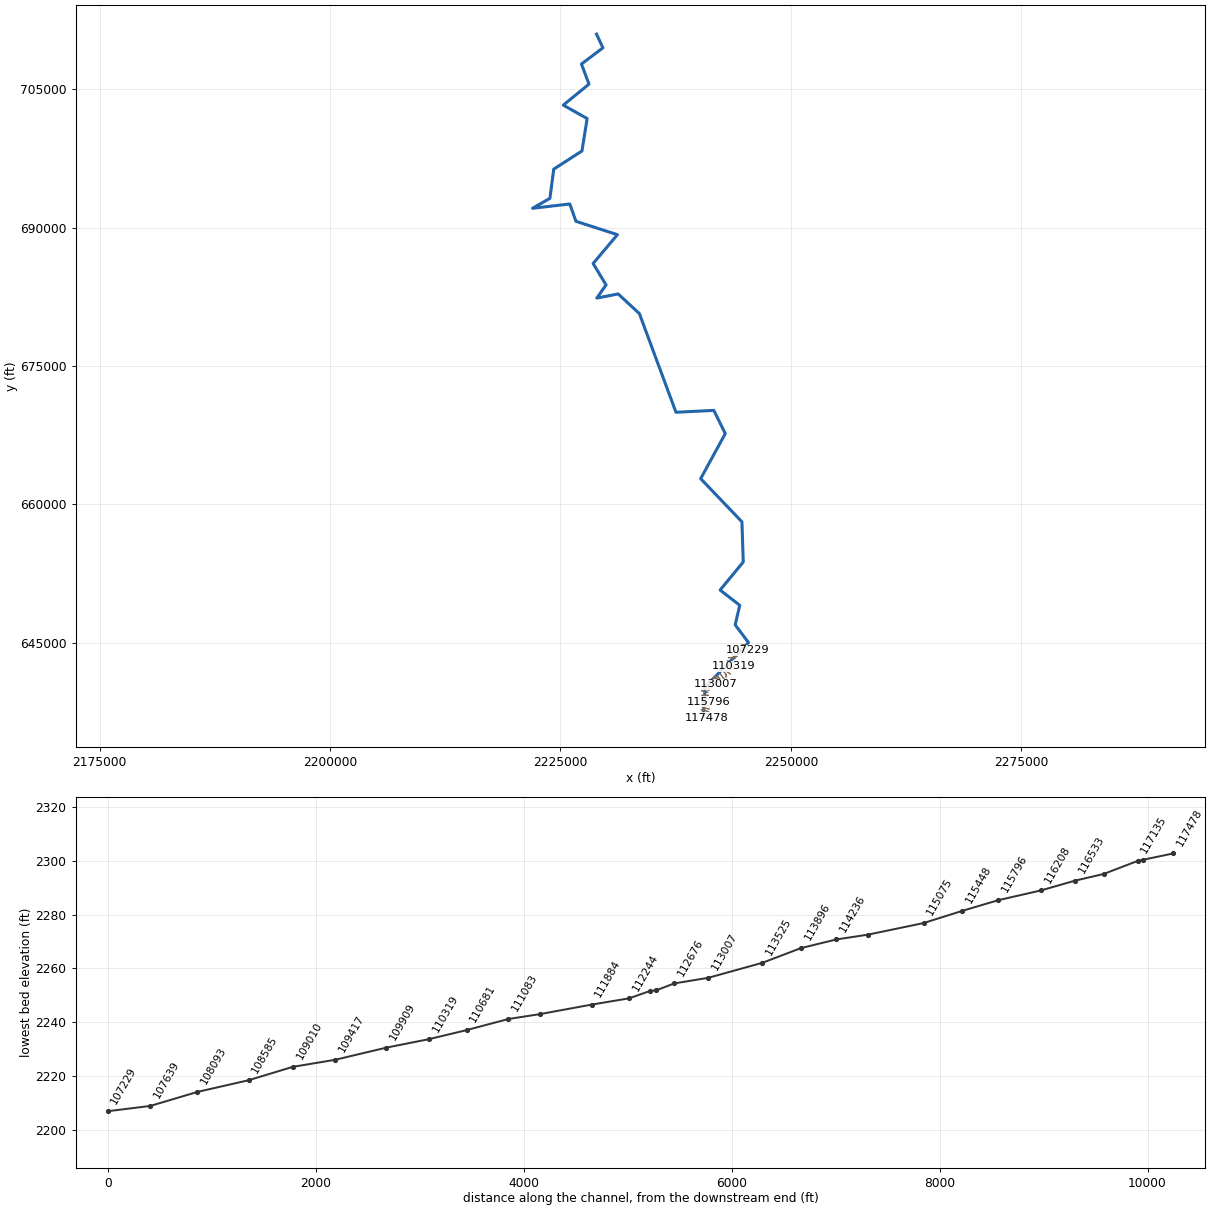
--- MIDFKRIV.prj (project) ---

Proj Title=MIDFKRIV
Current Plan=p01
Default Exp/Contr=0,0
English Units
Geom File=g01
Flow File=f01
Plan File=p01
BEGIN DESCRIPTION:
----------MODEL BY WOOD PLC 2022----------
AFH study
Randolph County, WV
HEC-RAS Version: RAS 6.2
Vertical Datum: NAVD88
Projection: NAD 1983 StatePlane West Virginia S FIPS 4702 (US Feet)
Terrain: 1-meter LIDAR (FEMA Region III 3DEP collected 2016-2018)
Land Use: 2019 NLCD
Hydrologic Method:
WV SIR2010-5033 regression equations
Additional Model Notes:
Normal depth out of county into Upshur and Barbour
END DESCRIPTION:
DSS Export Rating Curves= 0
DSS Export Rating Curve Sorted= 0
DSS Export Volume Flow Curves= 0
DXF OffsetX= 0
DXF OffsetY= 0
DXF ScaleX= 0
DXF ScaleY= 0

--- MIDFKRIV.p01 (plan) ---

Plan Title=Floodplain
Program Version=6.20
Short Identifier=Floodplain
Geom File=g01
Flow File=f01
Subcritical Flow
K Sum by GR= 0
Std Step Tol= 0.01
Critical Tol= 0.01
Num of Std Step Trials= 20
Max Error Tol= 0.3
Flow Tol Ratio= 0.001
Split Flow NTrial= 30
Split Flow Tol= 0.02
Split Flow Ratio= 0.02
Log Output Level= 0
Friction Slope Method= 1
Unsteady Friction Slope Method= 2
Unsteady Bridges Friction Slope Method= 1
Parabolic Critical Depth
Global Vel Dist= 0 , 0 , 0
Global Log Level= 0
CheckData=True
Encroach Param=-1 ,0,0, 0
Mapping Interval=1HOUR
Computation Time Step Use Courant=        0
Computation Time Step Use Time Series=    0
Computation Time Step Count To Double=0
Computation Time Step Max Doubling=0
Computation Time Step Max Halving=0
Computation Time Step Residence Courant=0
Run HTab= 0
Run UNet= 0
Run Sediment= 0
Run PostProcess= 0
Run WQNet= 0
Run RASMapper=-1
UNET Theta= 0
UNET Theta Warmup= 0
UNET ZTol= 0
UNET ZSATol= 0
UNET MxIter= 0
UNET Max Iter WO Improvement= 0
UNET MaxInSteps= 0
UNET DtIC= 0
UNET DtMin= 0
UNET MaxCRTS= 0
UNET WFStab= 0
UNET SFStab= 0
UNET WFX= 1
UNET SFX= 1
UNET Gravity=32.174
UNET 1D Methodology=Finite Difference
UNET DSS MLevel= 1
UNET Pardiso=0
UNET DZMax Abort= 0
UNET Use Existing IB Tables= 0
UNET Froude Reduction=False
UNET Froude Limit= 0
UNET Froude Power= 0
UNET D1 Cores= 0
UNET WindReference=Eulerian
UNET WindDragFormulation=Hsu (1988)
UNET D2 Coriolis=0
UNET D2 Cores= 0
UNET D2 Theta= 1
UNET D2 Theta Warmup= 1
UNET D2 Z Tol= 0.01
UNET D2 Volume Tol= 0.01
UNET D2 Max Iterations= 20
UNET D2 Equation= 0
UNET D2 RampUpFraction=0.1
UNET D2 TimeSlices= 1
UNET D2 Turbulence Formulation=Non-Conservative (original)
UNET D2 Eddy Viscosity=0.3
UNET D2 Transverse Eddy Viscosity=0.1
UNET D2 Smagorinsky Mixing=0
UNET D2 BCVolumeCheck=0
UNET D2 Cores=0
UNET D2 SolverType=PARDISO (Direct)
UNET D2 Minimum Iterations= 2147483647
UNET D2 Maximum Iterations= 2147483647
UNET D2 Restart Number= 10
UNET D2 Relaxation Coeff=1.3
UNET D2 SOR Precondition Iterations= 10
UNET D2 ILUT Maximum Fill= 8
UNET D2 ILUT Tolerance=1E-08
UNET D1D2 MaxIter= 0
UNET D1D2 ZTol=0.01
UNET D1D2 QTol=0.1
UNET D1D2 MinQTol=1
Write IC File= 0
Write IC File at Fixed DateTime=0
Write IC File at Sim End=0
Echo Input=False
Echo Parameters=False
Echo Output=False
Write Detailed= 0
HDF Write Warmup=0
HDF Write Time Slices=0
HDF Flush=0
HDF Compression= 1
HDF Chunk Size= 1
HDF Spatial Parts= 1
HDF Use Max Rows=0
HDF Fixed Rows= 1
Calibration Method= 0
Calibration Iterations= 20
Calibration Max Change=0.05
Calibration Tolerance=0.2
Calibration Maximum=1.5
Calibration Minimum=0.5
Calibration Optimization Method= 1
WQ AD Non Conservative
WQ ULTIMATE=-1
WQ Max Comp Step=1HOUR
WQ Output Interval=15MIN
WQ Output Selected Increments= 0
WQ Output face flow=0
WQ Output face velocity=0
WQ Output face area=0
WQ Output face dispersion=0
WQ Output cell volume=0
WQ Output cell surface area=0
WQ Output cell continuity=0
WQ Output cumulative cell continuity=0
WQ Output face conc=0
WQ Output face dconc_dx=0
WQ Output face courant=0
WQ Output face peclet=0
WQ Output face adv mass=0
WQ Output face disp mass=0
WQ Output cell mass=0
WQ Output cell source sink temp=0
WQ Output nsm pathways=0
WQ Output nsm derived pathways=0
WQ Create Restart=0
WQ Fixed Restart=0
WQ System Summary=0
WQ Write To DSS=0
Sorting and Armoring Iterations= 10
XS Update Threshold= 0.02
Bed Roughness Predictor= 0
Hydraulics Update Threshold= 0.02
Energy Slope Method= 1
Volume Change Method= 1
Sediment Retention Method= 0
Sediment TS Multiplier= 1
Warm Up Method= 0
XS Weighting Method= 0
Number of US Weighted Cross Sections= 1
Number of DS Weighted Cross Sections= 1
Upstream XS Weight=0
Main XS Weight=1
Downstream XS Weight=0
Number of DS XS's Weighted with US Boundary= 1
Upstream Boundary Weight= 1
Weight of XSs Associated with US Boundary= 0
Number of US XS's Weighted with DS Boundary= 1
Downstream Boundary Weight= 0.5
Weight of XSs Associated with DS Boundary= 0.5
Percentile Method= 0
Sediment Output Level= 3
Mass or Volume Output= 0
Output Increment Type= 1
Profile and TS Output Increment= 1
Transport Output Increment 1
XS Output Flag= 0
XS Output Increment= 10
Read HDF5 Sediment Hotstart= 0
Sediment Hotstart Type= 0
Write Gradation File= 0
Read Gradation Hotstart= 0
Write HDF5 File= 1
Write Binary Output= 1
Write DSS Sediment File= 0
DSS Sediment Output Type= 1
SV Curve= 0
Specific Gage Flag= 0
Subcell Erosion Methods= 0
Subcell Deposition Methods= 0
Advection Scheme= 1
Matrix Solver= 0
Implicit Weighting Factor= 1
Maximum Outer Loop Convergence Iterations= 5
Convergence Maximum Absolute= 0.001
Convergence RMSE= 0.0001
Grain Fractions Max Abs Error= 0.001
Max Subgrid Regions= 1
Max Subgrid Length Scale= 3.402823E+38
Initial Layer Thickness= 3.402823E+38
Min Layer Thickness= 3.402823E+38
Max Layer Thickness= 3.402823E+38
Number of Layers= 5

--- MIDFKRIV.f01 (steady flow) ---

Flow Title=Flow
Program Version=6.20
Number of Profiles= 1
Profile Names=P100yr
River Rch & RM=MIDFKRIV,Main            ,117478
    4040
River Rch & RM=MIDFKRIV,Main            ,107229
    4500
River Rch & RM=MIDFKRIV,Main            ,104488
    5140
River Rch & RM=MIDFKRIV,Main            ,94982
    6080
River Rch & RM=MIDFKRIV,Main            ,78541
    9960
River Rch & RM=MIDFKRIV,Main            ,51536
   11400
River Rch & RM=MIDFKRIV,Main            ,33492
   15700
Boundary for River Rch & Prof#=MIDFKRIV,Main            , 1
Up Type= 0
Dn Type= 3
Dn Slope=0.00018
DSS Import GetInterval= 0
DSS Import GetPeak= 0
DSS Import FillOption= 0

--- MIDFKRIV.g01 (geometry) ---

Geom Title=Geometry
Program Version=6.20

River Reach=MIDFKRIV        ,Main
Reach XY= 30
2240494.68799998 637087.630000012240703.97800003640187.983999997
2245397.55300005645008.9080000072243950.64111586646918.233073771
2244445.79900001649047.7000000032242319.71309991650700.222205982
2244828.21599999653744.0650000132244683.15500002658099.604000002
2240209.93100004662782.8230000142242876.45100002667666.983999997
2241638.65300003670188.687999994     2237528.961      669983.772
2233561.61200002680683.3250000032231258.65300001682820.060000002
2228937.87300003682369.9539999962229947.46600004683792.649000004
2228542.71799998686123.1710000192231178.60363483689248.925049737
2226679.72717699690698.0032331942226010.35964608 692577.89793551
     2221973.971692109.6550000162223854.35600001693187.287000015
     2224270.508696355.1110000162227331.58000004698326.329000011
2227893.31100003701845.6990000012225303.64100003703297.709000021
2228096.80199999705580.7709999982227272.90500002707756.734000012
     2229604.233709513.5100000052228909.19646253711008.433439114

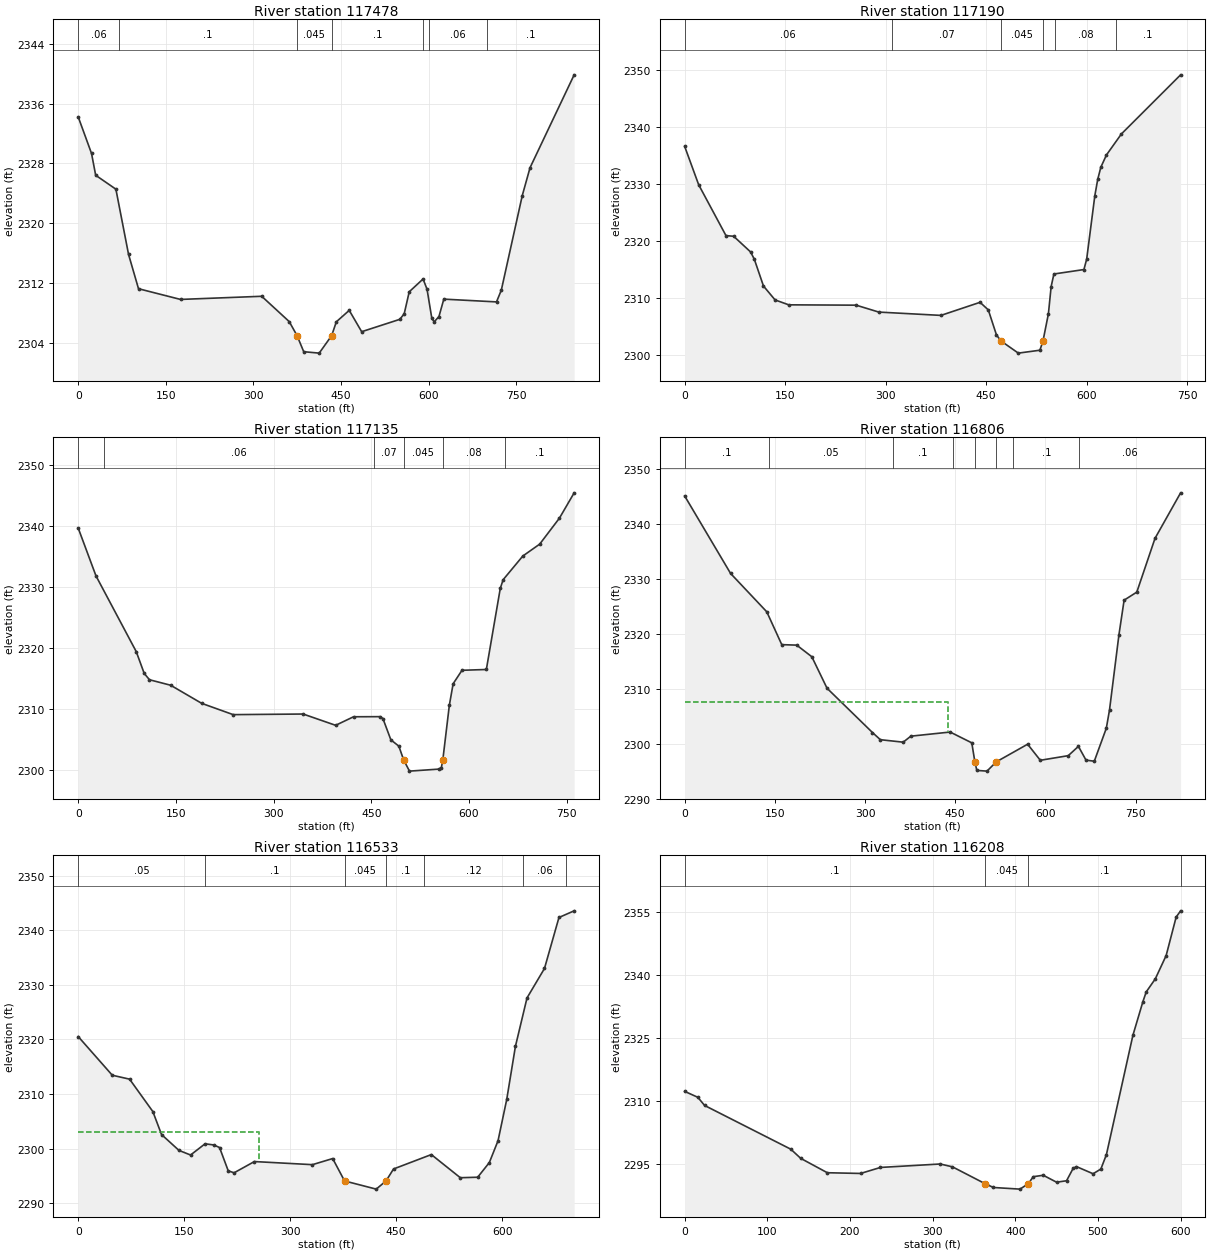
Type RM Length L Ch R = 1 ,117478  ,288.2,288.2,288.2
XS GIS Cut Line= 4
2240258.64113314637337.6025822582240459.20992929 637268.52283901
2240593.52684935636914.9760034592240845.95678648 636858.80540227
#Sta/Elev= 30
       0 2334.21    22.8 2329.33    29.9 2326.42    64.5 2324.56    86.2 2315.84
   103.2 2311.27   175.1 2309.84   314.1 2310.26   361.2 2306.88  374.562305.011
     386 2302.86   412.5 2302.67  433.862305.011   441.8 2306.85   463.9 2308.38
   485.2 2305.53   550.4 2307.18     558 2307.92   566.6 2310.86   590.3 2312.57
   597.1  2311.2   605.3  2307.3   609.4 2306.85   617.5 2307.56   625.8 2309.88
     716 2309.51   724.2 2311.07   760.1 2323.71   773.4 2327.43   848.9 2339.83
#Mann= 7 ,-1,0
       0     .06       0      70      .1       0  374.56    .045       0
  433.86      .1       0  590.33     .05       0  600.33     .06       0
  700.33      .1       0
Bank Sta=374.56,433.86
XS Rating Curve= 0 ,0
Exp/Cntr(USF)=0,0
Exp/Cntr=0.3,0.1

Type RM Length L Ch R = 1 ,117190  ,55.2,55.2,55.2
XS GIS Cut Line= 5
  2240271.629403637378.1377967562240555.70196956637324.102254205
2240645.24658293637271.6105842982240861.38875314637228.382150257
 2240978.7230741637180.522098283
#Sta/Elev= 30
       0 2336.56    20.9 2329.84    61.6 2320.94    73.1 2320.82    98.3 2318.08
   103.9 2316.81   117.6  2312.1   134.9 2309.67   155.3 2308.81   255.9 2308.75
   289.7 2307.54   382.4 2306.96   440.8 2309.25   453.1 2307.92   465.3 2303.53
   472.22302.469   497.9 2300.35   530.1 2300.86   534.72302.468   542.8 2307.24
   546.9 2312.02     551 2314.21   595.8 2314.99   599.9 2316.81   612.1 2327.94
   616.4 2330.79     621  2332.9   629.4 2335.06   651.7 2338.74   740.1  2349.1
#Mann= 6 ,-1,0
       0     .06       0  309.17     .07       0   472.2    .045       0
   534.7     .07       0  552.96     .08       0  643.38      .1       0
Bank Sta=472.2,534.7
XS Rating Curve= 0 ,0
Exp/Cntr(USF)=0,0
Exp/Cntr=0.3,0.1

Type RM Length L Ch R = 1 ,117135  ,328.8,328.8,328.8
XS GIS Cut Line= 5
2240272.40133933637429.085594019 2240578.0881229637375.050051468
2240667.63273627637322.5583815612240883.77490648 637279.32994752
2241001.10922745637231.469895546
#Sta/Elev= 30
       0 2339.73    27.3 2331.89    89.1 2319.48   101.3 2315.91   109.4 2314.87
   141.9 2313.97   189.6    2311   237.9 2309.15   345.3 2309.25   395.2  2307.4
   422.7  2308.8   463.7 2308.82   467.8 2308.51     480 2305.02   492.3 2303.98
  499.612301.725   508.6 2299.89   553.5 2300.22   557.5 2300.44  559.762301.724
   569.8  2310.7   575.6 2314.21   589.2 2316.42   626.6 2316.55     648 2329.85
   652.4 2331.27   682.6 2335.15   708.5  2337.1   738.8 2341.36   761.4 2345.51
#Mann= 6 ,-1,0
       0      .1       0      40     .06       0  454.22     .07       0
  499.61    .045       0  559.76     .08       0  654.64      .1       0
Bank Sta=499.61,559.76
XS Rating Curve= 0 ,0
Exp/Cntr(USF)=0,0
Exp/Cntr=0.3,0.1

Type RM Length L Ch R = 1 ,116806  ,273.2,273.2,273.2
XS GIS Cut Line= 3
 2240271.8644317637724.118984577 2240428.3324764 637714.70203322
2241061.23374643637500.127496614
#Sta/Elev= 30
       0 2345.02    76.4 2330.94   136.6 2323.97   161.5 2318.01   186.4 2317.92
   211.5 2315.81   236.8 2310.09   312.4 2302.04   325.5 2300.74   363.5 2300.29
   376.2 2301.38   441.6 2302.13   477.6 2300.17   482.7 2296.74     486 2295.16
   502.9 2295.03   518.3 2296.71   570.5 2299.92   591.6    2297   638.1 2297.84
     655 2299.53   667.6 2297.03   681.4 2296.83   701.4 2302.82   706.7 2306.13
   722.4  2319.8     731 2326.09   752.1 2327.55   782.4 2337.32     825 2345.59
#Mann= 8 ,-1,0
       0      .1       0     140     .05       0  346.75      .1       0
  446.75     .05       0   482.7    .045       0   518.3     .05       0
  546.75      .1       0  656.75     .06       0
#XS Ineff= 2 , 0
          438.27 2307.66
Permanent Ineff=
       F       F
Bank Sta=482.7,518.3
XS Rating Curve= 0 ,0
Exp/Cntr(USF)=0,0
Exp/Cntr=0.3,0.1

Type RM Length L Ch R = 1 ,116533  ,325,325,325
XS GIS Cut Line= 2
2240425.24473111637949.3706751572241109.18031255637791.895665436
#Sta/Elev= 30
       0 2320.52    48.2 2313.44    72.7 2312.72   105.6 2306.79   117.9 2302.58
   142.6 2299.67     159 2298.83   179.5 2300.88   191.8 2300.67     200  2300.2
   212.3 2295.93   220.6 2295.57   249.3 2297.63   331.4 2297.06   360.1 2298.18
   376.9 2294.08   421.7 2292.58   435.6 2294.08   446.2 2296.27   499.7 2298.91
   540.7 2294.67   565.3 2294.76   581.8 2297.45   594.1 2301.45   606.4 2309.01
   618.7 2318.73   635.1  2327.6   659.8 2332.99   680.3 2342.33   701.8 2343.55
#Mann= 7 ,-1,0
       0     .05       0     180      .1       0   376.9    .045       0
   435.6      .1       0     490     .12       0     630     .06       0
     690      .1       0
#XS Ineff= 2 , 0
          255.31 2302.96
Permanent Ineff=
       F       F
Bank Sta=376.9,435.6
XS Rating Curve= 0 ,0
Exp/Cntr(USF)=0,0
Exp/Cntr=0.3,0.1

Type RM Length L Ch R = 1 ,116208  ,412,412,412
XS GIS Cut Line= 2
2240500.39369626638211.3124173192241097.56566908638153.126208621
#Sta/Elev= 30
       0 2312.24    15.9 2310.83    24.1 2308.89   128.4 2298.48   140.4  2296.3
   172.6 2292.88   212.8 2292.71   236.9 2294.14   309.2 2294.96     324 2294.28
  363.232290.297   373.5 2289.37   405.7 2288.98   415.6 2290.26   421.8 2291.94
   433.8 2292.28   449.9 2290.63     462 2290.97     470 2293.93     474 2294.34
   494.1 2292.64   503.5 2293.76   510.2 2297.17   542.3  2325.6   554.4 2333.61
   558.4 2335.91   569.4 2339.02   582.5 2344.56   594.6 2353.72     600  2355.2
#Mann= 4 ,-1,0
       0      .1       0  363.23    .045       0   415.6      .1       0
     600     .06       0
Bank Sta=363.23,415.6
XS Rating Curve= 0 ,0
Exp/Cntr(USF)=0,0
Exp/Cntr=0.3,0.1

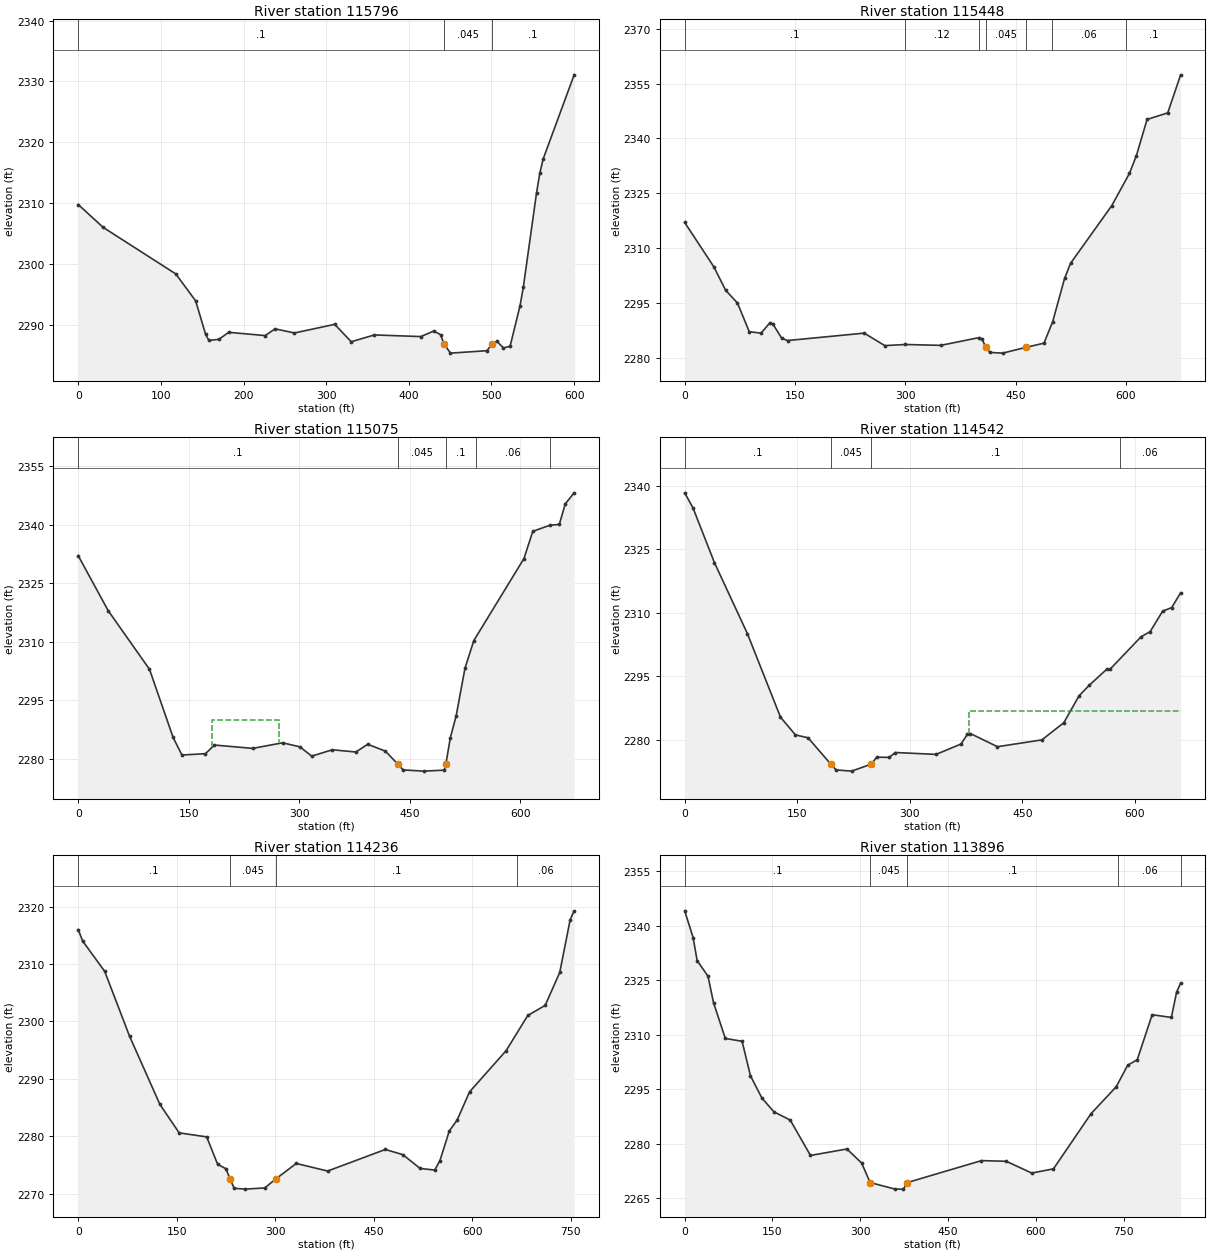
Type RM Length L Ch R = 1 ,115796  ,347.7,347.7,347.7
XS GIS Cut Line= 2
2240434.23791047638553.7282702112241033.59408992638581.516220028
#Sta/Elev= 30
       0 2309.77      30 2306.03   118.1 2298.36   142.1 2293.93   154.1 2288.45
   158.1 2287.44   170.1 2287.61   182.1 2288.77   226.2 2288.23   238.2 2289.34
   261.6 2288.66   310.3 2290.08   330.3 2287.22   358.3 2288.34   414.4 2288.07
   430.4 2288.98   438.4 2288.38   442.4 2286.88   450.4 2285.35   494.5 2285.75
   500.92286.884   506.5 2287.28   514.5 2286.21   522.5 2286.47   534.5 2293.12
   538.5 2296.17   554.5  2311.7   558.5 2314.95   562.5 2317.25     600 2331.08
#Mann= 3 ,-1,0
       0      .1       0   442.4    .045       0   500.9      .1       0
Bank Sta=442.4,500.9
XS Rating Curve= 0 ,0
Exp/Cntr(USF)=0,0
Exp/Cntr=0.3,0.1

Type RM Length L Ch R = 1 ,115448  ,373.4,373.4,373.4
XS GIS Cut Line= 2
2240400.54276881638891.1329881972241073.67124173638931.273676949
#Sta/Elev= 30
       0 2317.07    39.7 2304.93    55.7 2298.54    71.8 2295.06    87.8 2287.23
   103.8 2286.84   115.8 2289.63   119.8 2289.38   131.9 2285.45   139.9 2284.82
   244.1 2286.84   272.1 2283.43     300 2283.74   348.2  2283.5   400.3 2285.62
   404.3 2285.28  409.312282.983     415 2281.57   432.4 2281.38  464.562282.982
   488.5  2284.1   500.3 2289.93   516.5 2301.76   524.6 2305.89   580.7 2321.66
   604.7 2330.45   614.2 2335.32   628.7  2345.2   656.8 2346.99   674.3 2357.38
#Mann= 7 ,-1,0
       0      .1       0     300     .12       0     400      .1       0
  409.31    .045       0  464.56      .1       0     500     .06       0
     600      .1       0
Bank Sta=409.31,464.56
XS Rating Curve= 0 ,0
Exp/Cntr(USF)=0,0
Exp/Cntr=0.3,0.1

Type RM Length L Ch R = 1 ,115075  ,532.6,532.6,532.6
XS GIS Cut Line= 2
2240355.48725271 639274.79608874 2241028.2743434639289.012710022
#Sta/Elev= 30
       0 2332.07    40.7 2317.97    96.7 2302.95   128.7 2285.51   140.7 2280.97
   172.7 2281.31   184.7 2283.53   236.7 2282.67   277.3  2284.1   300.7 2283.07
   316.8 2280.69   344.8 2282.31   376.8 2281.74   392.8 2283.73   416.8 2281.96
  433.372278.687   440.8 2277.15   468.8 2276.84   496.7 2277.09  498.882278.688
   504.8  2285.3   512.8 2291.01   524.8 2303.24   536.8 2310.32   604.8 2331.35
   616.8 2338.33     640 2339.87   652.8  2340.1   660.8 2345.35   672.9 2348.19
#Mann= 5 ,-1,0
       0      .1       0  433.37    .045       0  498.88      .1       0
     540     .06       0     640      .1       0
#XS Ineff= 1 ,-1
  181.85  272.352289.985
Permanent Ineff=
       F
Bank Sta=433.37,498.88
XS Rating Curve= 0 ,0
Exp/Cntr(USF)=0,0
Exp/Cntr=0.3,0.1

Type RM Length L Ch R = 1 ,114542  ,305.6,305.6,305.6
XS GIS Cut Line= 4
2240336.54906455639749.033517339 2240483.9118916639743.350687865
2240812.75676484639649.1744565612240979.66702881639609.776546669
#Sta/Elev= 30
       0  2338.3    11.1 2334.73    39.7 2321.79    83.7    2305   127.7 2285.31
   147.7 2281.11   164.4 2280.44   194.7 2274.23   201.8 2272.84   222.6 2272.56
  248.632274.219   255.9 2275.85   272.6 2275.81   280.9 2276.96     335 2276.51
   368.3 2278.96   376.6 2281.23   380.8 2281.44   416.9 2278.33   476.1 2279.94
   505.4 2284.01   525.6 2290.35   538.9 2292.79   562.9 2296.69     567 2296.64
   608.1 2304.27   620.5 2305.54   636.9 2310.32   649.2 2311.21     661 2314.69
#Mann= 4 ,-1,0
       0      .1       0   194.7    .045       0  248.63      .1       0
  579.54     .06       0
#XS Ineff= 2 , 0
                          379.57         2286.88
Permanent Ineff=
       F       F
Bank Sta=194.7,248.63
XS Rating Curve= 0 ,0
Exp/Cntr(USF)=0,0
Exp/Cntr=0.3,0.1

Type RM Length L Ch R = 1 ,114236  ,340.4,340.4,340.4
XS GIS Cut Line= 4
2240377.82594964639999.0491558752240533.31581622640049.037471442
2240825.10774599639959.4928580712241084.01588101639836.897615944
#Sta/Elev= 30
       0 2315.99     6.7    2314    40.3 2308.71    78.1 2297.43   124.3 2285.54
   153.7 2280.57   195.6 2279.87   212.3 2275.08   224.9 2274.32  231.132272.553
   237.4 2270.92   254.2 2270.77     284 2270.98  300.942272.554     332 2275.24
   379.7 2273.92   467.6 2277.68   494.1 2276.78   520.6 2274.37   542.8 2274.09
   550.7 2275.75   564.9  2280.9   576.8 2282.78   595.7  2287.7   651.5  2294.9
   684.4 2301.02   710.9 2302.78   733.1 2308.53   748.9 2317.69     755 2319.25
#Mann= 4 ,-1,0
       0      .1       0  231.13    .045       0  300.94      .1       0
  668.55     .06       0
Bank Sta=231.13,300.94
XS Rating Curve= 0 ,0
Exp/Cntr(USF)=0,0
Exp/Cntr=0.3,0.1

Type RM Length L Ch R = 1 ,113896  ,370.5,370.5,370.5
XS GIS Cut Line= 4
2240639.84302867640561.6031893582240801.94965633640333.110037998
2240911.56461408640107.7046319262241194.43406094639966.215544883
#Sta/Elev= 30
       0 2344.16    14.4 2336.81    21.3 2330.45    39.8 2326.19    49.3 2318.86
    69.4 2309.03    98.1 2308.25   112.4 2298.73   131.9 2292.64   152.3 2288.85
   180.3 2286.56   214.9 2276.83   277.1 2278.61   302.3 2274.73  316.762269.367
   359.6 2267.56   373.5 2267.56  380.222269.367   506.9 2275.41   549.4 2275.22
   592.8 2271.98   629.9 2273.14   694.1 2288.33   737.2 2295.76   756.7 2301.67
     773 2303.17   798.5 2315.56   831.3 2314.82   840.2 2321.76   847.1 2324.25
#Mann= 5 ,-1,0
       0      .1       0  316.76    .045       0  380.22      .1       0
   740.8     .06       0  847.08      .1       0
Bank Sta=316.76,380.22
XS Rating Curve= 0 ,0
Exp/Cntr(USF)=0,0
Exp/Cntr=0.3,0.1

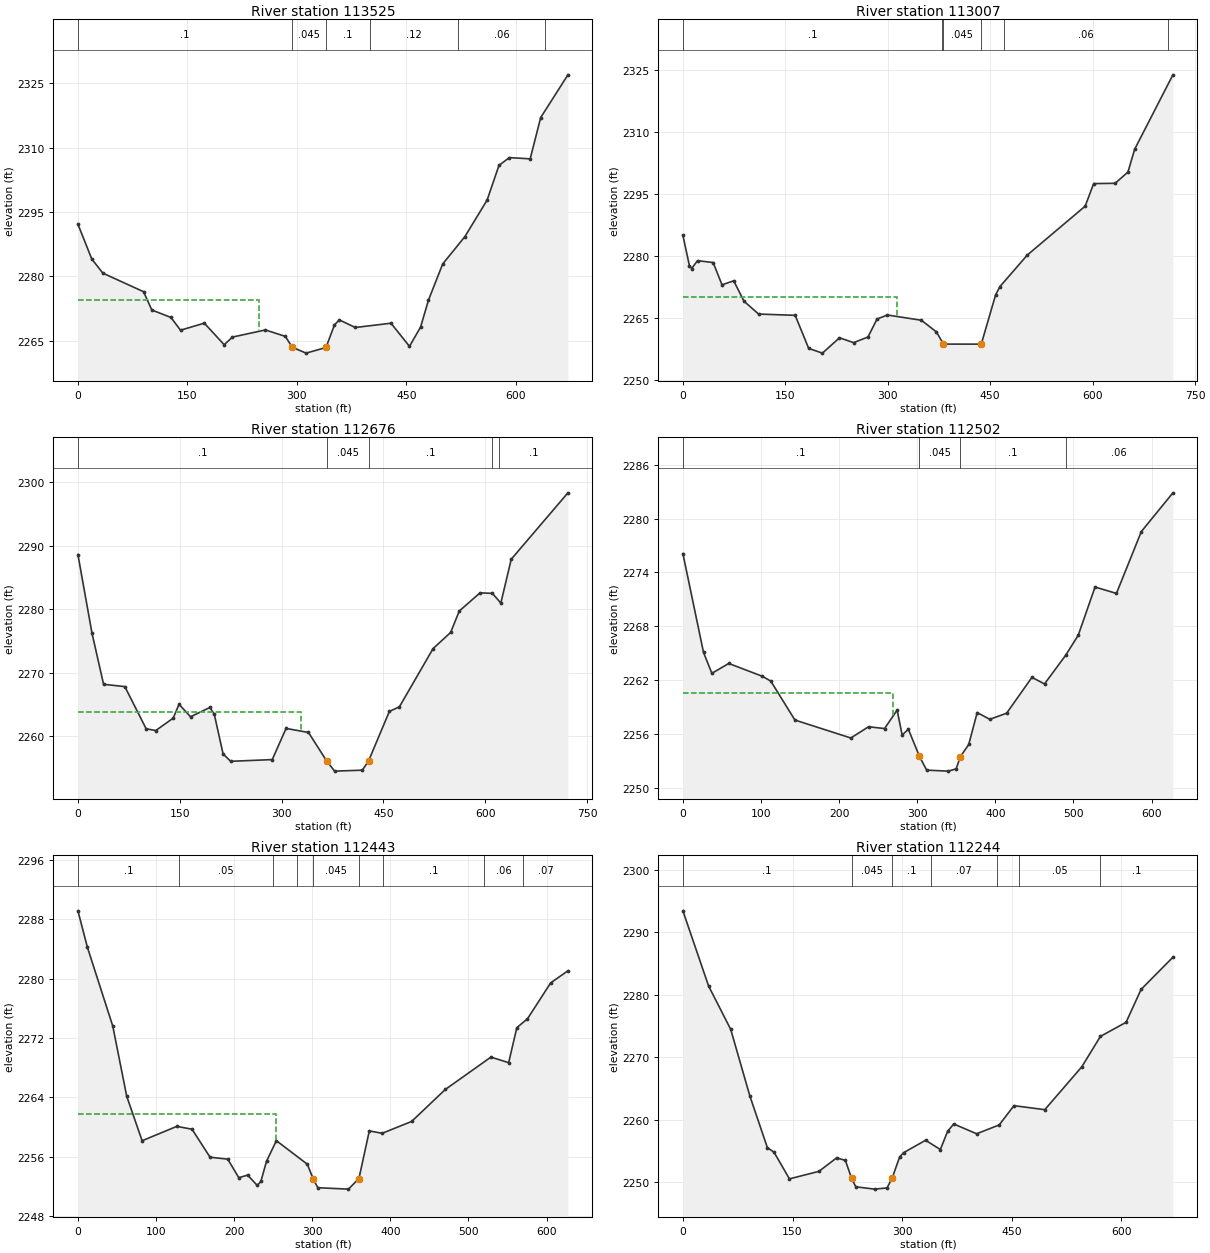
Type RM Length L Ch R = 1 ,113525  ,519,519,519
XS GIS Cut Line= 2
2240974.20245874640676.2241723732241385.08573611640145.618153304
#Sta/Elev= 30
       0 2292.15      19 2284.04    34.2 2280.74    89.9 2276.43   101.2 2272.17
   127.4 2270.43   140.5 2267.46   173.1  2269.1   200.3 2264.08   211.7 2265.86
   256.8 2267.52   284.1 2266.02  293.572263.479   312.5 2262.12  339.732263.433
   351.4 2268.71     358 2269.86   379.9 2268.09   428.8 2269.09   454.1 2263.69
   469.3 2268.19   480.1 2274.46   499.6 2282.89     530 2289.26   560.4 2297.76
   576.7 2305.86   590.9 2307.66   619.4 2307.37   633.8 2316.99   671.1 2326.94
#Mann= 6 ,-1,0
       0      .1       0  293.57    .045       0  339.73      .1       0
     400     .12       0     520     .06       0     640      .1       0
#XS Ineff= 2 , 0
          247.36 2274.41
Permanent Ineff=
       F       F
Bank Sta=293.57,339.73
XS Rating Curve= 0 ,0
Exp/Cntr(USF)=0,0
Exp/Cntr=0.3,0.1

Type RM Length L Ch R = 1 ,113007  ,330.7,330.7,330.7
XS GIS Cut Line= 2
2241357.82277136641036.7815983482241787.63308912640462.238536709
#Sta/Elev= 30
       0    2285     9.5  2277.7    12.8 2276.98    21.4 2278.87    44.3 2278.42
    57.3 2273.04    74.4 2274.01    89.4 2269.11   110.8 2265.99   164.4 2265.68
   184.2  2257.7   204.3 2256.56   229.3 2260.26     250 2259.09     271 2260.45
   284.2 2264.76   299.2 2265.77   349.2 2264.49   371.2 2261.69   381.5 2258.74
  436.872258.728     458 2270.67   464.3 2272.63   504.3 2280.23     589 2292.02
   601.5 2297.47   632.9 2297.54   651.7 2300.26   661.5 2305.76   717.5 2323.72
#Mann= 6 ,-1,0
       0      .1       0     380     .12       0   381.5    .045       0
  436.87     .12       0     470     .06       0     710      .1       0
#XS Ineff= 2 , 0
           313.3 2270.05
Permanent Ineff=
       F       F
Bank Sta=381.5,436.87
XS Rating Curve= 0 ,0
Exp/Cntr(USF)=0,0
Exp/Cntr=0.3,0.1

Type RM Length L Ch R = 1 ,112676  ,173.3,173.3,173.3
XS GIS Cut Line= 2
2241599.49592526 641245.613817232242047.46181244640679.708919264
#Sta/Elev= 30
       0 2288.63    20.7 2276.24    37.8 2268.15    69.1 2267.79   100.5 2261.13
   114.7 2260.86   140.3 2262.81   148.9 2264.99   165.9 2263.03   194.4  2264.5
   200.9  2263.4   213.8 2257.17     225    2256   286.2 2256.27   306.6 2261.19
   339.6 2260.55  366.532256.029   378.1 2254.45   418.9  2254.6   428.1 2256.07
   458.7 2263.87   473.5  2264.6   523.1 2273.79   548.9 2276.33   561.7 2279.72
   592.3 2282.59   610.5  2282.5   622.9 2280.97   638.2 2287.89   721.7 2298.37
#Mann= 5 ,-1,0
       0      .1       0  366.53    .045       0   428.1      .1       0
     610     .06       0     620      .1       0
#XS Ineff= 2 , 0
          327.87 2263.85
Permanent Ineff=
       F       F
Bank Sta=366.53,428.1
XS Rating Curve= 0 ,0
Exp/Cntr(USF)=0,0
Exp/Cntr=0.3,0.1

Type RM Length L Ch R = 1 ,112502  ,59.5,59.5,59.5
XS GIS Cut Line= 2
 2241748.0084635641300.7394722332242168.61207036640835.247361161
#Sta/Elev= 30
       0  2276.1    26.4  2265.1    37.1 2262.77    58.7 2263.87   101.8 2262.44
   112.6  2261.9   143.4 2257.57     215 2255.57   237.7 2256.82   258.2 2256.62
   274.3 2258.68   280.7  2255.9   288.7 2256.54   302.8 2253.54   312.1 2251.99
   339.7 2251.88   349.8 2252.13  355.422253.507     366 2254.85   376.8  2258.4
     393 2257.65   414.5 2258.33   446.9 2262.32     463 2261.59     490 2264.77
   506.2 2267.01   527.7 2272.38   555.1 2271.67     587 2278.56   627.4 2282.87
#Mann= 4 ,-1,0
       0      .1       0   302.8    .045       0  355.42      .1       0
     490     .06       0
#XS Ineff= 2 , 0
          269.03 2260.62
Permanent Ineff=
       F       F
Bank Sta=302.8,355.42
XS Rating Curve= 0 ,0
Exp/Cntr(USF)=0,0
Exp/Cntr=0.3,0.1

Type RM Length L Ch R = 1 ,112443  ,199.1,199.1,199.1
XS GIS Cut Line= 2
2241794.25194497641338.1920051752242214.85555183640872.699894102
#Sta/Elev= 30
       0 2289.15    12.1 2284.25    44.6 2273.63    62.5 2264.16    82.2 2258.17
   126.7 2260.11   146.1 2259.72   169.2 2255.95   191.8 2255.69     206 2253.19
   217.3 2253.54   229.6 2252.15   234.3  2252.7   241.5 2255.41   254.1 2258.18
   293.8    2255   301.2 2253.04   307.2 2251.84   346.4 2251.65  359.83 2253.08
   373.1  2259.5   389.5 2259.17   427.3 2260.77   470.4 2265.08   528.8 2269.44
   551.5 2268.69     562 2273.41   575.6  2274.6   605.3 2279.44   627.4 2281.07
#Mann= 9 ,-1,0
       0      .1       0     130     .05       0     250      .1       0
     280     .05       0   301.2    .045       0  359.83     .05       0
     390      .1       0     520     .06       0     570     .07       0
#XS Ineff= 2 , 0
          253.73 2261.82
Permanent Ineff=
       F       F
Bank Sta=301.2,359.83
XS Rating Curve= 0 ,0
Exp/Cntr(USF)=0,0
Exp/Cntr=0.3,0.1

Type RM Length L Ch R = 1 ,112244  ,360.1,360.1,360.1
XS GIS Cut Line= 3
2242016.48980971 641421.051557842242308.76935719641038.659836455
2242353.86888269 640854.95873011
#Sta/Elev= 30
       0 2293.42    35.1 2281.42    65.4 2274.48    91.7  2263.8   115.6 2255.57
   124.6 2254.86   145.8 2250.58   186.1 2251.78   210.3 2253.93   222.3 2253.54
   230.8 2250.68   236.6 2249.31   262.2 2248.94   279.3 2249.13  286.23 2250.67
   296.5 2254.05   301.9 2254.76   332.1 2256.75   352.3 2255.27   362.3  2258.2
   370.6 2259.35     402 2257.79   432.8  2259.2     453 2262.28   495.2 2261.64
   545.9  2268.5   571.3 2273.35   606.4  2275.6     627 2280.87   670.5    2286
#Mann= 7 ,-1,0
       0      .1       0   230.8    .045       0  286.23      .1       0
     340     .07       0     430     .06       0     460     .05       0
   571.3      .1       0
Bank Sta=230.8,286.23
XS Rating Curve= 0 ,0
Exp/Cntr(USF)=0,0
Exp/Cntr=0.3,0.1

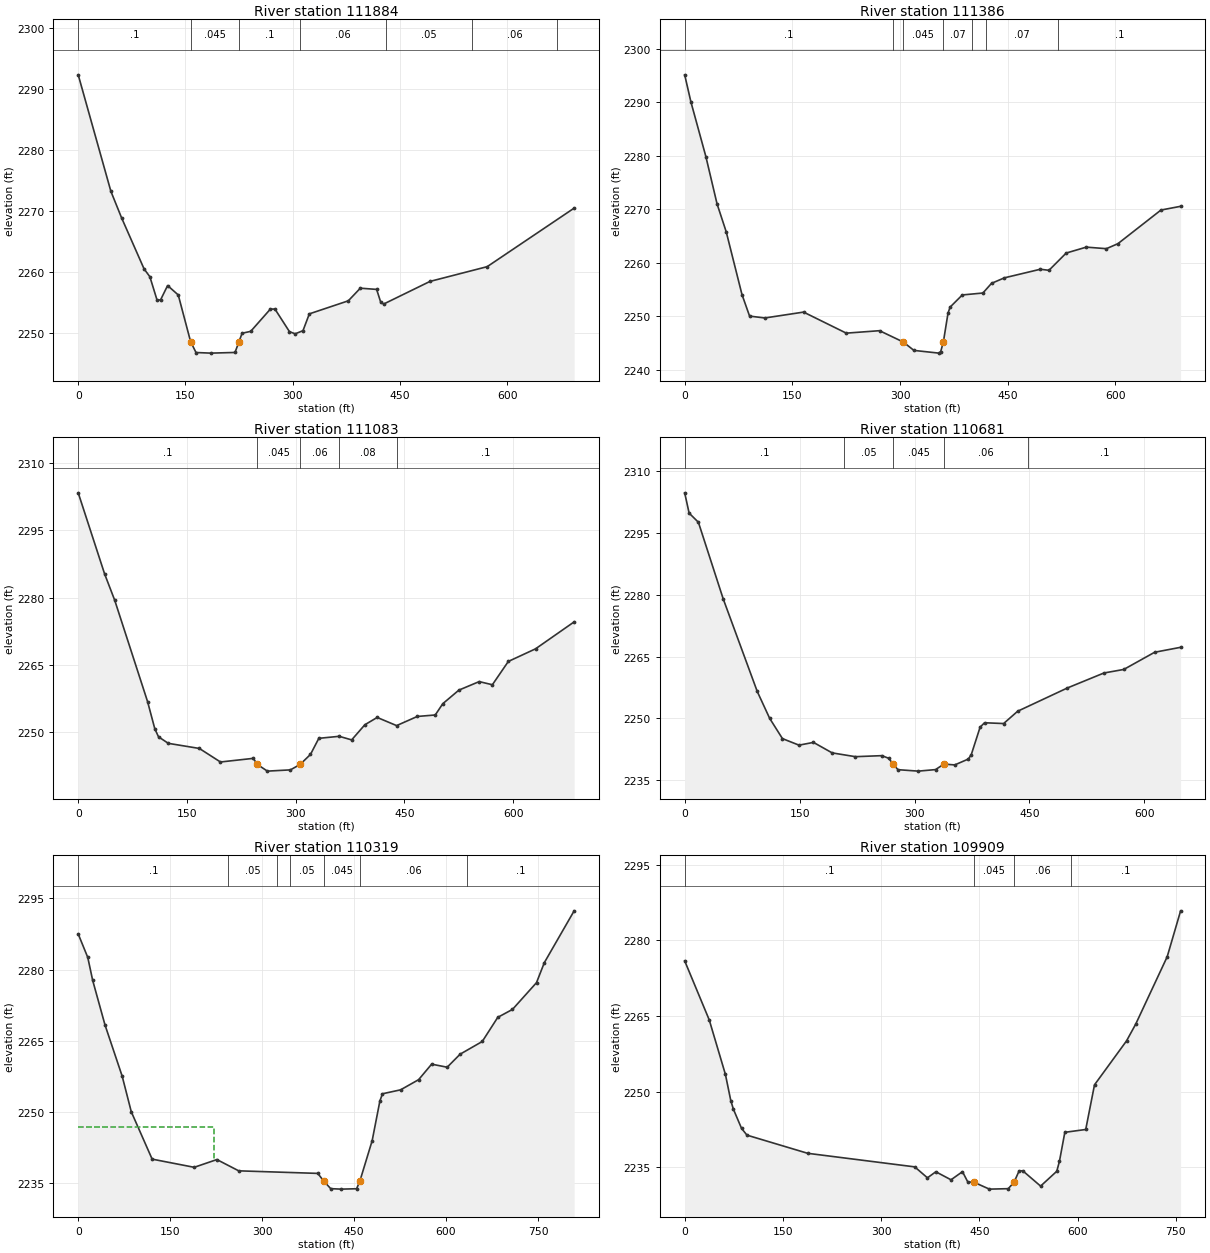
Type RM Length L Ch R = 1 ,111884  ,497.9,497.9,497.9
XS GIS Cut Line= 2
2242341.83150608641594.0996819462242751.12105155 641034.28238162
#Sta/Elev= 30
       0 2292.26    45.7 2273.15    60.6 2268.82    92.1 2260.43   100.2 2259.15
   110.2 2255.34   115.1 2255.34     125  2257.7   139.9 2256.16  157.162248.505
   164.7 2246.72   185.5 2246.62   219.2 2246.73  224.952248.503   229.1 2249.88
   241.2 2250.19   268.7 2253.84   275.1 2253.85   295.4 2250.14   303.4 2249.79
   314.3  2250.3   323.2 2253.06   377.7  2255.2   394.5 2257.27   417.3 2257.07
   423.1 2254.94   427.3 2254.68   491.9 2258.38   571.9  2260.8   693.5  2270.4
#Mann= 7 ,-1,0
       0      .1       0  157.16    .045       0  224.95      .1       0
     310     .06       0     430     .05       0     550     .06       0
     670     .07       0
Bank Sta=157.16,224.95
XS Rating Curve= 0 ,0
Exp/Cntr(USF)=0,0
Exp/Cntr=0.3,0.1

Type RM Length L Ch R = 1 ,111386  ,303.2,303.2,303.2
XS GIS Cut Line= 3
2242702.41345783641861.1116852662242966.45910368641560.488790237
2242965.76625175641269.769254637
#Sta/Elev= 30
       0 2295.17     8.7 2290.09    29.5 2279.88    45.1 2271.01    57.9 2265.77
    79.8 2254.05    90.4 2250.01   111.7 2249.66   165.6 2250.76   225.1 2246.82
   271.4 2247.28   304.5 2245.16   319.3 2243.59   354.2 2243.08   356.6 2243.36
   360.3 2245.14   366.8 2250.56   369.7 2251.69   386.7 2253.97   415.4 2254.33
   427.4 2256.14   445.3 2257.17   495.4 2258.78   507.4 2258.58   531.4 2261.81
   559.4 2262.92   587.4 2262.63   603.4 2263.56   663.4 2269.86   690.8 2270.56
#Mann= 7 ,-1,0
       0      .1       0     290     .07       0   304.5    .045       0
   360.3     .07       0     400     .06       0  420.12     .07       0
  520.12      .1       0
Bank Sta=304.5,360.3
XS Rating Curve= 0 ,0
Exp/Cntr(USF)=0,0
Exp/Cntr=0.3,0.1

Type RM Length L Ch R = 1 ,111083  ,401.9,401.9,401.9
XS GIS Cut Line= 2
2242876.04679806642007.2178166282243420.35766111641592.910115768
#Sta/Elev= 30
       0 2303.39    36.4  2285.3    50.4 2279.39    95.7 2256.78   105.7  2250.7
   110.8 2248.93   124.3 2247.48   167.1 2246.34   196.2 2243.32   241.5 2244.13
     247 2242.79   260.9 2241.28   292.7 2241.56  306.042242.762   320.4 2245.01
   331.9  2248.6     360 2249.05   377.2 2248.25   395.4 2251.63   412.4 2253.26
   439.2 2251.44   467.7 2253.48   492.5 2253.81   502.9 2256.33   525.1 2259.36
   553.1 2261.26   571.3 2260.56   593.3 2265.76   630.8 2268.57   684.1 2274.59
#Mann= 5 ,-1,0
       0      .1       0     247    .045       0  306.04     .06       0
     360     .08       0     440      .1       0
Bank Sta=247,306.04
XS Rating Curve= 0 ,0
Exp/Cntr(USF)=0,0
Exp/Cntr=0.3,0.1

Type RM Length L Ch R = 1 ,110681  ,361.4,361.4,361.4
XS GIS Cut Line= 3
2242966.45910368642278.3895698492243083.79342464642261.406970761
2243572.82251355642060.282745333
#Sta/Elev= 30
       0 2304.77     5.8 2299.84    17.9 2297.62    50.2 2279.05    94.7 2256.52
   110.9 2249.99   127.6 2245.06   149.2 2243.47   168.1 2244.14   192.5 2241.59
   222.8 2240.67   257.4 2240.92   266.4 2240.27  271.862238.894   278.4 2237.51
   304.9 2237.16   327.4 2237.53  338.382238.865   352.5 2238.67   370.3  2240.1
   374.1 2241.19   385.6 2247.84   391.4 2248.91   416.3 2248.72   434.6 2251.71
   499.6 2257.37   547.2    2261   573.1 2261.86   613.4 2266.04   647.3 2267.24
#Mann= 5 ,-1,0
       0      .1       0  208.56     .05       0  271.86    .045       0
  338.38     .06       0  448.56      .1       0
Bank Sta=271.86,338.38
XS Rating Curve= 0 ,0
Exp/Cntr(USF)=0,0
Exp/Cntr=0.3,0.1

Type RM Length L Ch R = 1 ,110319  ,410,410,410
XS GIS Cut Line= 4
2243028.61300034642608.2025839292243133.19734926642601.058952513
2243650.39468511642426.601343704  2243808.715731642425.728014794
#Sta/Elev= 30
       0 2287.49    15.6 2282.55    23.6 2277.73    43.7 2268.35    71.7 2257.58
    86.6 2250.07   120.6 2240.12   189.2  2238.4   226.2 2240.03   261.8 2237.66
   390.8 2237.12   400.7 2235.48   411.9 2233.91   428.8 2233.81   454.1 2233.89
  459.442235.496   479.5    2244   492.1 2252.35   496.3 2253.87   525.9  2254.7
   555.3 2256.84   576.5  2260.1   601.9 2259.46     623  2262.2   659.1 2264.87
   684.4 2269.95   708.4 2271.62   747.6 2277.25   760.4 2281.47     809 2292.36
#Mann= 7 ,-1,0
       0      .1       0  244.83     .05       0  324.83      .1       0
  344.83     .05       0   400.7    .045       0  459.44     .06       0
  634.83      .1       0
#XS Ineff= 2 , 0
          220.94 2246.83
Permanent Ineff=
       F       F
Bank Sta=400.7,459.44
XS Rating Curve= 0 ,0
Exp/Cntr(USF)=0,0
Exp/Cntr=0.3,0.1

Type RM Length L Ch R = 1 ,109909  ,492.2,492.2,492.2
XS GIS Cut Line= 2
2243083.73832227 643003.261025872243820.08415151642826.315750824
#Sta/Elev= 30
       0 2275.91    37.5  2264.2    62.2  2253.4    70.4 2248.21    74.5 2246.47
    86.8 2242.71    95.1 2241.36   187.8 2237.76   351.3 2235.07   370.7  2232.9
   383.5  2234.1   406.7 2232.51   424.2 2234.12   432.4 2232.06   441.8 2232.02
   465.3 2230.66   494.1 2230.75   502.9 2232.02   510.6 2234.25   516.2  2234.3
   543.5 2231.26   568.2  2234.2   572.3  2236.2   580.5 2241.92   612.4 2242.48
   625.8 2251.33   674.7 2260.04   688.7 2263.36   736.8 2276.72   757.3 2285.82
#Mann= 4 ,-1,0
       0      .1       0   441.8    .045       0   502.9     .06       0
     590      .1       0
Bank Sta=441.8,502.9
XS Rating Curve= 0 ,0
Exp/Cntr(USF)=0,0
Exp/Cntr=0.3,0.1

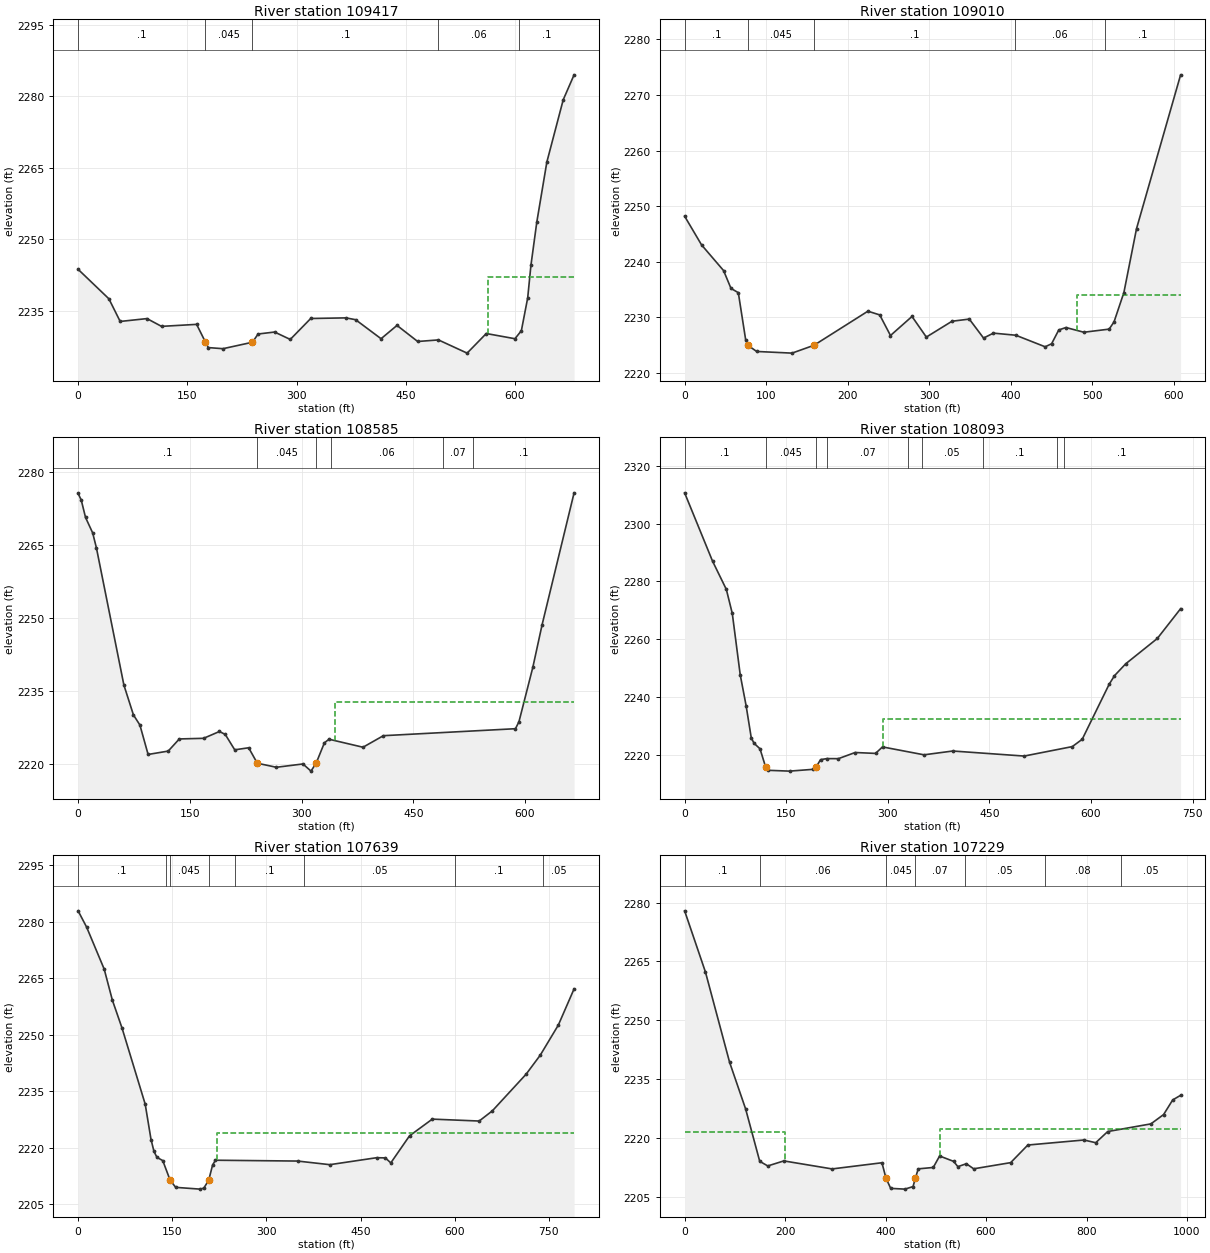
Type RM Length L Ch R = 1 ,109417  ,407.6,407.6,407.6
XS GIS Cut Line= 3
2243270.01342576643355.3247935182243633.41208602 643388.43400112
2243922.36856524643259.700386992
#Sta/Elev= 30
       0 2243.73    42.3 2237.55    57.8  2232.8    94.6  2233.4   114.6 2231.77
   162.8 2232.19   174.9 2228.47   178.9 2227.32     199 2227.09   239.52228.444
   247.2 2230.17   269.9 2230.58   291.4 2229.03   319.5 2233.42   367.9 2233.55
   381.1 2233.17   416.1 2229.18     438 2231.97   466.4  2228.6   494.9 2228.93
   534.3 2226.16   560.6 2230.27     600 2229.18   608.8 2230.86   617.5 2237.76
   621.9 2244.53     630 2253.64   643.8 2266.22   666.3 2279.28   681.2  2284.5
#Mann= 5 ,-1,0
       0      .1       0   174.9    .045       0   239.5      .1       0
   494.9     .06       0   604.9      .1       0
#XS Ineff= 2 , 0
                          563.57         2242.16
Permanent Ineff=
       F       F
Bank Sta=174.9,239.5
XS Rating Curve= 0 ,0
Exp/Cntr(USF)=0,0
Exp/Cntr=0.3,0.1

Type RM Length L Ch R = 1 ,109010  ,425,425,425
XS GIS Cut Line= 4
2243583.28617496643807.6102441852243687.44762858643607.663916614
2243976.15181307643476.4347418462244020.58530945643427.672085182
#Sta/Elev= 30
       0 2248.19    20.8 2243.02    47.8  2238.4    56.9 2235.19    65.9 2234.42
    74.9 2225.95   77.682224.935    88.4 2223.84   131.8 2223.54  158.732224.952
   224.9 2231.09   239.4 2230.42   252.6 2226.71     279 2230.14   296.6 2226.43
   328.1 2229.28   349.3 2229.67   366.8 2226.25   378.9 2227.14   406.4 2226.76
   442.4 2224.68   450.3 2225.23   459.1 2227.71   467.9 2228.15   489.9  2227.3
   520.9 2227.86   526.9 2229.16     539 2234.45   554.5 2245.95   608.6 2273.64
#Mann= 5 ,-1,0
       0      .1       0   77.68    .045       0  158.73      .1       0
  405.45     .06       0  515.45      .1       0
#XS Ineff= 2 , 0
                          481.97         2233.93
Permanent Ineff=
       F       F
Bank Sta=77.68,158.73
XS Rating Curve= 0 ,0
Exp/Cntr(USF)=0,0
Exp/Cntr=0.3,0.1

Type RM Length L Ch R = 1 ,108585  ,491.7,491.7,491.7
XS GIS Cut Line= 2
2243875.24046481644134.0165569642244215.35421619  643561.5801575
#Sta/Elev= 30
       0 2275.54     4.2 2274.19      10 2270.61    19.6 2267.43    24.6 2264.37
    61.5 2236.23    74.3 2230.11      83 2228.03      94    2222     121 2222.69
   135.9 2225.18   168.5 2225.31   189.8 2226.71   197.6  2226.1   210.3 2222.95
     229 2223.37   240.6  2220.2   266.2 2219.37   301.9 2220.05   312.7 2218.58
  319.772220.275   330.7 2224.39   336.9 2225.12   382.5 2223.48   409.9 2225.85
   587.2 2227.28   591.9 2228.72   610.5 2239.86     623 2248.64   665.9 2275.66
#Mann= 6 ,-1,0
       0      .1       0   240.6    .045       0  319.77     .07       0
     340     .06       0     490     .07       0     530      .1       0
#XS Ineff= 2 , 0
                          344.26         2232.72
Permanent Ineff=
       F       F
Bank Sta=240.6,319.77
XS Rating Curve= 0 ,0
Exp/Cntr(USF)=0,0
Exp/Cntr=0.3,0.1

Type RM Length L Ch R = 1 ,108093  ,453.4,453.4,453.4
XS GIS Cut Line= 2
2244260.30784162644385.7601263072244634.02947644643755.939527946
#Sta/Elev= 30
       0 2310.67    41.2 2287.02    61.6 2277.21    70.4 2268.87    82.1 2247.64
    90.8 2236.93    98.4 2225.79   102.5  2223.9   111.3 2221.99  119.632215.678
   122.9 2214.54     155 2214.25   190.1 2214.88  194.14 2215.68   200.7 2218.22
     210 2218.59   227.1 2218.57   251.8  2220.7   281.9 2220.39   292.2 2222.64
   353.5  2219.9     396 2221.22   501.4 2219.47   572.5 2222.75   587.1 2225.29
   626.8  2244.3   634.7  2247.3   651.3 2251.43     698 2260.21   732.4 2270.53
#Mann= 9 ,-1,0
       0      .1       0  119.63    .045       0  194.14      .1       0
     210     .07       0     330      .1       0     350     .05       0
     440      .1       0     550     .05       0     560      .1       0
#XS Ineff= 2 , 0
                          293.43         2232.31
Permanent Ineff=
       F       F
Bank Sta=119.63,194.14
XS Rating Curve= 0 ,0
Exp/Cntr(USF)=0,0
Exp/Cntr=0.3,0.1

Type RM Length L Ch R = 1 ,107639  ,410.7,410.7,410.7
XS GIS Cut Line= 2
2244648.02740475644616.7922775132245055.31879145643939.596535144
#Sta/Elev= 30
       0 2282.91    13.6 2278.58    41.6 2267.43    54.6 2259.21    70.1 2251.75
   106.9 2231.61   116.2 2222.21   120.9 2219.06   125.6 2217.49   134.9 2216.62
  146.622211.423   155.5 2209.52   194.3 2209.05   200.3 2209.32  208.112211.425
   214.3 2215.46   218.9 2216.72   349.8  2216.5     401 2215.54   475.7 2217.39
   489.5 2217.34   498.2 2216.01     528 2223.19   564.3 2227.63     639 2227.12
     660 2229.83   713.7 2239.54   736.3  2244.6   765.1 2252.59   790.2  2262.2
#Mann= 8 ,-1,0
       0      .1       0     140     .07       0  146.62    .045       0
  208.11     .07       0     250      .1       0     360     .05       0
     600      .1       0     740     .05       0
#XS Ineff= 2 , 0
                          220.65         2223.83
Permanent Ineff=
       F       F
Bank Sta=146.62,208.11
XS Rating Curve= 0 ,0
Exp/Cntr(USF)=0,0
Exp/Cntr=0.3,0.1

Type RM Length L Ch R = 1 ,107229  ,54.1,54.1,54.1
XS GIS Cut Line= 4
 2244682.7255938644757.1511212012245007.35705422644748.531932492
 2245164.9537211644620.3519061972245311.99846089644185.056738636
#Sta/Elev= 30
       0 2277.89    41.5  2262.3    89.5 2239.37   121.5 2227.45   149.5 2214.16
   165.5 2212.98   197.5 2214.26   293.6 2212.22   392.8 2213.79  400.81 2209.87
   410.2 2207.27   438.6 2207.08   454.7 2207.73  459.36 2209.87     465 2212.24
   494.9 2212.59   507.6 2215.51   535.5 2214.14   543.9  2212.8   560.8 2213.54
   575.4 2212.25     649 2213.82   683.2  2218.3   794.9 2219.58   818.3 2218.89
   842.2 2221.73   928.1 2223.68   953.4 2226.05   971.6 2229.78   987.3 2230.95
#Mann= 7 ,-1,0
       0      .1       0     150     .06       0  400.81    .045       0
  459.36     .07       0  557.89     .05       0  717.89     .08       0
  867.89     .05       0
#XS Ineff= 2 , 0
          199.28 2221.54  509.03         2222.37
Permanent Ineff=
       F       F
Bank Sta=400.81,459.36
XS Rating Curve= 0 ,0
Exp/Cntr(USF)=0,0
Exp/Cntr=0.3,0.1