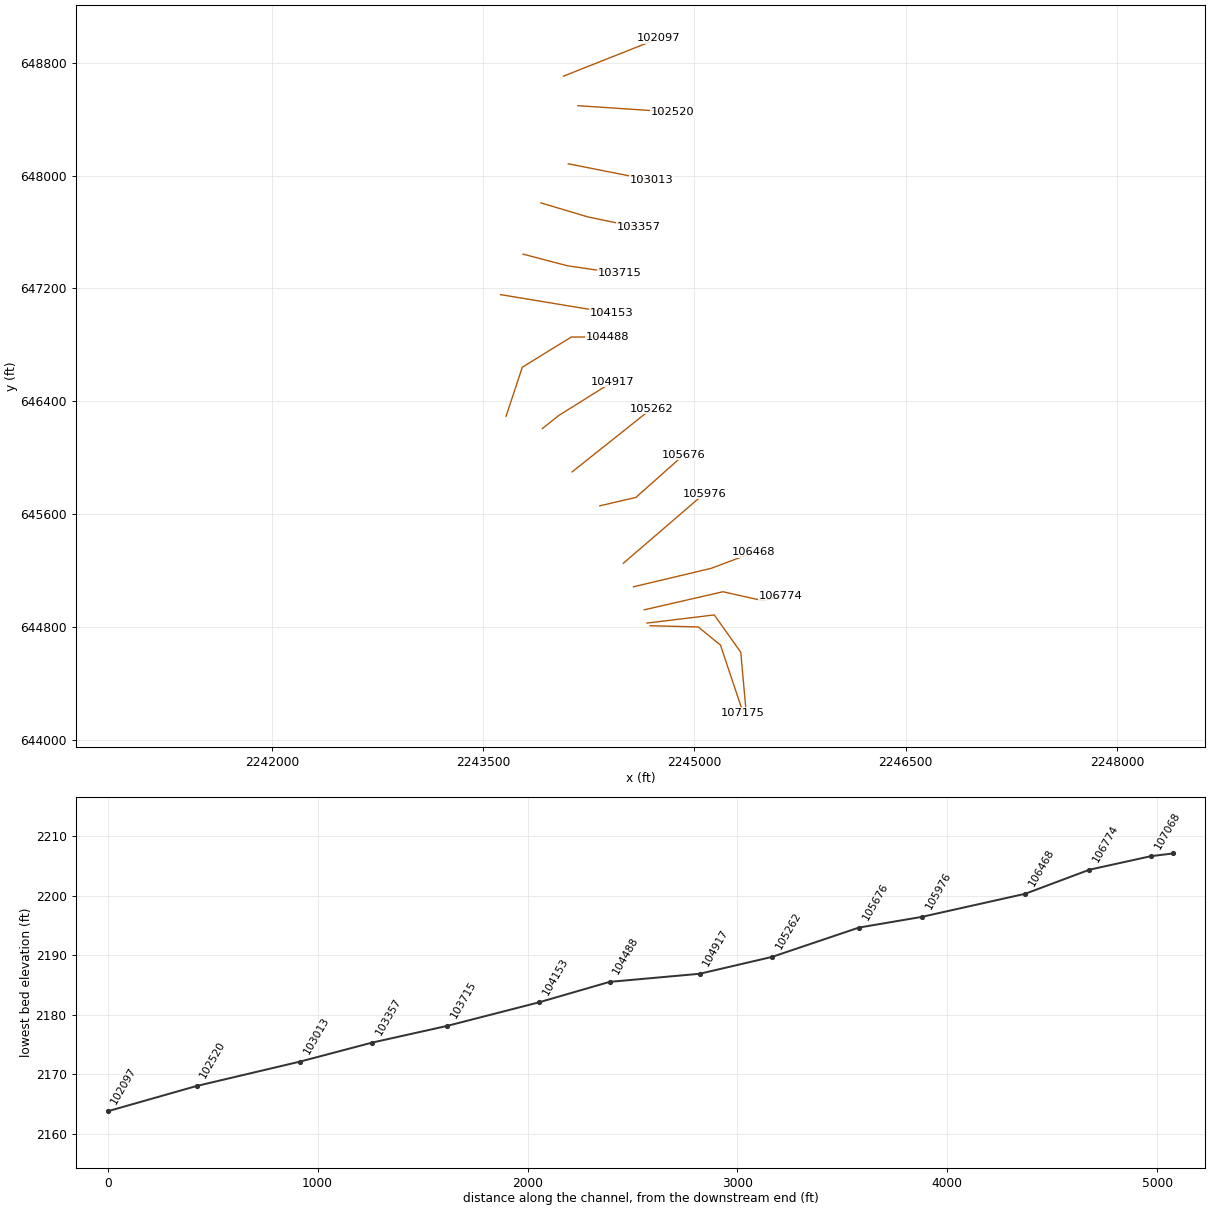
HEC-RAS study MIDFKRIV.prj: MIDFKRIV

--- MIDFKRIV.g01 (geometry) --- (continued)

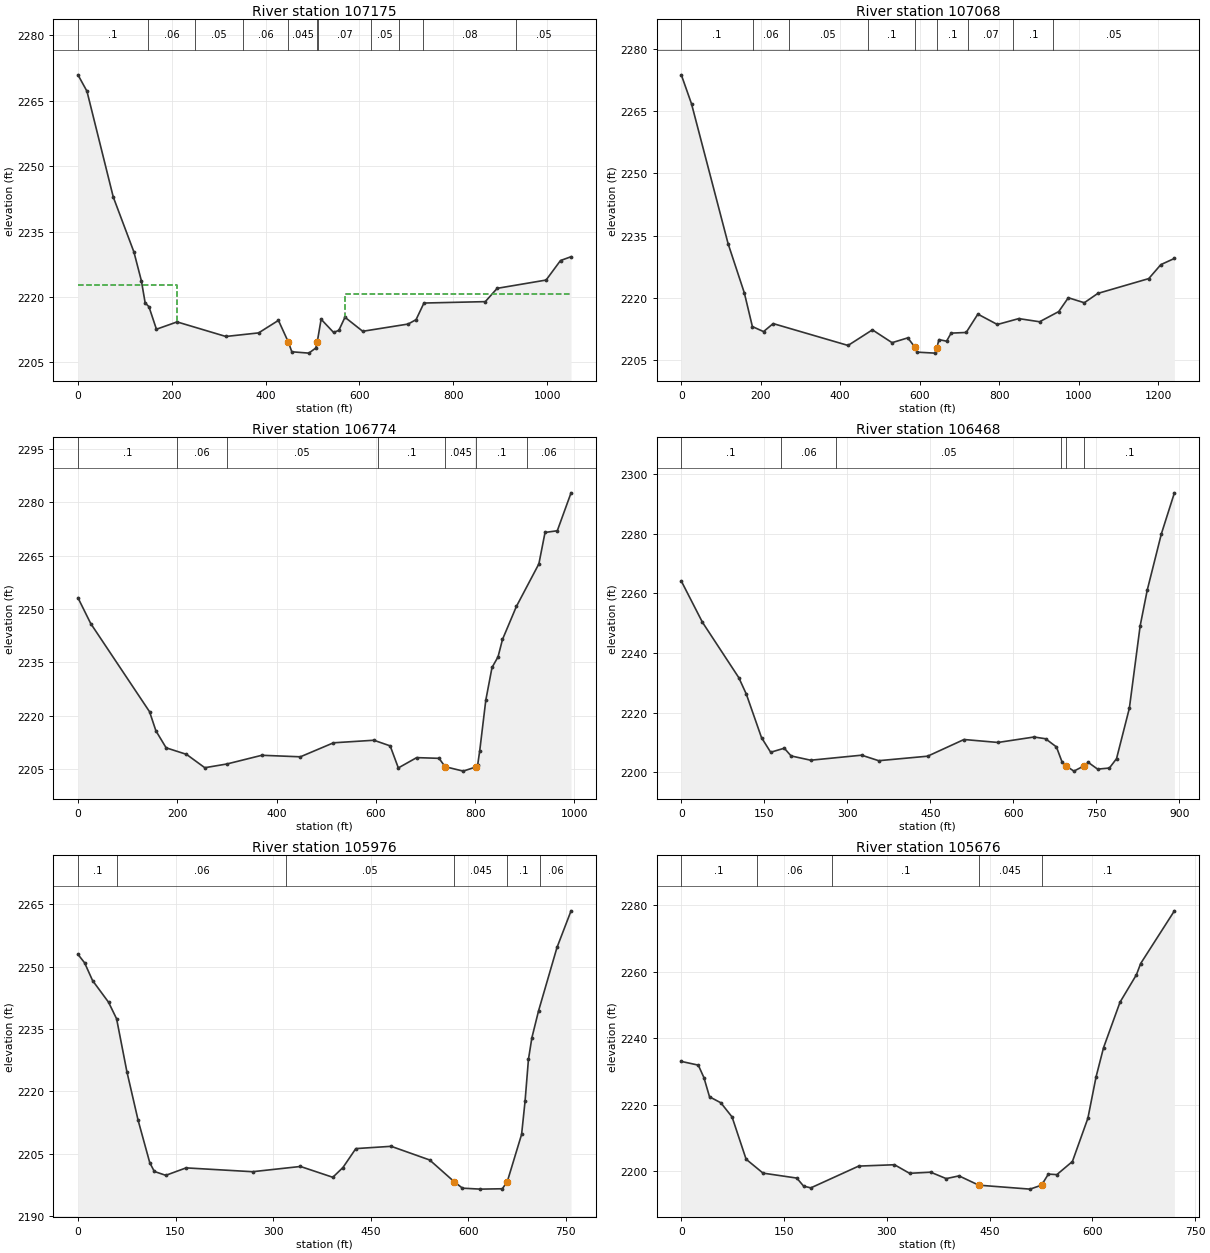
Type RM Length L Ch R = 1 ,107175  ,106.7,106.7,106.7
XS GIS Cut Line= 4
2244684.93903938644808.7621212552245026.55309889644800.142932547
2245184.14976578644671.9629062522245345.08935936644191.895432006
#Sta/Elev= 30
       0 2270.95    19.2 2267.19    75.3 2242.92   119.3 2230.32   135.3 2223.68
   143.3 2218.63   151.3 2217.78   167.3  2212.6   211.3 2214.28   315.3 2210.94
   385.1 2211.76   427.4 2214.63  448.662209.615   455.9 2207.43   492.2 2207.12
   507.1  2208.3  510.042209.618   518.4 2214.89   544.9 2211.87   556.2 2212.34
   569.2 2215.35   607.1 2212.13   703.9 2213.79   720.8  2214.8   737.6 2218.61
   868.4 2218.93   893.7 2221.98     998 2223.88  1028.7 2228.36  1051.2 2229.23
#Mann= 11 ,-1,0
       0      .1       0     150     .06       0     250     .05       0
  351.72     .06       0  448.66    .045       0  510.04     .06       0
  511.72     .07       0  624.87     .05       0  684.87      .1       0
  734.87     .08       0  934.87     .05       0
#XS Ineff= 2 , 0
          211.41 2222.72  568.38         2220.71
Permanent Ineff=
       F       F
Bank Sta=448.66,510.04
XS Rating Curve= 0 ,0
Exp/Cntr(USF)=0,0
Exp/Cntr=0.3,0.1

Type RM Length L Ch R = 1 ,107068  ,293.5,293.5,293.5
XS GIS Cut Line= 4
2244662.67082126644827.567760751 2245140.4115782644885.352905335
2245328.47813847644620.7788784722245367.54623739644187.255095678
#Sta/Elev= 30
       0 2273.73    25.7 2266.75   117.8 2233.03   158.7 2221.16   178.9 2213.06
     207 2211.85   231.2 2213.78   419.7 2208.51     481 2212.27   530.5 2209.18
   570.1 2210.34  588.472208.028   594.3 2206.89   638.5 2206.66   643.4 2207.96
   648.3 2209.92   667.6 2209.54   679.1 2211.48     717 2211.64   746.4 2216.06
   795.5 2213.56   849.4 2214.98   901.8 2214.22     950 2216.68   974.1 2220.01
  1014.3  2218.8  1048.3 2221.05  1176.5 2224.62    1207 2227.99  1241.1 2229.48
#Mann= 9 ,-1,0
       0      .1       0     180     .06       0     270     .05       0
     470      .1       0  588.47    .045       0   643.4      .1       0
  721.22     .07       0  835.83      .1       0  935.83     .05       0
Bank Sta=588.47,643.4
XS Rating Curve= 0 ,0
Exp/Cntr(USF)=0,0
Exp/Cntr=0.3,0.1

Type RM Length L Ch R = 1 ,106774  ,306.3,306.3,306.3
XS GIS Cut Line= 4
2244643.10479541644921.4995369362245201.98669266645049.640966415
2245486.05925922644986.3421879982245611.11294341645017.219640884
#Sta/Elev= 30
       0 2253.16    25.7 2245.91   144.2  2221.1     157 2215.73   177.6 2210.94
   218.6  2209.1   255.5 2205.34     300 2206.39   370.4 2208.84     448 2208.41
   514.7 2212.35   596.1 2213.07   628.9 2211.48   645.3 2205.28   682.2 2208.18
   727.3 2207.98   739.5 2205.63     776 2204.38  802.642205.608   805.1 2206.13
   809.2 2210.05   821.5 2224.36     834 2233.54   846.1 2236.52   855.1 2241.43
   883.1 2250.71   928.4  2262.7   940.8 2271.53   965.5 2272.01   993.2 2282.68
#Mann= 7 ,-1,0
       0      .1       0     200     .06       0     300     .05       0
  603.38      .1       0   739.5    .045       0  802.64      .1       0
  904.42     .06       0
Bank Sta=739.5,802.64
XS Rating Curve= 0 ,0
Exp/Cntr(USF)=0,0
Exp/Cntr=0.3,0.1

Type RM Length L Ch R = 1 ,106468  ,491.9,491.9,491.9
XS GIS Cut Line= 3
2244567.07802506645084.8905851652245117.90153385645215.474809035
2245422.09638246645329.804564177
#Sta/Elev= 30
       0 2264.11    38.1 2250.31   103.9 2231.69   117.5 2226.17     145 2211.55
   161.5 2206.66   186.1 2208.02   198.4 2205.43   233.8 2203.99   325.9 2205.68
   356.7 2203.83   445.1 2205.34   510.9 2210.94   572.3 2209.95   637.5 2211.78
   658.3 2211.19   677.9 2208.45   688.2 2203.33  694.772202.143   709.5 2200.33
  728.622202.184   735.2 2203.29   752.3    2201   773.6 2201.37   786.5 2204.51
   809.7 2221.44   829.2 2249.08     842 2261.07   867.6 2279.99   891.1 2293.71
#Mann= 6 ,-1,0
       0      .1       0     180     .06       0     280     .05       0
  686.09      .1       0  694.77    .045       0  728.62      .1       0
Bank Sta=694.77,728.62
XS Rating Curve= 0 ,0
Exp/Cntr(USF)=0,0
Exp/Cntr=0.3,0.1

Type RM Length L Ch R = 1 ,105976  ,300,300,300
XS GIS Cut Line= 2
2244495.13760873645251.8761321372245069.83820887645746.042990766
#Sta/Elev= 30
       0 2252.93    10.2  2250.9    22.5 2246.62      47 2241.42    59.4 2237.43
    75.2 2224.73    92.4 2213.06   110.4  2202.8   117.4  2200.7     135 2199.77
   166.2 2201.56   268.3 2200.64     342  2201.9   391.7  2199.3   407.3 2201.65
   427.1  2206.2   481.4 2206.75   540.6 2203.46  577.95 2198.28     591 2196.68
   618.6 2196.45   652.3 2196.54  659.92 2198.28   681.9 2209.63   687.2 2217.58
   692.4 2227.65   697.7 2232.87   707.9 2239.31   736.3 2254.59   757.9  2263.4
#Mann= 6 ,-1,0
       0      .1       0      60     .06       0     320     .05       0
  577.95    .045       0  659.92      .1       0     710     .06       0
Bank Sta=577.95,659.92
XS Rating Curve= 0 ,0
Exp/Cntr(USF)=0,0
Exp/Cntr=0.3,0.1

Type RM Length L Ch R = 1 ,105676  ,413.8,413.8,413.8
XS GIS Cut Line= 3
2244328.01202476645658.8484167772244584.21716297645718.662930149
2244925.72868709646021.895524861
#Sta/Elev= 30
       0 2233.03    24.8 2231.91      33 2228.17    41.2 2222.39    57.7  2220.6
    74.1 2216.34    94.6 2203.64   119.3 2199.46   168.6 2197.97   178.6 2195.54
   189.1 2195.03   258.9 2201.57   311.2 2201.98   333.2  2199.4     364 2199.74
   386.7 2197.81   405.4 2198.63   434.2 2195.84   509.1 2194.65   525.9 2195.85
   535.8 2199.17   548.2 2199.01   570.9 2202.95   593.5 2215.95   605.4 2228.35
   616.3 2237.12   640.4 2250.83   664.4 2259.09   670.5 2262.43   719.8 2278.28
#Mann= 5 ,-1,0
       0      .1       0     110     .06       0     220      .1       0
   434.2    .045       0   525.9      .1       0
Bank Sta=434.2,525.9
XS Rating Curve= 0 ,0
Exp/Cntr(USF)=0,0
Exp/Cntr=0.3,0.1

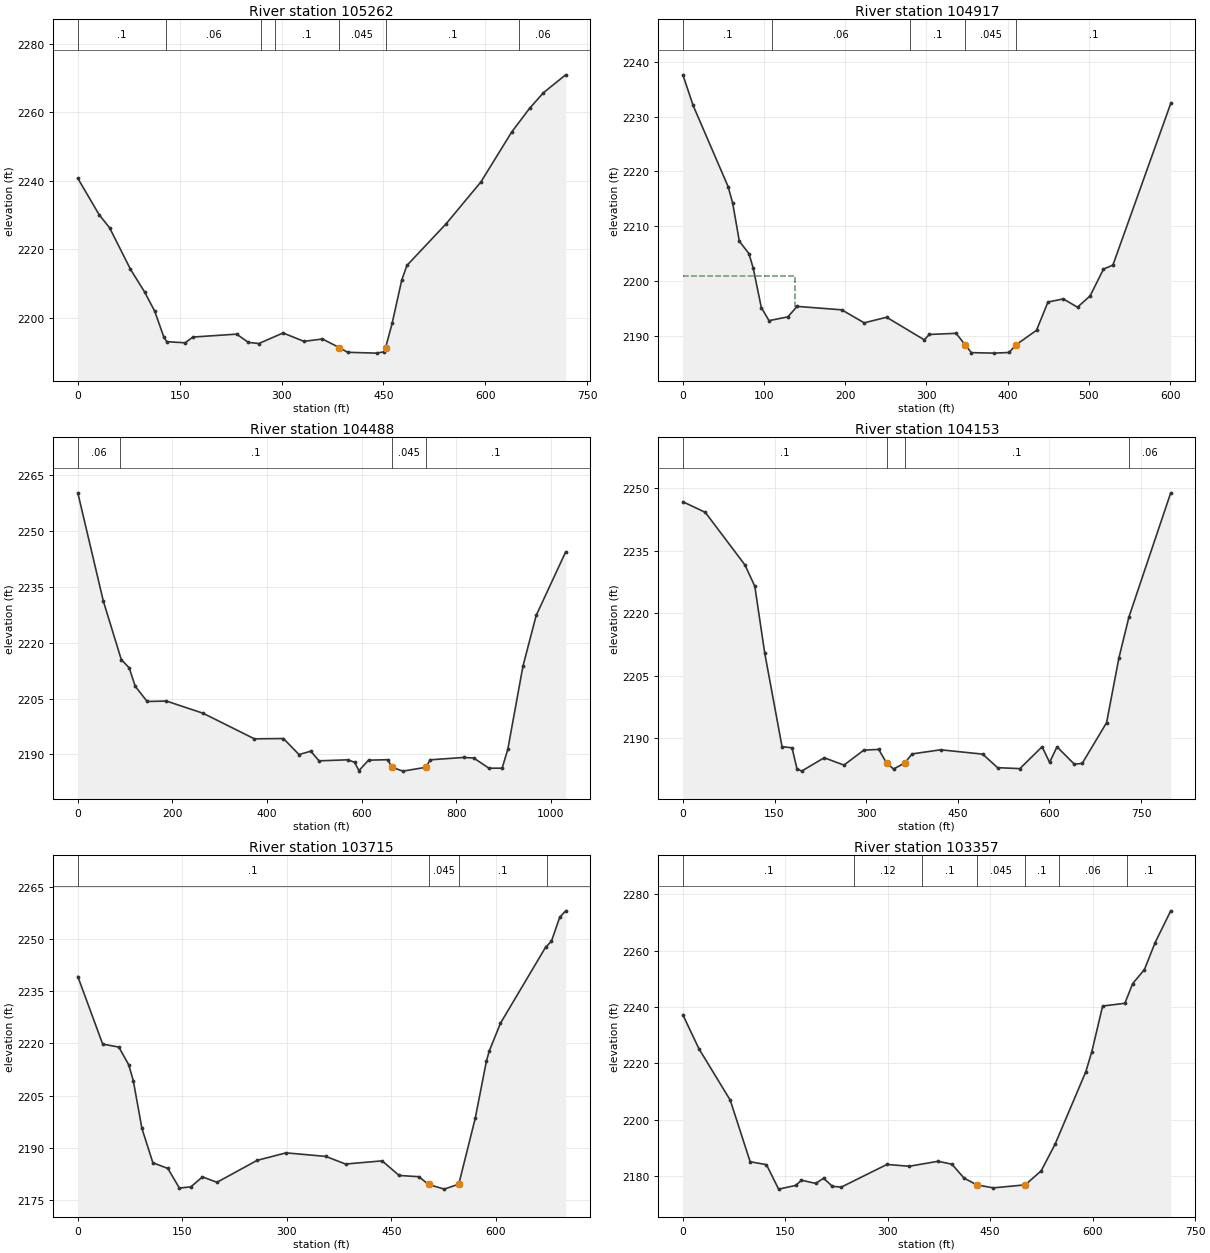
Type RM Length L Ch R = 1 ,105262  ,345.5,345.5,345.5
XS GIS Cut Line= 2
2244131.56344813645899.7196923382244693.78690456646346.580733375
#Sta/Elev= 30
       0 2240.73    31.4  2230.1    46.8 2226.29    77.4 2214.24    98.3 2207.57
   113.2 2201.96   126.7 2194.39   130.9 2193.07   158.1 2192.73   169.4 2194.41
   233.8 2195.26   251.1 2192.86   266.5 2192.52   302.2  2195.6   332.9 2193.16
   360.2 2193.84  384.722191.358   397.2 2189.96   439.9 2189.72   450.4 2190.08
  453.182191.358   462.7 2198.37   476.9 2211.04   484.5  2215.3   542.4 2227.49
   593.5 2239.68   638.8 2254.23     665 2261.11   685.5 2265.69   718.2 2270.91
#Mann= 7 ,-1,0
       0      .1       0     130     .06       0     270     .05       0
     290      .1       0  384.72    .045       0  453.18      .1       0
     650     .06       0
Bank Sta=384.72,453.18
XS Rating Curve= 0 ,0
Exp/Cntr(USF)=0,0
Exp/Cntr=0.3,0.1

Type RM Length L Ch R = 1 ,104917  ,428.7,428.7,428.7
XS GIS Cut Line= 3
2243920.67733391  646206.94167082244037.19068282646299.997691284
2244420.39340334646539.031794031
#Sta/Elev= 30
       0  2237.6    12.6 2232.02    55.7 2217.23    61.3 2214.25    69.5 2207.29
    81.3 2205.02    86.6 2202.39    96.6 2195.18   106.1  2192.8   129.3 2193.49
   140.7  2195.4   195.7 2194.77   223.3  2192.4   250.9 2193.42   297.3  2189.3
   303.5 2190.28   336.5 2190.49   347.8 2188.35   355.3 2186.97   383.6 2186.88
   401.8    2187   410.12188.375   435.5 2191.04   449.6 2196.19   468.5 2196.76
     486 2195.25   501.5 2197.31     518 2202.19   529.6 2202.93   600.8 2232.38
#Mann= 5 ,-1,0
       0      .1       0     110     .06       0  279.11      .1       0
   347.8    .045       0   410.1      .1       0
#XS Ineff= 2 , 0
           138.5 2200.88
Permanent Ineff=
       F       F
Bank Sta=347.8,410.1
XS Rating Curve= 0 ,0
Exp/Cntr(USF)=0,0
Exp/Cntr=0.3,0.1

Type RM Length L Ch R = 1 ,104488  ,335.4,335.4,335.4
XS GIS Cut Line= 4
2243662.63624347646293.9917085992243777.87953669646641.711342866
2244125.19793679646855.6086502422244382.48568532646856.931315962
#Sta/Elev= 30
       0 2260.22    53.9 2231.19    91.9 2215.47   108.7 2213.23   121.3 2208.33
   146.6 2204.21   187.3 2204.33   264.6 2201.07   373.4 2194.19   434.8 2194.27
   467.7 2189.97   492.6 2190.87   510.1 2188.28     571 2188.56   585.1 2187.89
   594.5 2185.66   614.7 2188.46   655.4 2188.59   664.1 2186.58   687.4 2185.52
  736.48 2186.56   744.8 2188.55   815.8 2189.19   837.2 2189.04   869.2 2186.31
   897.2 2186.31   909.2 2191.38   941.2 2213.67   969.2 2227.31  1031.5 2244.35
#Mann= 4 ,-1,0
       0     .06       0      90      .1       0   664.1    .045       0
  736.48      .1       0
Bank Sta=664.1,736.48
XS Rating Curve= 0 ,0
Exp/Cntr(USF)=0,0
Exp/Cntr=0.3,0.1

Type RM Length L Ch R = 1 ,104153  ,438.1,438.1,438.1
XS GIS Cut Line= 2
2243624.00857515647156.4548884162244411.81785464647026.209574192
#Sta/Elev= 30
       0 2246.75    36.7  2244.2   101.5  2231.6   117.7 2226.48     134  2210.4
   162.3 2187.96   178.6 2187.69   186.7  2182.7   194.3 2182.09   231.3  2185.3
   263.7 2183.54   296.1 2187.13   320.5  2187.3   333.3 2184.07   344.8  2182.6
   363.4 2184.06   375.1 2186.22   421.8 2187.21   490.7 2186.17   515.1 2182.92
   551.6 2182.69     588 2187.94   600.2  2184.2   612.4 2187.92   640.7 2183.76
   653.6 2183.95   693.5 2193.72   713.7 2209.25   730.1 2219.09   798.5 2248.89
#Mann= 4 ,-1,0
       0      .1       0   333.3    .045       0   363.4      .1       0
     730     .06       0
Bank Sta=333.3,363.4
XS Rating Curve= 0 ,0
Exp/Cntr(USF)=0,0
Exp/Cntr=0.3,0.1

Type RM Length L Ch R = 1 ,103715  ,357.7,357.7,357.7
XS GIS Cut Line= 3
2243783.16081421647443.6947590442244095.54880507647361.761684527
2244468.60040165647306.439226334
#Sta/Elev= 30
       0 2239.21    35.7 2219.79    58.9 2218.93      73 2213.86    79.6 2209.31
      92 2195.58   107.7  2185.7   129.2 2184.06   145.8 2178.42   162.3 2178.78
   178.9 2181.63   199.7 2180.08   257.4 2186.39   298.8 2188.54   355.9 2187.52
   384.2 2185.33   436.7 2186.24   461.1 2182.05   489.4 2181.69   503.4 2179.46
   525.8 2178.12  546.722179.546   570.3 2198.42   586.4 2214.91   590.5 2217.81
   606.6  2225.8   671.3 2247.61   679.7 2249.34   691.6 2256.23   700.1 2258.08
#Mann= 4 ,-1,0
       0      .1       0   503.4    .045       0  546.72      .1       0
  672.95     .06       0
Bank Sta=503.4,546.72
XS Rating Curve= 0 ,0
Exp/Cntr(USF)=0,0
Exp/Cntr=0.3,0.1

Type RM Length L Ch R = 1 ,103357  ,344.1,344.1,344.1
XS GIS Cut Line= 3
2243909.75174592 647806.932312322244245.91225877647706.962289499
2244601.96385909647633.080908009
#Sta/Elev= 30
       0 2237.19    23.4 2225.21    69.3 2206.92    98.5 2185.05   122.4 2183.99
   140.2 2175.31   165.3 2176.63   173.6 2178.48   194.5 2177.35     206 2179.17
   218.9  2176.3   232.1 2176.04   298.8 2184.08   331.4 2183.43   373.4 2185.19
   393.9 2184.17   411.6 2179.24  430.07 2176.84   454.4 2175.76  501.332176.826
   524.6  2181.8     545 2191.28     590 2217.02   598.8 2224.15   614.6 2240.33
   647.2 2241.31   658.6 2248.31   675.8 2253.28   691.5 2262.88   714.3 2274.14
#Mann= 7 ,-1,0
       0      .1       0     250     .12       0     350      .1       0
  430.07    .045       0  501.33      .1       0  550.71     .06       0
  650.71      .1       0
Bank Sta=430.07,501.33
XS Rating Curve= 0 ,0
Exp/Cntr(USF)=0,0
Exp/Cntr=0.3,0.1

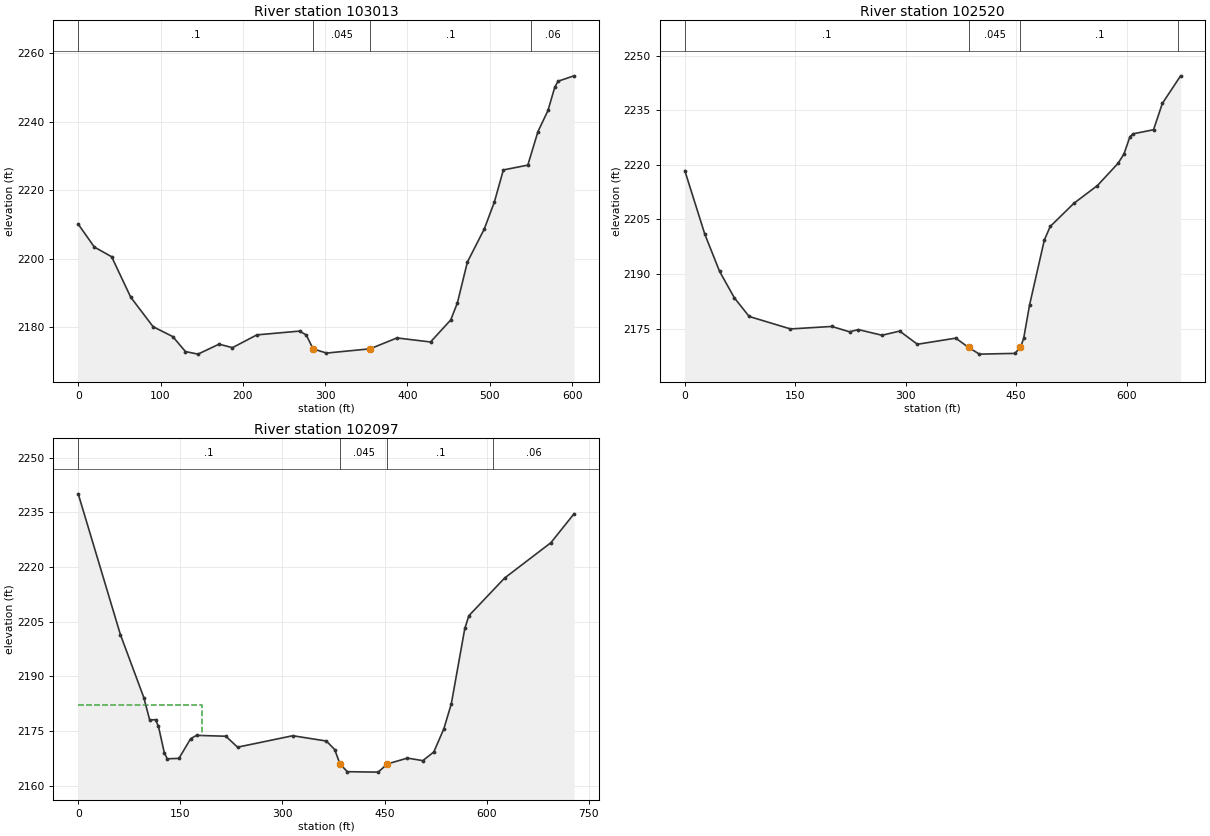
Type RM Length L Ch R = 1 ,103013  ,492.6,492.6,492.6
XS GIS Cut Line= 2
2244104.33618582648084.3286031132244695.19372997647967.371372548
#Sta/Elev= 30
       0  2210.1    19.6 2203.39    40.6 2200.56    63.8 2188.74      91 2180.12
   114.9 2177.23   130.3 2172.86   145.5 2172.11   171.1 2175.02   187.4    2174
     217 2177.73     269 2178.84   277.1 2177.68   285.3 2173.65   301.6 2172.42
   354.6 2173.66   387.2 2176.84     428 2175.66   452.5 2182.08   460.6 2187.04
   472.8 2199.02   493.2 2208.61   505.5 2216.49   516.5 2225.91   546.2 2227.32
   558.5 2237.11   570.7 2243.28   578.9 2250.06   582.9 2251.82   602.3  2253.4
#Mann= 4 ,-1,0
       0      .1       0   285.3    .045       0   354.6      .1       0
     550     .06       0
Bank Sta=285.3,354.6
XS Rating Curve= 0 ,0
Exp/Cntr(USF)=0,0
Exp/Cntr=0.3,0.1

Type RM Length L Ch R = 1 ,102520  ,422.8,422.8,422.8
XS GIS Cut Line= 2
 2244172.9908909648496.2893296152244844.89477472648451.387793786
#Sta/Elev= 30
       0 2218.39    27.2 2200.91    47.2 2190.74    67.3 2183.46    87.4 2178.35
   143.5 2174.93   199.6 2175.61   223.7 2174.14   235.7 2174.75   267.8 2173.19
   291.8 2174.34   315.9 2170.72     368  2172.4  385.482169.833   400.1 2168.01
   448.2 2168.21  455.872169.834   460.2 2172.31   468.3 2181.58   488.3 2199.36
   496.3 2203.07   528.2 2209.39   560.4 2214.31   588.5 2220.43   596.5    2223
   604.5 2227.69   608.5  2228.5   636.6 2229.63   648.6 2236.87   673.4 2244.44
#Mann= 4 ,-1,0
       0      .1       0  385.48    .045       0  455.87      .1       0
     670     .06       0
Bank Sta=385.48,455.87
XS Rating Curve= 0 ,0
Exp/Cntr(USF)=0,0
Exp/Cntr=0.3,0.1

Type RM Length L Ch R = 1 ,102097  ,488.5,488.5,488.5
XS GIS Cut Line= 2
2244070.53050468648705.829206628 2244747.7550297648973.827132962
#Sta/Elev= 30
       0 2240.07      62 2201.47    96.4  2184.2     105 2178.07   113.6 2178.15
   117.9 2176.29   126.5 2169.07   130.8 2167.43     148 2167.54   165.2 2172.94
   173.8 2173.85   216.9 2173.61   234.1 2170.61   315.1 2173.75   364.5  2172.3
   376.8 2169.95  384.512166.018   395.3 2163.89   440.6 2163.77  454.142166.015
   483.6 2167.62   506.2 2166.92   522.3 2169.29   537.1 2175.64   548.1 2182.52
   567.9 2203.16   573.9 2206.66   626.4 2216.99   694.4 2226.68   728.3 2234.59
#Mann= 4 ,-1,0
       0      .1       0  384.51    .045       0  454.14      .1       0
     610     .06       0
#XS Ineff= 2 , 0
          182.25 2182.24
Permanent Ineff=
       F       F
Bank Sta=384.51,454.14
XS Rating Curve= 0 ,0
Exp/Cntr(USF)=0,0
Exp/Cntr=0.3,0.1