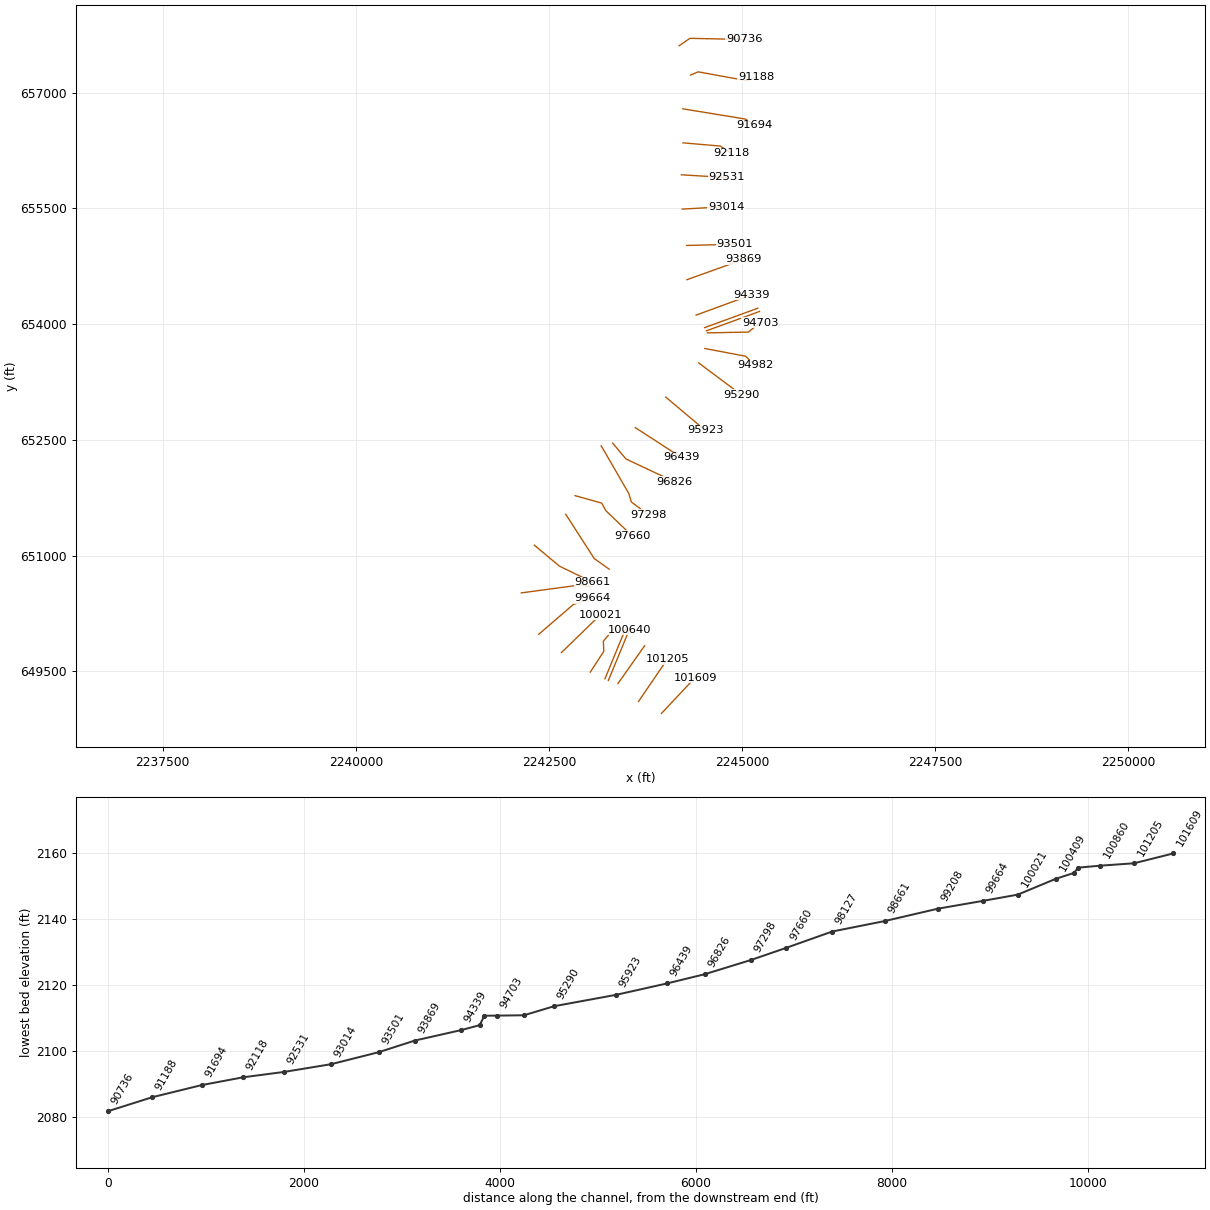
HEC-RAS study MIDFKRIV.prj: MIDFKRIV

--- MIDFKRIV.g01 (geometry) --- (continued)

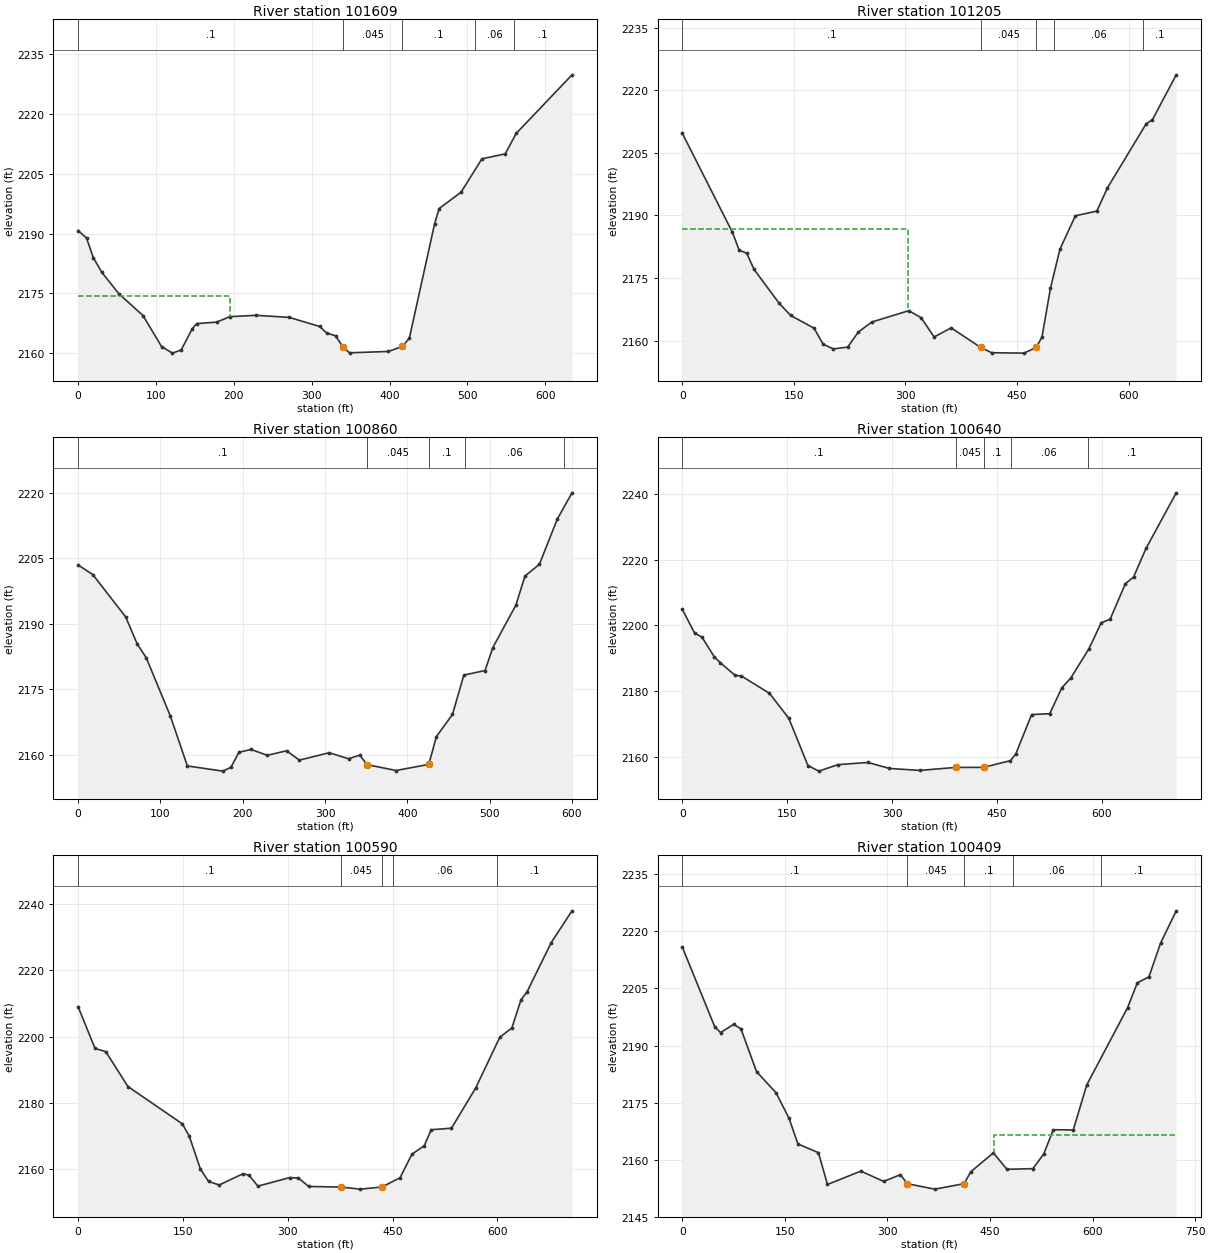
Type RM Length L Ch R = 1 ,101609  ,403.8,403.8,403.8
XS GIS Cut Line= 2
2243959.13670186648954.9663820432244393.10864511 649417.55576079
#Sta/Elev= 30
       0 2190.78    10.8  2188.9    19.5 2183.97    30.5 2180.27    52.4  2174.9
    83.4 2169.43   107.2 2161.65   121.2 2160.01   132.5 2160.83   146.6 2166.15
   152.3 2167.42   177.8 2167.79     195 2169.16   228.7  2169.5   271.1 2168.98
   310.2  2166.7   319.2 2165.05   330.6 2164.36  339.722161.657   348.6 2160.09
   398.5 2160.43  416.372161.674   425.4 2163.76   457.9 2192.52   463.7  2196.3
   491.9 2200.42   518.6 2208.78   548.5 2210.02   562.6 2215.14   634.3 2229.86
#Mann= 5 ,-1,0
       0      .1       0  339.72    .045       0  416.37      .1       0
     510     .06       0     560      .1       0
#XS Ineff= 2 , 0
          195.48 2174.42
Permanent Ineff=
       F       F
Bank Sta=339.72,416.37
XS Rating Curve= 0 ,0
Exp/Cntr(USF)=0,0
Exp/Cntr=0.3,0.1

Type RM Length L Ch R = 1 ,101205  ,344.8,344.8,344.8
XS GIS Cut Line= 2
2243661.70560759649109.4647008362244035.28466721649658.397196596
#Sta/Elev= 30
       0 2209.65    67.4 2185.93    76.4 2181.68    86.7 2180.91    96.4 2177.06
   130.3 2168.92   145.5 2166.04   177.2 2162.96   189.2 2159.16   202.9 2158.01
   222.2 2158.44   236.7 2162.07   254.9 2164.46   304.5 2167.17   321.1 2165.48
   338.5 2160.87   361.5 2163.05   401.2 2158.35   415.8  2157.1   459.3    2157
   475.82158.353   483.5 2160.84   494.9 2172.53   507.7 2181.91   528.4  2189.9
   557.2 2191.02   571.6 2196.61   623.5 2211.91   632.1 2212.96     664 2223.67
#Mann= 5 ,-1,0
       0      .1       0   401.2    .045       0   475.8      .1       0
     500     .06       0     620      .1       0
#XS Ineff= 2 , 0
          303.02 2186.69
Permanent Ineff=
       F       F
Bank Sta=401.2,475.8
XS Rating Curve= 0 ,0
Exp/Cntr(USF)=0,0
Exp/Cntr=0.3,0.1

Type RM Length L Ch R = 1 ,100860  ,220.6,220.6,220.6
XS GIS Cut Line= 2
2243394.86909085649341.5014639112243740.66714955649831.831661434
#Sta/Elev= 30
       0 2203.49    17.9 2201.28    57.8 2191.59    71.7 2185.44    82.8 2182.23
   112.2 2168.83   132.7 2157.47   175.8 2156.28   185.6 2157.15   195.4  2160.6
   210.1 2161.24   229.7 2159.91   253.3 2160.94   268.8  2158.8     305 2160.49
   328.5 2159.12   342.2 2159.94   350.9 2157.77   386.3 2156.42  426.062157.831
   435.2 2164.17   454.8 2169.26   468.6 2178.28   494.4 2179.32   503.8 2184.58
   531.7 2194.24   542.9 2200.95   560.4 2203.65   582.1 2213.98     600 2220.01
#Mann= 5 ,-1,0
       0      .1       0   350.9    .045       0  426.06      .1       0
     470     .06       0     590      .1       0
Bank Sta=350.9,426.06
XS Rating Curve= 0 ,0
Exp/Cntr(USF)=0,0
Exp/Cntr=0.3,0.1

Type RM Length L Ch R = 1 ,100640  ,49.4,49.4,49.4
XS GIS Cut Line= 2
2243271.50701584 649383.062854062243540.62469312650036.567834961
#Sta/Elev= 30
       0 2204.88    17.5 2197.67    28.2  2196.4    45.5 2190.51    54.2 2188.65
    75.8 2184.76    84.5 2184.61   124.7 2179.35   152.3 2171.77   179.7  2157.4
   195.2 2155.69   222.9 2157.67   265.6 2158.32   296.4  2156.5   339.7 2155.91
   391.3 2156.82   431.1 2156.83   469.5 2158.88   477.1  2160.9   499.8 2172.88
   525.7 2173.16     543    2181     556 2184.04     582 2192.96   599.3 2200.77
   612.2  2201.9   633.9 2212.66   645.6 2214.68   663.5 2223.41   706.7 2240.29
#Mann= 5 ,-1,0
       0      .1       0   391.3    .045       0   431.1      .1       0
     470     .06       0     580      .1       0
Bank Sta=391.3,431.1
XS Rating Curve= 0 ,0
Exp/Cntr(USF)=0,0
Exp/Cntr=0.3,0.1

Type RM Length L Ch R = 1 ,100590  ,181.7,181.7,181.7
XS GIS Cut Line= 2
2243226.46653422649403.2525502632243495.58421149650056.757531164
#Sta/Elev= 30
       0 2209.02    24.2 2196.43    39.6 2195.48    71.3 2184.96   149.2  2173.7
   159.1 2169.96   175.1 2160.04   186.6 2156.37   201.9 2155.29   235.7 2158.65
   244.3 2158.28   257.3 2154.94   303.1 2157.53   315.3 2157.37   330.1 2154.84
   375.5 2154.67   403.7 2154.04   434.7 2154.68   460.6 2157.46   477.7 2164.57
   495.2 2167.11   505.3 2171.95   534.2  2172.4   568.8 2184.49   603.3 2199.78
   620.7 2202.64   633.7 2211.09   642.3 2213.46   676.9 2228.32   706.7 2237.91
#Mann= 5 ,-1,0
       0      .1       0   375.5    .045       0   434.7      .1       0
     450     .06       0     600      .1       0
Bank Sta=375.5,434.7
XS Rating Curve= 0 ,0
Exp/Cntr(USF)=0,0
Exp/Cntr=0.3,0.1

Type RM Length L Ch R = 1 ,100409  ,387.4,387.4,387.4
XS GIS Cut Line= 4
2243037.48765509649490.1623195812243211.15896921649757.896357695
2243206.15682184649891.7037997792243380.68335711650096.850079516
#Sta/Elev= 30
       0 2215.85    47.5 2194.89      56 2193.41    75.1 2195.58    85.8 2194.37
   108.5 2183.17   137.1 2177.58   156.2 2170.85     169 2164.17   199.1 2161.86
   212.3 2153.51   261.1 2157.02   294.4 2154.32   319.1 2156.09     329 2153.71
   369.3 2152.29  412.312153.729   421.6  2156.8     455 2161.82   474.7  2157.5
   512.7 2157.67   528.5 2161.48   542.6 2167.89   571.8 2167.83   591.5 2179.65
   651.3 2199.96   665.5 2206.46   682.5 2208.05   699.5  2216.9   722.4 2225.38
#Mann= 5 ,-1,0
       0      .1       0     329    .045       0  412.31      .1       0
  483.03     .06       0  613.03      .1       0
#XS Ineff= 2 , 0
                           456.3         2166.38
Permanent Ineff=
       F       F
Bank Sta=329,412.31
XS Rating Curve= 0 ,0
Exp/Cntr(USF)=0,0
Exp/Cntr=0.3,0.1

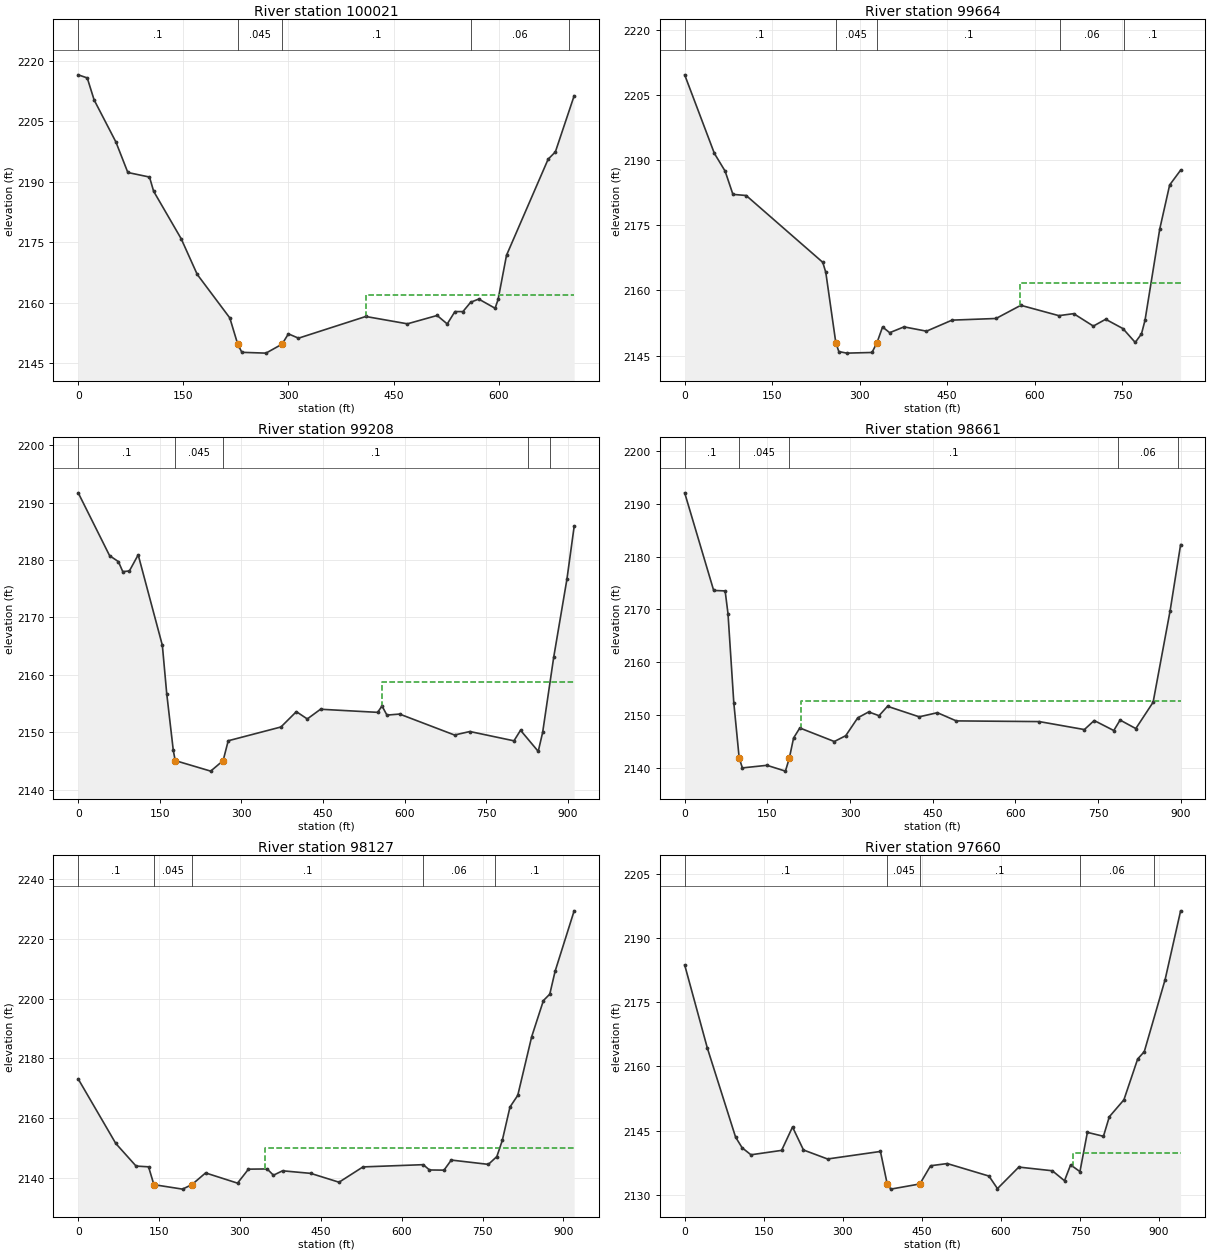
Type RM Length L Ch R = 1 ,100021  ,357.5,357.5,357.5
XS GIS Cut Line= 2
2242662.95342781649742.2618834492243169.95358014650235.919926511
#Sta/Elev= 30
       0 2216.52    12.9 2215.75    22.7 2210.29    53.8 2199.85    70.8 2192.29
   101.7 2191.16   107.6 2187.64   146.9 2175.86   169.8 2167.01   216.3 2156.21
  227.572149.707   233.5 2147.68   267.9 2147.48  290.822149.704   299.9 2152.26
   314.3 2151.19   410.3 2156.57   469.7 2154.75   512.1 2156.82   526.5 2154.72
   537.5 2157.79   548.9 2157.78     560 2160.11   571.5 2160.89   594.8 2158.61
   599.1  2160.8   611.1 2171.76   670.5  2195.6   680.8  2197.4   707.6 2211.32
#Mann= 5 ,-1,0
       0      .1       0  227.57    .045       0  290.82      .1       0
     560     .06       0     700      .1       0
#XS Ineff= 2 , 0
                          410.18         2161.81
Permanent Ineff=
       F       F
Bank Sta=227.57,290.82
XS Rating Curve= 0 ,0
Exp/Cntr(USF)=0,0
Exp/Cntr=0.3,0.1

Type RM Length L Ch R = 1 ,99664   ,455.4,455.4,455.4
XS GIS Cut Line= 3
2242368.77318287649979.9820091172242818.51834618650366.912963399
2243061.91867063650448.694442102
#Sta/Elev= 30
       0 2209.59    50.9 2191.52    69.3 2187.44    82.7 2182.09   105.4 2181.83
   236.7 2166.46   241.9 2164.14  259.012148.012   264.2 2145.93   277.8 2145.57
   321.1 2145.72  329.722148.009   339.2 2151.59   351.4 2150.27     376 2151.61
   414.5 2150.62   458.3 2153.16   533.7 2153.54   576.2 2156.57   641.4 2154.19
   666.8 2154.65   700.5 2151.79   721.6 2153.36   751.2 2151.22   772.3 2148.03
     783 2149.99   789.1 2153.15   814.3  2174.1   831.3 2184.25   850.1 2187.66
#Mann= 5 ,-1,0
       0      .1       0  259.01    .045       0  329.72      .1       0
  643.28     .06       0  753.28      .1       0
#XS Ineff= 2 , 0
                          575.47         2161.81
Permanent Ineff=
       F       F
Bank Sta=259.01,329.72
XS Rating Curve= 0 ,0
Exp/Cntr(USF)=0,0
Exp/Cntr=0.3,0.1

Type RM Length L Ch R = 1 ,99208   ,547.6,547.6,547.6
XS GIS Cut Line= 3
2242142.99295801650516.5303802652242903.23015108 650618.93058298
2243045.19858749650594.447493206
#Sta/Elev= 30
       0  2191.7    57.7 2180.75    73.8 2179.72    81.9 2177.97      94 2178.09
   110.2  2180.9   154.6 2165.13   162.6 2156.74   174.7 2146.82  178.242145.056
   243.4 2143.22  266.272145.053   275.6 2148.51   372.5 2150.91   400.8 2153.58
   420.9 2152.31   445.2    2154   550.1 2153.46   558.2 2154.57   567.2 2152.98
   590.5 2153.16   691.4 2149.51   719.6 2150.12   800.6  2148.5   812.7 2150.34
   845.2 2146.66   853.3 2149.95   873.6 2163.04     898  2176.7   911.2 2185.84
#Mann= 5 ,-1,0
       0      .1       0  178.24    .045       0  266.27      .1       0
   827.1     .06       0   867.1      .1       0
#XS Ineff= 2 , 0
                          557.38         2158.69
Permanent Ineff=
       F       F
Bank Sta=178.24,266.27
XS Rating Curve= 0 ,0
Exp/Cntr(USF)=0,0
Exp/Cntr=0.3,0.1

Type RM Length L Ch R = 1 ,98661   ,534.2,534.2,534.2
XS GIS Cut Line= 3
2242311.78787424 651135.087918572242638.50576077650862.477022071
2243065.29638642650655.647168446
#Sta/Elev= 30
       0 2192.06    52.6  2173.6    73.4 2173.51    78.6  2169.2    89.1 2152.39
   98.882141.913   104.7 2140.04   149.3 2140.53   182.8 2139.43  189.912141.916
   197.6  2145.7   208.9 2147.59   271.5 2145.03   292.2 2146.13     314 2149.51
   333.9 2150.63   352.6 2149.91     368 2151.69   425.5  2149.7   458.5 2150.48
   492.7 2148.93   643.3  2148.8   725.2 2147.29     743    2149   778.5 2147.11
     790 2149.09   818.5 2147.48   849.9 2152.46   880.8  2169.8   899.8 2182.27
#Mann= 5 ,-1,0
       0      .1       0   98.88    .045       0  189.91      .1       0
  785.51     .06       0  895.51      .1       0
#XS Ineff= 2 , 0
                          211.42         2152.69
Permanent Ineff=
       F       F
Bank Sta=98.88,189.91
XS Rating Curve= 0 ,0
Exp/Cntr(USF)=0,0
Exp/Cntr=0.3,0.1

Type RM Length L Ch R = 1 ,98127   ,466.6,466.6,466.6
XS GIS Cut Line= 3
2242718.63267196651535.9788756622243087.47832674 650962.01339283
2243280.95035995650824.077055869
#Sta/Elev= 30
       0  2173.1    69.7 2151.53   107.3 2143.97   130.5 2143.72  140.392137.752
   193.5 2136.26  210.732137.754   236.3 2141.68   295.5 2138.26   315.8 2142.94
   350.4 2143.01   362.1 2140.91     379 2142.39   431.3 2141.53   483.8 2138.57
   528.2 2143.69     640 2144.44   651.5 2142.67   678.5 2142.61     692 2145.98
   760.8 2144.54   776.5 2147.15   786.6 2152.54   800.9 2163.73   815.3 2167.62
   841.1 2187.22   862.9 2199.33   874.7 2201.47   884.5 2209.08   919.9 2229.33
#Mann= 5 ,-1,0
       0      .1       0  140.39    .045       0  210.73      .1       0
     640     .06       0  772.26      .1       0
#XS Ineff= 2 , 0
                          345.96            2150
Permanent Ineff=
       F       F
Bank Sta=140.39,210.73
XS Rating Curve= 0 ,0
Exp/Cntr(USF)=0,0
Exp/Cntr=0.3,0.1

Type RM Length L Ch R = 1 ,97660   ,361.6,361.6,361.6
XS GIS Cut Line= 4
2242839.21095378651777.3208538192243184.89690238651679.945939369
2243237.84178044651582.5273637322243577.93451701651256.808553146
#Sta/Elev= 30
       0 2183.68      43 2164.27    96.6 2143.46     109 2140.98   125.7 2139.34
   183.9 2140.37   204.6 2145.83   225.4 2140.46   271.1 2138.36   371.4 2140.12
   384.2 2132.56   391.1 2131.32   446.2 2132.53   466.5 2136.78   498.1 2137.29
   577.3 2134.37   593.4 2131.44   633.9 2136.47   697.5 2135.61   720.6 2133.28
   732.2 2136.99   749.9 2135.41     764 2144.58   794.5 2143.66   805.6 2148.22
   833.3 2152.18   859.4 2161.71     872 2163.44   911.5 2180.27   940.9 2196.32
#Mann= 5 ,-1,0
       0      .1       0   384.2    .045       0   446.2      .1       0
  750.01     .06       0  890.01      .1       0
#XS Ineff= 2 , 0
                          736.57         2139.76
Permanent Ineff=
       F       F
Bank Sta=384.2,446.2
XS Rating Curve= 0 ,0
Exp/Cntr(USF)=0,0
Exp/Cntr=0.3,0.1

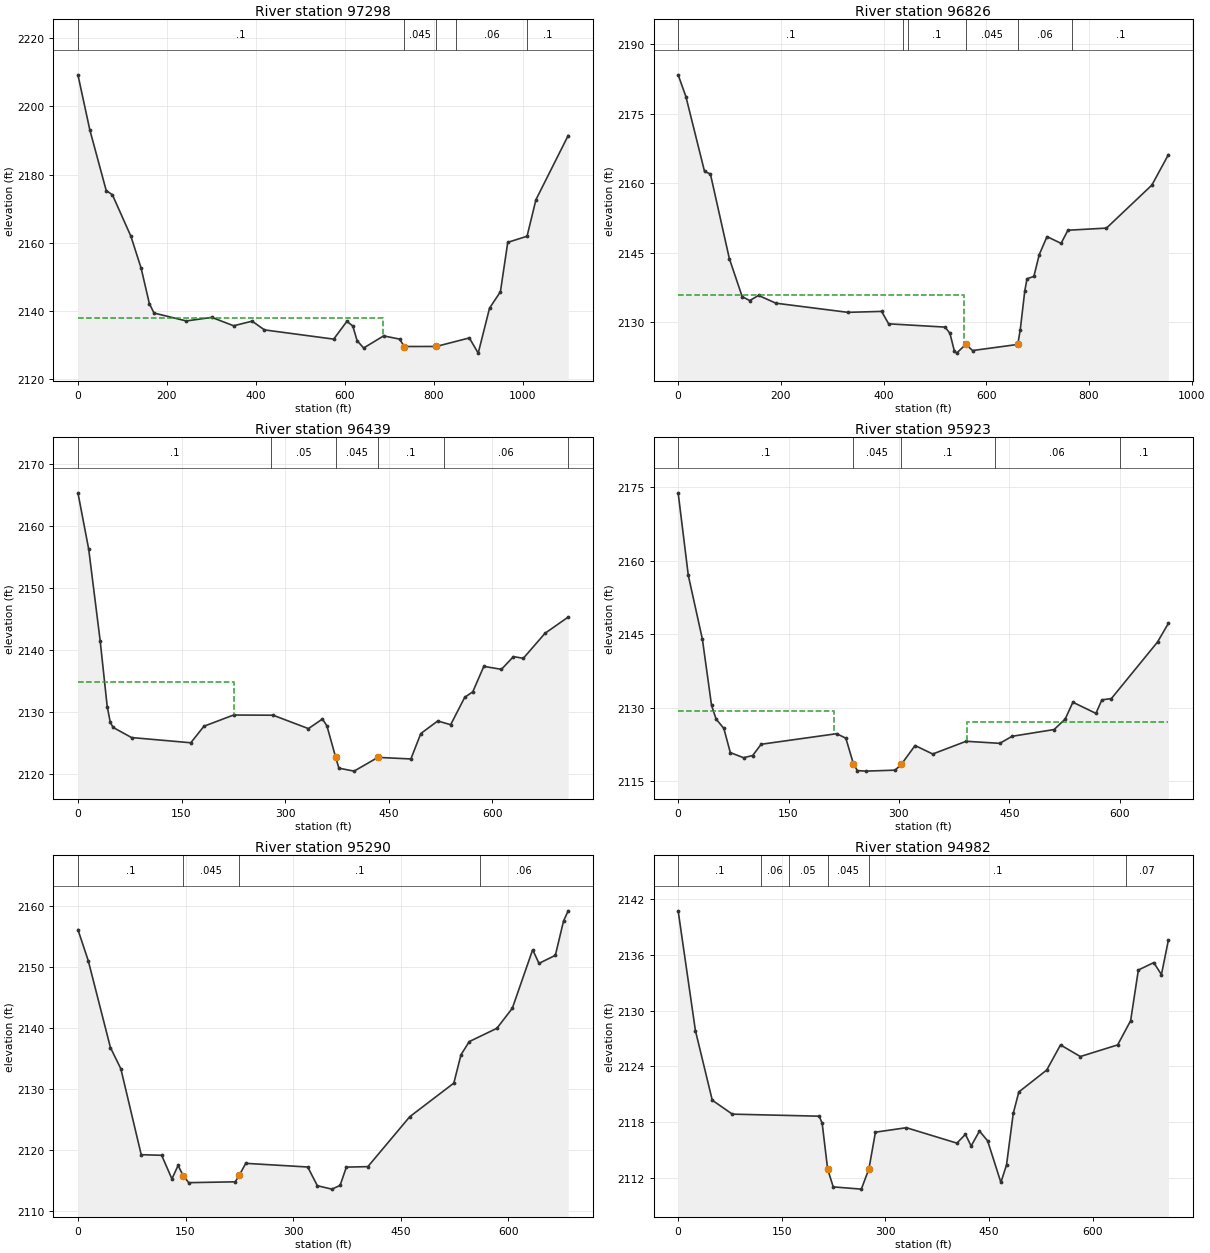
Type RM Length L Ch R = 1 ,97298   ,472.1,472.1,472.1
XS GIS Cut Line= 4
2243177.44200793652424.249348486 2243534.3330976651807.013646721
2243568.21781956651694.7705052262243786.25708078651531.827743571
#Sta/Elev= 30
       0 2209.28    26.6  2193.2    63.6 2175.32    77.5 2174.08   119.1 2161.91
   142.2  2152.5   160.6 2142.15   171.1 2139.38   243.8 2137.05   301.1  2138.1
   350.1 2135.64   391.7 2136.99   419.4 2134.43   575.1 2131.72   604.8 2136.93
   618.1 2135.57   627.8 2131.25   642.5 2129.12   687.4 2132.67   723.3 2131.73
  733.832129.553   805.8 2129.57   880.1 2132.07   900.1 2127.61   925.6 2140.82
     950 2145.62   966.5 2160.12  1009.9 2161.91  1029.9 2172.64  1102.4 2191.47
#Mann= 5 ,-1,0
       0      .1       0  733.83    .045       0   805.8      .1       0
  850.23     .06       0 1010.23      .1       0
#XS Ineff= 2 , 0
          685.13 2137.96
Permanent Ineff=
       F       F
Bank Sta=733.83,805.8
XS Rating Curve= 0 ,0
Exp/Cntr(USF)=0,0
Exp/Cntr=0.3,0.1

Type RM Length L Ch R = 1 ,96826   ,387.8,387.8,387.8
XS GIS Cut Line= 3
2243327.26500053652456.7151474312243499.13103677652251.951732013
2244121.38141104651959.890347345
#Sta/Elev= 30
       0 2183.38    15.1 2178.68    51.4 2162.51    62.8 2161.97    99.7  2143.7
   124.7 2135.48   139.4 2134.63   156.5 2135.74   190.5 2134.06   330.3 2132.09
   396.2 2132.29   409.9 2129.61   519.8  2128.9   529.2 2127.58   537.8 2123.78
   542.4 2123.28   560.1 2125.17   573.4 2123.84  661.322125.155   666.2 2128.32
     675  2136.7   679.4 2139.35   692.7 2139.84   703.2 2144.56   718.3 2148.45
   745.7 2146.98     759 2149.82   834.1 2150.28   922.5 2159.57   954.7 2166.14
#Mann= 6 ,-1,0
       0      .1       0  437.33     .05       0  447.33      .1       0
   560.1    .045       0  661.32     .06       0  767.33      .1       0
#XS Ineff= 2 , 0
          557.38 2135.92
Permanent Ineff=
       F       F
Bank Sta=560.1,661.32
XS Rating Curve= 0 ,0
Exp/Cntr(USF)=0,0
Exp/Cntr=0.3,0.1

Type RM Length L Ch R = 1 ,96439   ,515.4,515.4,515.4
XS GIS Cut Line= 2
 2243619.0922337652658.6755345922244214.64275968652272.602715273
#Sta/Elev= 30
       0  2165.3    15.6 2156.22    32.2 2141.46    42.4 2130.85    46.9  2128.3
      51  2127.5    77.6 2125.87   163.4 2125.03   182.4 2127.69   225.3  2129.5
   282.5 2129.47   333.7 2127.31     354 2128.86   360.5 2127.74   373.22122.667
   377.8 2120.94   399.8 2120.46  434.282122.677     482 2122.42   496.4 2126.52
   520.9 2128.54   539.6 2127.94     560 2132.36   571.6 2133.24   587.6 2137.34
   613.1 2136.86   630.5 2138.91   644.8 2138.64   676.2 2142.67   709.7 2145.28
#Mann= 6 ,-1,0
       0      .1       0     280     .05       0   373.2    .045       0
  434.28      .1       0     530     .06       0  709.74      .1       0
#XS Ineff= 2 , 0
          225.66 2134.82
Permanent Ineff=
       F       F
Bank Sta=373.2,434.28
XS Rating Curve= 0 ,0
Exp/Cntr(USF)=0,0
Exp/Cntr=0.3,0.1

Type RM Length L Ch R = 1 ,95923   ,633.2,633.2,633.2
XS GIS Cut Line= 2
2244013.91664064653054.4357455482244523.47958206652625.129403068
#Sta/Elev= 30
       0 2173.89    13.8 2157.02      33 2143.94    45.4 2130.45    51.6 2127.66
    62.1 2125.75    70.9 2120.81    88.9 2119.76   101.3 2120.21   112.8 2122.51
   215.4 2124.67   227.9 2123.75   238.3 2118.47   243.6 2117.13   255.1 2117.02
   294.9 2117.22   303.4 2118.42     322 2122.25     346 2120.52   391.4 2123.12
   437.1  2122.7   453.9 2124.14     511 2125.52     526 2127.66   536.5  2131.1
   567.8 2128.82   575.9 2131.58   588.8 2131.85   651.5  2143.4   666.3 2147.23
#Mann= 5 ,-1,0
       0      .1       0   238.3    .045       0   303.4      .1       0
     430     .06       0     600      .1       0
#XS Ineff= 2 , 0
          212.49 2129.26  392.54         2127.06
Permanent Ineff=
       F       F
Bank Sta=238.3,303.4
XS Rating Curve= 0 ,0
Exp/Cntr(USF)=0,0
Exp/Cntr=0.3,0.1

Type RM Length L Ch R = 1 ,95290   ,308.3,308.3,308.3
XS GIS Cut Line= 2
2244440.54887624653496.9599017232244987.80019917653087.833223232
#Sta/Elev= 30
       0 2156.13    14.5 2150.99    45.3 2136.78    59.8 2133.31    88.2 2119.21
   116.7 2119.11     131 2115.24   139.6 2117.44   146.6 2115.79   154.4 2114.62
   219.3 2114.76   224.92115.845   233.9 2117.79   320.3 2117.19   333.7 2114.12
   353.9 2113.56   365.4 2114.17   374.1 2117.17   404.1 2117.25   462.5 2125.44
   523.9 2130.95   533.9  2135.6   545.4 2137.76   583.9 2139.94   605.4 2143.22
   633.8 2152.83   642.6 2150.59   665.4 2151.91   676.9 2157.57   683.3 2159.21
#Mann= 4 ,-1,0
       0      .1       0   146.6    .045       0   224.9      .1       0
     560     .06       0
Bank Sta=146.6,224.9
XS Rating Curve= 0 ,0
Exp/Cntr(USF)=0,0
Exp/Cntr=0.3,0.1

Type RM Length L Ch R = 1 ,94982   ,278.7,278.7,278.7
XS GIS Cut Line= 3
2244519.59859301653684.2858109952245048.17517795653583.966891103
2245171.41653157653464.449964023
#Sta/Elev= 30
       0 2140.75      25 2127.86    49.4 2120.37    78.4 2118.87   204.2 2118.65
   208.5 2117.89   216.4 2112.96   224.5 2111.04   265.2  2110.8  276.182112.985
   285.6 2116.93   330.4 2117.41   403.5 2115.75   415.9  2116.7   424.1 2115.44
   436.2 2117.05     448    2116   467.2 2111.52   475.4 2113.42   485.1 2118.95
   493.2 2121.26   533.6 2123.62   553.5 2126.32   582.2 2125.07   636.2 2126.32
     655 2128.92   666.2 2134.38   688.5 2135.18   699.6 2133.89   709.7 2137.61
#Mann= 6 ,-1,0
       0      .1       0     120     .06       0     160     .05       0
   216.4    .045       0  276.18      .1       0  648.01     .07       0
Bank Sta=216.4,276.18
XS Rating Curve= 0 ,0
Exp/Cntr(USF)=0,0
Exp/Cntr=0.3,0.1

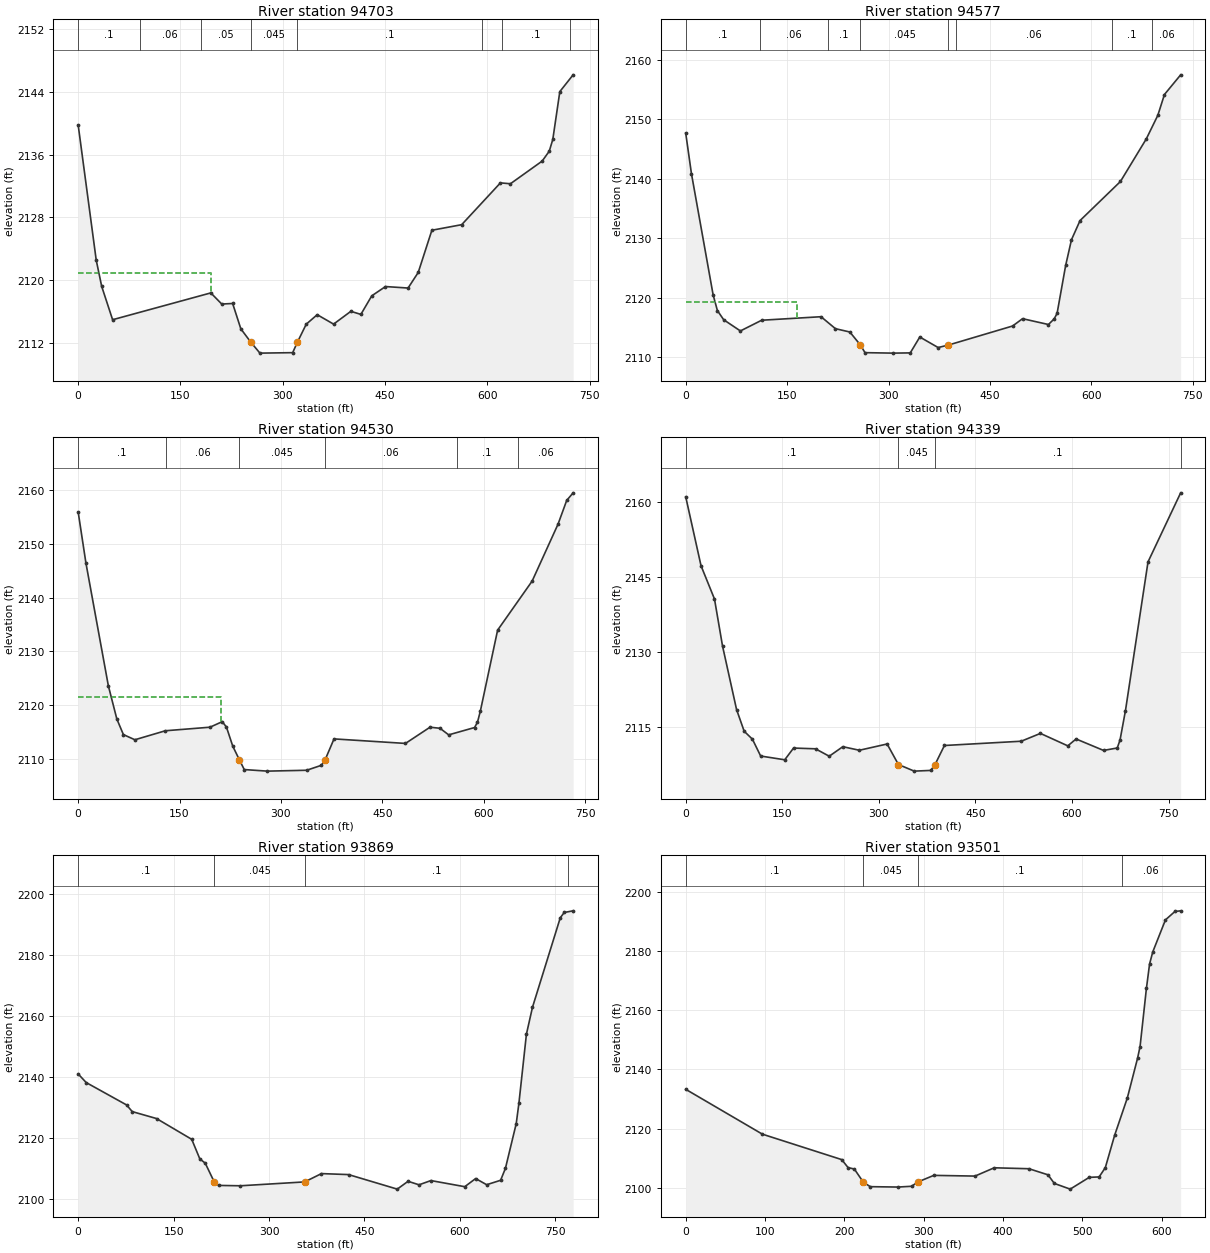
Type RM Length L Ch R = 1 ,94703   ,126.1,126.1,126.1
XS GIS Cut Line= 3
2244553.69944452653887.131611048 2245084.9900218653896.898303783
2245235.25140316654020.131146127
#Sta/Elev= 30
       0 2139.79    26.5 2122.54    34.5  2119.2    50.5 2114.95   194.5 2118.37
   210.5 2116.95   226.5 2117.02   238.5 2113.79   253.1 2112.09   266.5 2110.69
   314.5 2110.75  321.582112.106   334.4 2114.38   350.5 2115.59   374.5 2114.39
   399.8 2116.02   414.5 2115.63   430.5    2118   450.6 2119.18   483.7 2118.99
   498.6 2120.98   518.6 2126.36   562.3 2127.07   619.1  2132.4   633.8 2132.29
   680.3 2135.18   690.7 2136.44   695.9 2137.94   706.2 2144.04   725.7 2146.18
#Mann= 8 ,-1,0
       0      .1       0      90     .06       0     180     .05       0
   253.1    .045       0  321.58      .1       0  591.38     .06       0
  621.38      .1       0  721.38     .06       0
#XS Ineff= 2 , 0
          195.36 2120.85
Permanent Ineff=
       F       F
Bank Sta=253.1,321.58
XS Rating Curve= 0 ,0
Exp/Cntr(USF)=0,0
Exp/Cntr=0.3,0.1

Type RM Length L Ch R = 1 ,94577   ,46.8,46.8,46.8
XS GIS Cut Line= 2
2244540.15143233653913.0792965072245227.93419001654164.287137308
#Sta/Elev= 30
       0 2147.65     8.5 2140.82    40.6 2120.43    46.9 2117.81    56.2 2116.27
    80.9 2114.39   112.4 2116.19   200.2 2116.78   221.5 2114.77   242.8 2114.21
  258.482112.021   265.2 2110.74   306.6 2110.66   332.2  2110.7   346.3 2113.37
   373.4  2111.6  388.752112.022   483.6 2115.22   498.3 2116.45   536.6 2115.47
   545.1 2116.42   549.4 2117.35   562.1 2125.42   570.7 2129.73   583.4 2132.95
   643.1 2139.51   681.4 2146.68   698.4 2150.63   708.2 2154.13   732.2 2157.44
#Mann= 8 ,-1,0
       0      .1       0     110     .06       0     210      .1       0
  258.48    .045       0  388.75      .1       0     400     .06       0
     630      .1       0     690     .06       0
#XS Ineff= 2 , 0
          164.61 2119.23
Permanent Ineff=
       F       F
Bank Sta=258.48,388.75
XS Rating Curve= 0 ,0
Exp/Cntr(USF)=0,0
Exp/Cntr=0.3,0.1

Type RM Length L Ch R = 1 ,94530   ,191,191,191
XS GIS Cut Line= 2
2244517.36039839653954.6096250272245205.14315606654205.817465828
#Sta/Elev= 30
       0 2155.89    11.5  2146.4    44.7 2123.61    57.2 2117.48    66.9 2114.58
    83.9 2113.62     129 2115.29     195 2115.95   213.2 2116.98   219.4 2115.96
   228.7 2112.43  238.422109.917   245.7 2108.09   279.8  2107.8     338 2107.96
   359.8 2108.88  365.372109.917   378.5 2113.78   484.2 2112.94   520.5 2115.95
   535.3 2115.75   548.1 2114.53   586.4 2115.89   590.7 2116.87   594.9  2118.9
   620.5 2133.96   671.6 2143.07   709.9 2153.63   722.7 2158.03   732.2 2159.44
#Mann= 6 ,-1,0
       0      .1       0     130     .06       0  238.42    .045       0
  365.37     .06       0     560      .1       0     650     .06       0
#XS Ineff= 2 , 0
          211.19 2121.63
Permanent Ineff=
       F       F
Bank Sta=238.42,365.37
XS Rating Curve= 0 ,0
Exp/Cntr(USF)=0,0
Exp/Cntr=0.3,0.1

Type RM Length L Ch R = 1 ,94339   ,470.2,470.2,470.2
XS GIS Cut Line= 2
2244406.94255763654116.9970793692245128.62830115654381.745152274
#Sta/Elev= 30
       0 2160.98    23.8 2147.22    44.7 2140.59    57.2 2131.21      79 2118.55
    90.8 2114.23   103.6 2112.65   116.4 2109.29   153.8 2108.54   167.5 2110.88
   201.6 2110.73   222.9 2109.25     244 2111.15   269.7 2110.44   312.8 2111.69
  330.352107.598   354.9 2106.28   380.5 2106.42     3872107.531   401.8 2111.39
   521.1 2112.24   550.9  2113.8   593.4 2111.32   606.3 2112.69   648.9 2110.41
   670.2 2110.89   674.5 2112.46     683 2118.36     718 2147.99   768.7 2161.76
#Mann= 4 ,-1,0
       0      .1       0  330.35    .045       0     387      .1       0
  768.71     .06       0
Bank Sta=330.35,387
XS Rating Curve= 0 ,0
Exp/Cntr(USF)=0,0
Exp/Cntr=0.3,0.1

Type RM Length L Ch R = 1 ,93869   ,367.6,367.6,367.6
XS GIS Cut Line= 2
 2244288.2199106654575.9348529722245020.32130312 654838.89186833
#Sta/Elev= 30
       0 2140.93    12.7  2138.1      76 2130.77      85 2128.57   123.2 2126.29
   178.5 2119.47   191.2 2113.05   199.7 2111.65  213.842105.496     221 2104.34
     255 2104.22     356 2105.49   382.4 2108.22     425 2107.89   501.5 2103.12
   518.5 2105.69   535.7 2104.54   554.4 2105.93   607.6 2103.92   624.7 2106.59
     642 2104.57   663.9 2106.02   671.5 2109.93   688.5 2124.65   692.7 2131.32
   704.5 2153.99     714 2162.81   757.7  2192.2   763.9 2193.95   777.9 2194.49
#Mann= 4 ,-1,0
       0      .1       0  213.84    .045       0     356      .1       0
     770     .06       0
Bank Sta=213.84,356
XS Rating Curve= 0 ,0
Exp/Cntr(USF)=0,0
Exp/Cntr=0.3,0.1

Type RM Length L Ch R = 1 ,93501   ,486.8,486.8,486.8
XS GIS Cut Line= 2
2244283.50193785655019.4922914882244907.38512199655035.360680776
#Sta/Elev= 30
       0 2133.27    96.7 2118.13   196.7 2109.55   204.7 2106.87   212.7 2106.35
   223.92101.952   232.7 2100.42   267.6 2100.29   284.8 2100.55   292.8 2102.01
   312.8 2104.23   364.8 2103.99     389 2106.79   432.8 2106.47   456.8 2104.42
   464.8 2101.51   484.8 2099.59   508.8 2103.56   521.3 2103.71   529.1 2106.84
   540.8 2117.72   556.9  2130.4   569.7  2143.7   572.9 2147.69   580.9 2167.28
   584.9 2175.54   588.9 2179.61   604.9 2190.42   616.9 2193.27   624.1 2193.48
#Mann= 4 ,-1,0
       0      .1       0   223.9    .045       0   292.8      .1       0
     550     .06       0
Bank Sta=223.9,292.8
XS Rating Curve= 0 ,0
Exp/Cntr(USF)=0,0
Exp/Cntr=0.3,0.1

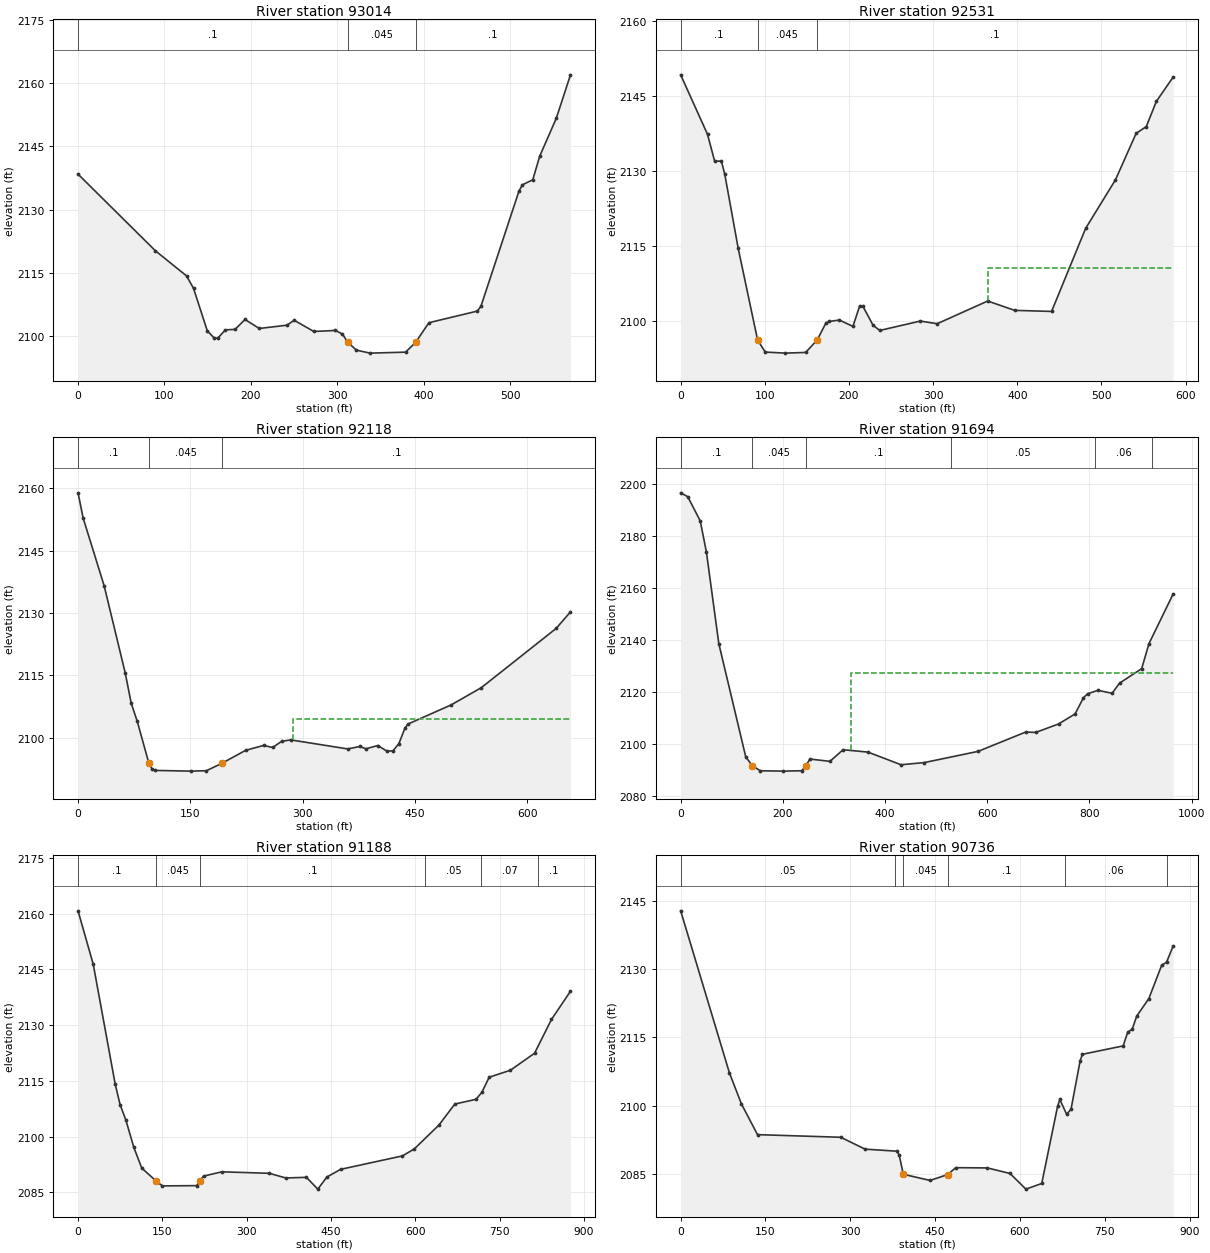
Type RM Length L Ch R = 1 ,93014   ,483.6,483.6,483.6
XS GIS Cut Line= 2
2244226.80588238655490.6989660672244795.64376408655522.987779993
#Sta/Elev= 30
       0  2138.4    89.5 2120.22   125.6 2114.25   133.6 2111.31   149.6  2101.2
   157.6 2099.51   161.6 2099.47   170.5 2101.45   181.7 2101.56   193.2 2103.92
   209.7 2101.78   241.8 2102.56   250.1 2103.73   272.8 2101.07   297.8 2101.31
   305.9 2100.46   312.22098.474   322.1 2096.64   337.9 2095.93     379 2096.16
  390.562098.472     406 2103.15   462.1 2105.91   466.2 2107.06   510.2 2134.38
   514.2 2135.87   526.2 2137.08   534.2 2142.67   553.4 2151.66   569.8 2161.97
#Mann= 3 ,-1,0
       0      .1       0   312.2    .045       0  390.56      .1       0
Bank Sta=312.2,390.56
XS Rating Curve= 0 ,0
Exp/Cntr(USF)=0,0
Exp/Cntr=0.3,0.1

Type RM Length L Ch R = 1 ,92531   ,412.7,412.7,412.7
XS GIS Cut Line= 2
2244215.88339426655935.510846028 2244800.0040425655900.551293745
#Sta/Elev= 30
       0 2149.22    31.9 2137.32    40.4 2131.95    48.4 2131.97    52.4 2129.36
    68.4 2114.49   91.422096.193   100.5 2093.77   124.5 2093.56   148.6  2093.7
  162.262096.195   172.6 2099.57   176.6 2099.89   188.6 2100.18   204.7  2098.9
   212.7 2102.98   216.7 2102.89   228.7 2099.12   236.7  2098.1   284.8 2099.97
   304.8 2099.44   364.9 2103.98     397 2102.11   440.8  2101.9   481.2 2118.49
   516.7 2128.22   541.3 2137.52   553.3 2138.86   565.3  2143.9   585.2 2148.76
#Mann= 3 ,-1,0
       0      .1       0   91.42    .045       0  162.26      .1       0
#XS Ineff= 1 ,-1
  365.03585.1659 2110.58
Permanent Ineff=
       F
Bank Sta=91.42,162.26
XS Rating Curve= 0 ,0
Exp/Cntr(USF)=0,0
Exp/Cntr=0.3,0.1

Type RM Length L Ch R = 1 ,92118   ,423.7,423.7,423.7
XS GIS Cut Line= 3
2244237.43152471656349.7894204632244719.63119657656307.933543236
2244864.23517145656212.233149265
#Sta/Elev= 30
       0  2158.9     6.8 2152.84    34.9 2136.51      63 2115.56      71 2108.27
      79 2103.95   94.542093.862    99.1 2092.39   103.1 2092.12   150.9 2091.95
   171.4 2092.05  192.392093.863   223.6 2096.94   247.7 2098.13   259.7 2097.64
   271.8 2099.11   283.8 2099.47   360.1 2097.29   376.2 2097.88   384.2 2097.32
   400.2 2098.11   412.3 2096.76   420.3 2096.82   428.3 2098.56   436.4 2102.28
   440.4 2103.27   497.9 2107.86   538.3 2112.02   638.2 2126.27   657.4 2130.26
#Mann= 3 ,-1,0
       0      .1       0   94.54    .045       0  192.39      .1       0
#XS Ineff= 2 , 0
                          287.28         2104.51
Permanent Ineff=
       F       F
Bank Sta=94.54,192.39
XS Rating Curve= 0 ,0
Exp/Cntr(USF)=0,0
Exp/Cntr=0.3,0.1

Type RM Length L Ch R = 1 ,91694   ,506.3,506.3,506.3
XS GIS Cut Line= 3
2244234.42506452656790.9439748372245046.27733075656657.838587499
2245162.24376483656577.664952656
#Sta/Elev= 30
       0 2196.72    13.9 2195.23    38.3 2185.91    50.4 2173.93    74.7 2138.63
   127.4 2095.06  140.362091.628   155.8 2089.72   200.4 2089.58   236.9 2089.72
   244.82091.627   253.1 2094.23   292.1 2093.34   317.9 2097.82   366.6  2096.9
   431.4 2092.03   476.7 2092.87   581.8 2097.17   675.2 2104.62   694.9 2104.48
   739.5 2107.73   771.9  2111.6   788.1 2117.79   796.2 2119.35   816.5 2120.67
   844.4 2119.56     859 2123.47   902.2 2129.04   916.5 2138.67   963.7 2157.76
#Mann= 6 ,-1,0
       0      .1       0  140.36    .045       0   244.8      .1       0
     530     .05       0     810     .06       0  922.69      .1       0
#XS Ineff= 2 , 0
                          333.33         2127.49
Permanent Ineff=
       F       F
Bank Sta=140.36,244.8
XS Rating Curve= 0 ,0
Exp/Cntr(USF)=0,0
Exp/Cntr=0.3,0.1

Type RM Length L Ch R = 1 ,91188   ,452.5,452.5,452.5
XS GIS Cut Line= 4
2244335.24605185657228.0511803012244434.53841053 657270.02291286
2245064.09536661 657155.090171562245183.63120495657202.130048163
#Sta/Elev= 30
       0 2160.79    27.1 2146.37    66.1 2114.15    74.8 2108.62    85.1 2104.48
    99.2 2097.14   113.5 2091.52  139.162088.035   150.1 2086.75   211.1 2086.82
   216.5 2088.03   223.3 2089.38   255.8 2090.54   340.3 2090.14   369.7 2088.88
   406.3 2089.06   426.6 2085.88   442.9 2089.15   467.3 2091.21   577.1 2094.82
   598.2 2096.69   642.1 2103.12   670.4 2108.78   708.2 2110.06   718.5 2111.93
   731.6 2116.01   769.3 2117.88   812.3 2122.46   842.4 2131.56   876.2 2139.14
#Mann= 6 ,-1,0
       0      .1       0  139.16    .045       0   216.5      .1       0
   617.8     .05       0   717.8     .07       0  817.76      .1       0
Bank Sta=139.16,216.5
XS Rating Curve= 0 ,0
Exp/Cntr(USF)=0,0
Exp/Cntr=0.3,0.1

Type RM Length L Ch R = 1 ,90736   ,459.5,459.5,459.5
XS GIS Cut Line= 3
2244187.25766014657608.6725262192244327.51884412 657704.24115754
2245028.40707704657689.643116404
#Sta/Elev= 30
       0 2142.81    86.1 2107.23   107.5 2100.34   135.9  2093.6   283.1 2093.02
   326.2 2090.41   382.4 2089.96   386.4 2089.14  393.672084.892     441 2083.53
   472.22084.823   486.4 2086.34   542.5 2086.28   582.5 2085.06   610.5 2081.62
   638.5 2082.86   666.5  2099.8   670.5 2101.34   682.5 2098.08   690.3 2099.19
   706.5 2109.89   710.5 2111.27   782.5 2113.11   790.5 2116.11   798.5 2116.79
   806.5 2119.67   827.9 2123.51   850.5 2130.81   859.2 2131.52   870.8 2135.04
#Mann= 6 ,-1,0
       0     .05       0  379.72      .1       0  393.67    .045       0
   472.2      .1       0  679.72     .06       0  859.72      .1       0
Bank Sta=393.67,472.2
XS Rating Curve= 0 ,0
Exp/Cntr(USF)=0,0
Exp/Cntr=0.3,0.1