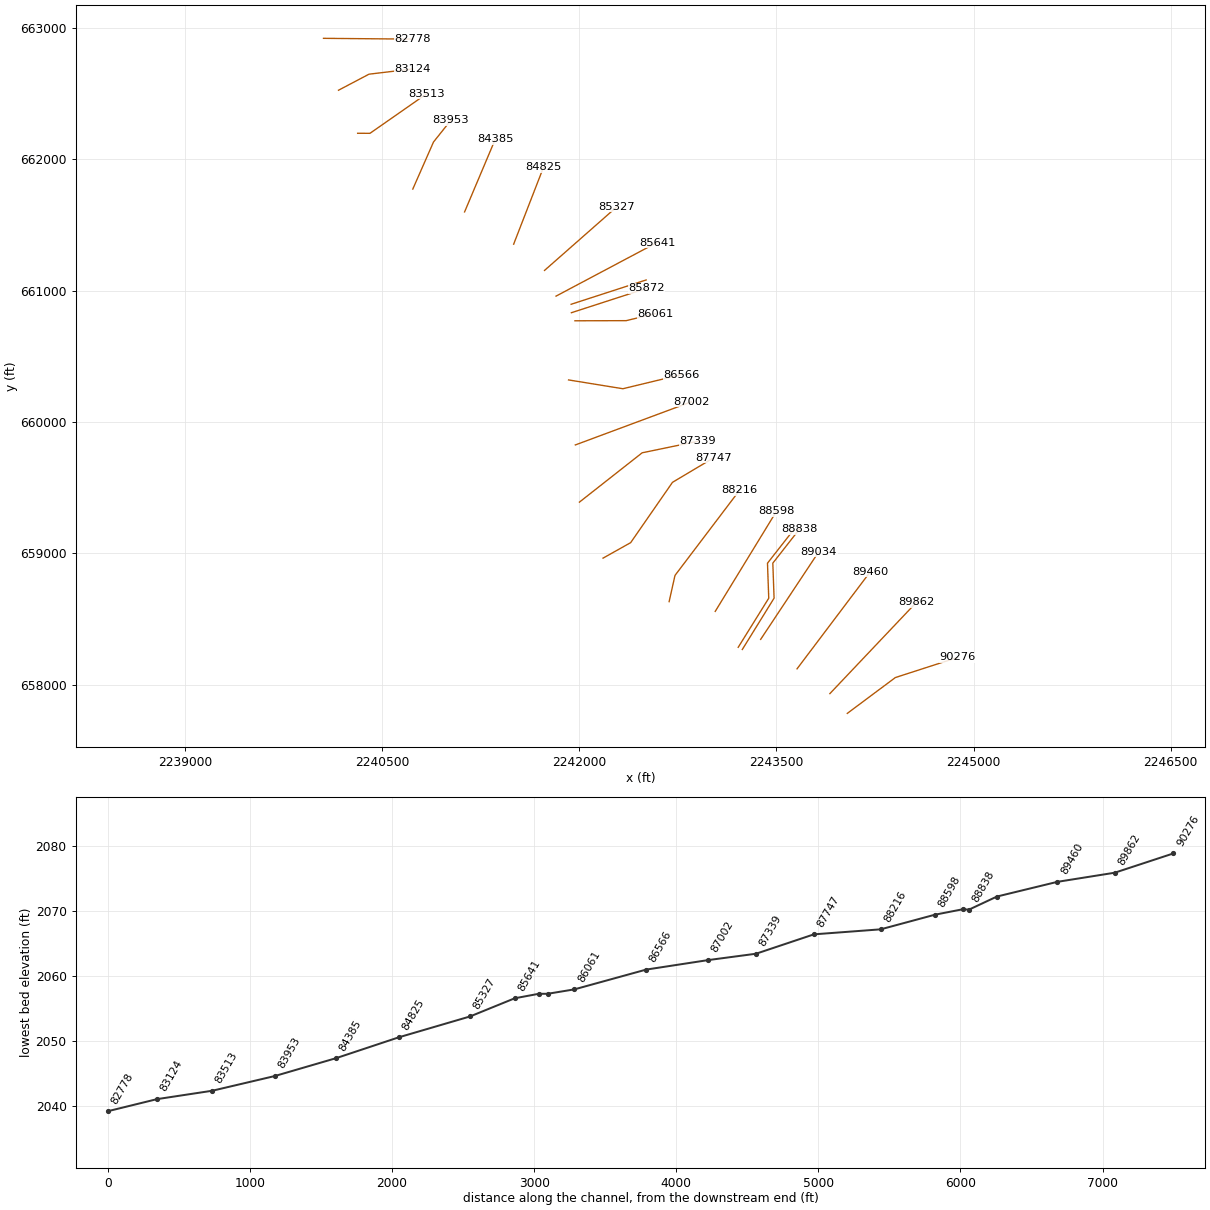
HEC-RAS study MIDFKRIV.prj: MIDFKRIV

--- MIDFKRIV.g01 (geometry) --- (continued)

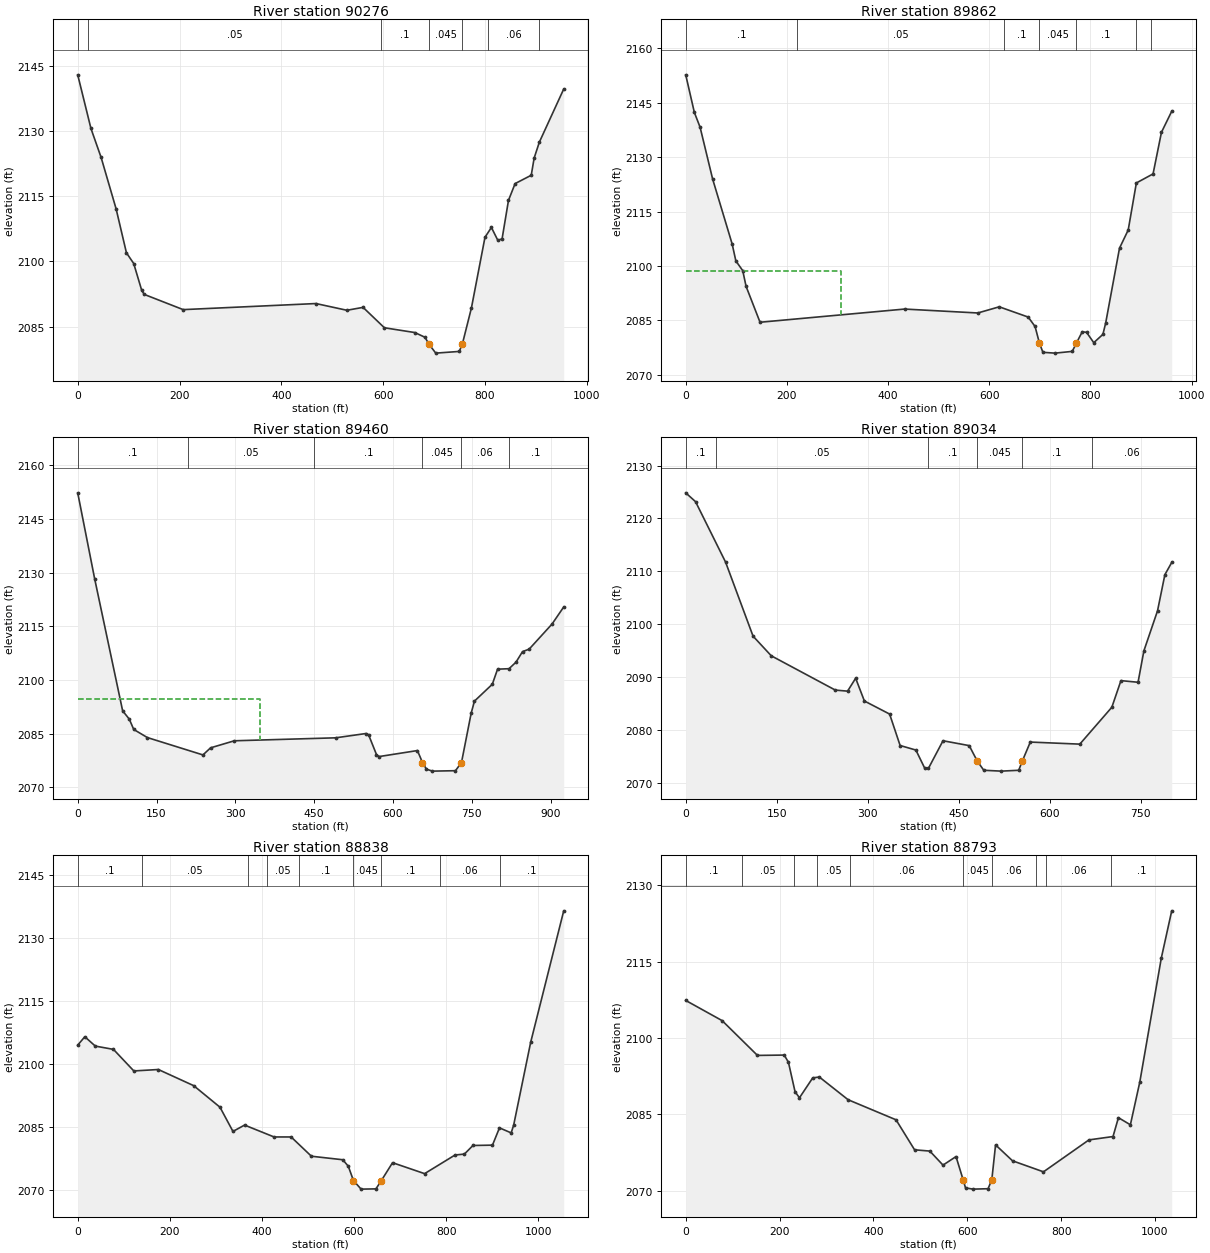
Type RM Length L Ch R = 1 ,90276   ,413.7,413.7,413.7
XS GIS Cut Line= 3
2244039.32200397657780.1094176812244405.07301921658052.968880385
2244879.43894353658206.205864934
#Sta/Elev= 30
       0 2142.99      26 2130.63      46 2123.95    75.4 2112.13    95.7    2102
     110 2099.53   125.8 2093.32   130.8 2092.41   207.2 2088.91     468 2090.31
   528.8 2088.76   560.6 2089.43   602.5 2084.73   662.3 2083.63   682.4 2082.53
  689.582081.021   703.4 2078.89   749.6 2079.28  755.732081.021   773.5 2089.31
   800.1 2105.57   812.7 2107.84   825.3 2104.88   833.7 2105.21   846.3 2114.09
   859.3 2117.94     891 2119.86   896.7 2123.82   906.9 2127.48   954.8 2139.72
#Mann= 7 ,-1,0
       0      .1       0      20     .05       0  596.32      .1       0
  689.58    .045       0  755.73      .1       0  806.32     .06       0
  906.32      .1       0
Bank Sta=689.58,755.73
XS Rating Curve= 0 ,0
Exp/Cntr(USF)=0,0
Exp/Cntr=0.3,0.1

Type RM Length L Ch R = 1 ,89862   ,402.9,402.9,402.9
XS GIS Cut Line= 2
2243906.69058463657930.5564280852244567.32599917658627.977891695
#Sta/Elev= 30
       0 2152.72    17.1 2142.33    28.4 2138.27    53.2 2123.96    91.8 2106.03
    99.1 2101.37   112.7 2098.68   119.3 2094.35   146.9 2084.44   432.6 2088.08
   577.3    2087   619.7  2088.7   676.9 2085.87   690.5 2083.27  699.052078.718
     706 2076.14   730.1 2075.92     764  2076.4  772.252078.717   783.8 2081.83
   792.3 2081.65   806.5  2078.8   824.6  2081.1   830.1 2084.26   857.4 2104.89
   874.6  2109.9   890.7 2122.88   923.7 2125.38   940.3 2136.86   960.6 2142.66
#Mann= 7 ,-1,0
       0      .1       0     220     .05       0     630      .1       0
  699.05    .045       0  772.25      .1       0     890     .06       0
     920      .1       0
#XS Ineff= 2 , 0
          306.95 2098.69
Permanent Ineff=
       F       F
Bank Sta=699.05,772.25
XS Rating Curve= 0 ,0
Exp/Cntr(USF)=0,0
Exp/Cntr=0.3,0.1

Type RM Length L Ch R = 1 ,89460   ,425.4,425.4,425.4
XS GIS Cut Line= 2
2243656.70025804658119.3103401062244213.49457448658857.656914538
#Sta/Elev= 30
       0 2152.31    32.3 2128.24    85.5 2091.37    98.1 2089.06   106.6 2086.17
   132.6  2083.9   238.3 2079.05   252.8 2081.03     298    2083   490.7 2083.83
   548.4 2085.03   553.4 2084.71   568.5 2079.15   573.5 2078.59   646.4 2080.27
  656.062076.922   663.5 2075.07     675 2074.52   718.8 2074.64  730.262076.926
   748.8  2090.8     755  2094.1   788.9  2098.8   798.9 2103.02   820.7 2103.15
     834 2104.98   846.4 2107.93     859 2108.61   902.6 2115.64   924.8 2120.41
#Mann= 6 ,-1,0
       0      .1       0     210     .05       0     450      .1       0
  656.06    .045       0  730.26     .06       0     820      .1       0
#XS Ineff= 2 , 0
          345.96  2094.8
Permanent Ineff=
       F       F
Bank Sta=656.06,730.26
XS Rating Curve= 0 ,0
Exp/Cntr(USF)=0,0
Exp/Cntr=0.3,0.1

Type RM Length L Ch R = 1 ,89034   ,196.5,196.5,196.5
XS GIS Cut Line= 2
2243379.87124731658343.6633769792243822.39861121659011.458216974
#Sta/Elev= 30
       0 2124.84    16.2 2123.17    65.7 2111.75     111 2097.76     141 2094.05
   246.6 2087.57   266.8 2087.37   280.1 2089.81   294.5 2085.51   336.1 2083.04
   353.4  2077.1   379.4 2076.24   393.8 2072.85   400.1 2072.79   424.1    2078
   467.3 2077.08   480.4 2074.19   491.3 2072.42   520.1 2072.26   548.9 2072.42
  554.712074.136     568 2077.75   649.6 2077.36   702.4 2084.33   717.4 2089.36
   745.6 2089.05   755.2 2094.98   777.7 2102.55   789.8 2109.37   801.1 2111.69
#Mann= 6 ,-1,0
       0      .1       0      50     .05       0     400      .1       0
   480.4    .045       0  554.71      .1       0     670     .06       0
Bank Sta=480.4,554.71
XS Rating Curve= 0 ,0
Exp/Cntr(USF)=0,0
Exp/Cntr=0.3,0.1

Type RM Length L Ch R = 1 ,88838   ,45,45,45
XS GIS Cut Line= 4
2243240.07472421  658266.52145452243481.92370387658657.460000038
2243472.39362582658924.3021854762243674.98627414659182.978605639
#Sta/Elev= 30
       0 2104.56    15.4 2106.56    38.2 2104.33    77.6 2103.55   121.8 2098.41
   175.1 2098.75   251.9  2094.9   308.9 2089.77   337.1    2084   362.3 2085.51
   426.4 2082.68   463.4 2082.68   507.4 2078.09   575.5 2077.25   587.5 2075.71
   598.7  2072.3   615.3 2070.25   647.5 2070.31  658.862072.208   683.6 2076.55
   753.2 2073.94   819.3 2078.38   839.6  2078.6   858.2 2080.65   900.6 2080.73
   915.8 2084.85   941.2 2083.65   946.6  2085.5   983.6 2105.27  1055.3 2136.56
#Mann= 9 ,-1,0
       0      .1       0     140     .05       0     370     .06       0
     410     .05       0   479.7      .1       0   598.7    .045       0
  658.86      .1       0  786.71     .06       0  916.71      .1       0
Bank Sta=598.7,658.86
XS Rating Curve= 0 ,0
Exp/Cntr(USF)=0,0
Exp/Cntr=0.3,0.1

Type RM Length L Ch R = 1 ,88793   ,194.4,194.4,194.4
XS GIS Cut Line= 4
2243209.01046488658283.3020708592243441.32936649658657.086475905
2243431.79928844658923.9286613432243634.39193676659182.605081506
#Sta/Elev= 30
       0  2107.4    77.6 2103.43   152.9 2096.59   209.9 2096.66   218.9 2095.24
     233 2089.45   242.4 2088.26   270.7 2092.18   284.8 2092.34     346 2087.88
   448.2 2083.93   487.7 2078.03   520.2 2077.78   548.3 2075.02     576  2076.7
  591.312072.105   596.3 2070.54   612.3  2070.3   644.3 2070.38   652.3 2072.14
   660.3    2079   696.4 2075.87   762.4  2073.7   859.3 2079.98   910.6 2080.64
   922.1 2084.35   947.6 2082.95   967.6 2091.33  1013.5 2115.73  1035.7 2125.02
#Mann= 10 ,-1,0
       0      .1       0     120     .05       0     230     .06       0
     280     .05       0     350     .06       0  591.31    .045       0
   652.3     .06       0  747.11      .1       0  767.11     .06       0
  907.11      .1       0
Bank Sta=591.31,652.3
XS Rating Curve= 0 ,0
Exp/Cntr(USF)=0,0
Exp/Cntr=0.3,0.1

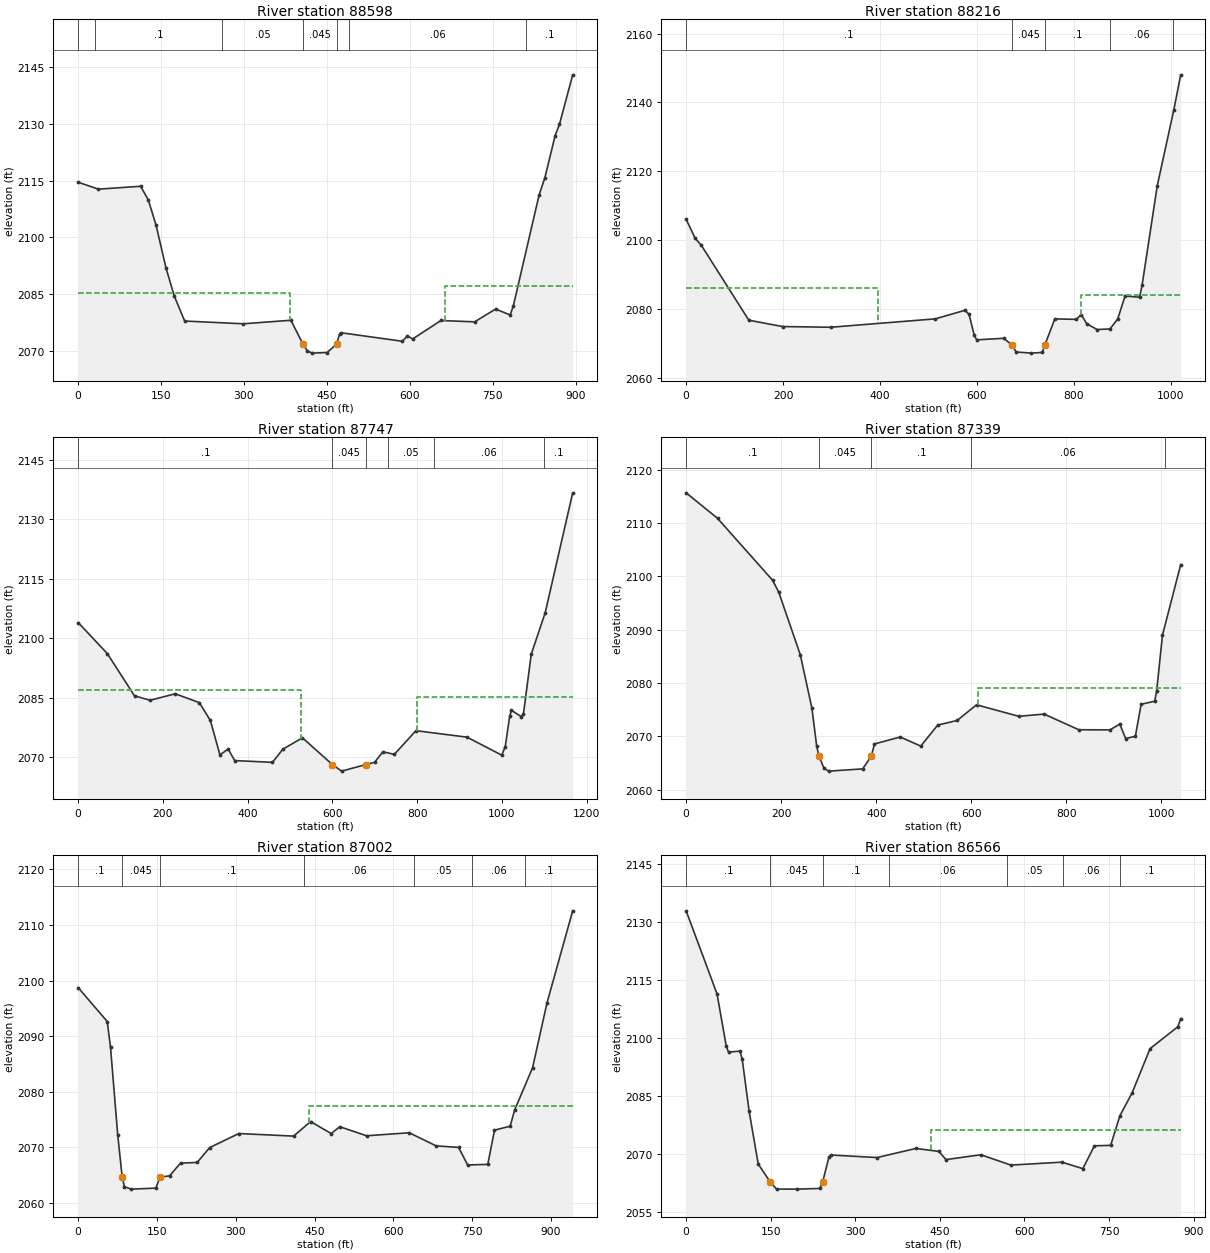
Type RM Length L Ch R = 1 ,88598   ,382.2,382.2,382.2
XS GIS Cut Line= 2
2243034.09665099658556.8019400162243500.68927238659320.161191931
#Sta/Elev= 30
       0 2114.56    36.7 2112.73     113 2113.49   126.9  2109.9   141.1 2103.15
   158.9 2091.95   173.9 2084.54   192.7 2077.94   298.6 2077.21   384.9 2078.14
  406.662071.868   414.9 2070.01   423.7 2069.47   450.5 2069.63  467.562071.867
   473.1 2074.56     476 2074.84   586.4  2072.6   595.8 2074.01   605.2 2073.21
   656.4 2078.08   717.3 2077.72   755.2 2081.09   781.6 2079.55   787.4 2081.97
   833.9 2111.18   844.3  2115.7     863 2126.88   870.7 2129.79   894.7 2142.89
#Mann= 7 ,-1,0
       0     .05       0      30      .1       0     260     .05       0
  406.66    .045       0  467.56      .1       0     490     .06       0
     810      .1       0
#XS Ineff= 2 ,-1
       0  383.85 2085.43  663.02894.6653 2087.07
Permanent Ineff=
       F       F
Bank Sta=406.66,467.56
XS Rating Curve= 0 ,0
Exp/Cntr(USF)=0,0
Exp/Cntr=0.3,0.1

Type RM Length L Ch R = 1 ,88216   ,469.5,469.5,469.5
XS GIS Cut Line= 3
2242683.21347544658631.0105679792242727.77928217658830.623249376
2243220.32463615659480.715860443
#Sta/Elev= 30
       0 2106.09    18.6 2100.56    30.9 2098.62   129.3 2076.78   198.9 2074.94
   298.1 2074.73   513.9 2077.17     575 2079.65   583.5 2078.51   594.2 2072.46
   599.2 2071.08   654.9 2071.52  672.782069.527   680.6 2067.55     712 2067.22
   734.7 2067.42   739.7 2069.52   760.5 2077.16   804.9 2077.02     815 2078.43
   826.2 2075.76   847.7 2074.07   874.2 2074.24   890.2 2077.13   905.3 2083.79
   935.4 2083.46   940.5 2086.96   971.8 2115.84  1005.7  2137.7  1020.1 2148.02
#Mann= 5 ,-1,0
       0      .1       0  672.78    .045       0   739.7      .1       0
  874.53     .06       0 1004.53      .1       0
#XS Ineff= 2 , 0
           394.8 2086.13   814.7         2083.99
Permanent Ineff=
       F       F
Bank Sta=672.78,739.7
XS Rating Curve= 0 ,0
Exp/Cntr(USF)=0,0
Exp/Cntr=0.3,0.1

Type RM Length L Ch R = 1 ,87747   ,407.5,407.5,407.5
XS GIS Cut Line= 4
2242180.22858777658962.3591357712242390.41451915659080.311294322
2242708.71912606659539.6610563982243023.96974318659727.474588227
#Sta/Elev= 30
       0 2103.93    68.7 2096.11     133 2085.44   169.7 2084.32   229.3 2085.96
   285.9 2083.72   311.9 2079.24   334.5 2070.56     354 2072.01   369.4 2069.11
   458.5 2068.67   482.9 2071.98   529.2 2074.85   599.8 2068.11   621.7 2066.45
  678.892068.109   699.5 2068.67     719 2071.32     746 2070.68   796.9 2076.65
   917.3 2075.02   999.5 2070.48  1007.7 2072.66  1018.1 2080.23  1022.3 2081.78
    1046 2080.17  1050.7 2080.93    1069 2095.93  1101.9 2106.38  1166.8 2136.64
#Mann= 6 ,-1,0
       0      .1       0   599.8    .045       0  678.89      .1       0
  731.02     .05       0  839.88     .06       0 1099.88      .1       0
#XS Ineff= 2 , 0
           526.4 2086.93  800.45         2085.03
Permanent Ineff=
       F       F
Bank Sta=599.8,678.89
XS Rating Curve= 0 ,0
Exp/Cntr(USF)=0,0
Exp/Cntr=0.3,0.1

Type RM Length L Ch R = 1 ,87339   ,337.5,337.5,337.5
XS GIS Cut Line= 3
 2242000.2330903 659388.703348972242478.09123722 659764.57089841
2242901.68649969659852.277128799
#Sta/Elev= 30
       0 2115.67    66.1 2110.88   181.9 2099.27   194.9 2097.01   240.2 2085.29
   264.6 2075.28   274.7 2068.14  279.462066.259     290 2064.01   300.2 2063.47
   371.4 2063.89  389.572066.258   396.2 2068.57   450.4 2069.87   493.6 2068.17
   529.2  2072.1   570.1 2072.97     611 2075.91     700 2073.75   753.1 2074.17
   826.2 2071.23   891.9 2071.21   912.4 2072.29   924.6 2069.58   945.1    2070
   957.3 2076.01   985.9 2076.59     990 2078.56  1002.2 2088.98  1040.5  2102.2
#Mann= 5 ,-1,0
       0      .1       0  279.46    .045       0  389.57      .1       0
     600     .06       0 1007.97      .1       0
#XS Ineff= 2 , 0
                          613.91         2079.07
Permanent Ineff=
       F       F
Bank Sta=279.46,389.57
XS Rating Curve= 0 ,0
Exp/Cntr(USF)=0,0
Exp/Cntr=0.3,0.1

Type RM Length L Ch R = 1 ,87002   ,435.7,435.7,435.7
XS GIS Cut Line= 2
2241969.58571947659824.5289210612242851.65023893660152.514102134
#Sta/Elev= 30
       0 2098.75    55.4 2092.64    61.6 2088.02    75.3 2072.25    83.8 2064.67
    88.1 2062.93   100.9 2062.49   147.9 2062.67  155.742064.659     174 2064.88
   194.8 2067.17   226.5 2067.29   250.3 2069.97   305.8 2072.49     410 2072.03
   442.3 2074.64   481.6 2072.49   497.8 2073.72     549 2072.09   630.1 2072.63
   681.3 2070.27     724    2070   741.1 2066.84   779.5 2066.94   792.3  2073.1
   822.1 2073.81   830.7 2076.74   864.8 2084.34   892.2 2095.99   941.1 2112.56
#Mann= 7 ,-1,0
       0      .1       0    83.8    .045       0  155.74      .1       0
     430     .06       0     640     .05       0     750     .06       0
     850      .1       0
#XS Ineff= 2 , 0
                           439.8         2077.49
Permanent Ineff=
       F       F
Bank Sta=83.8,155.74
XS Rating Curve= 0 ,0
Exp/Cntr(USF)=0,0
Exp/Cntr=0.3,0.1

Type RM Length L Ch R = 1 ,86566   ,505.2,505.2,505.2
XS GIS Cut Line= 3
2241917.95474636660319.5224880522242331.32803523 660252.51089464
2242776.96748926 660360.14282364
#Sta/Elev= 30
       0 2132.94    54.9 2111.42    71.1 2098.02    75.2 2096.44    95.5 2096.69
    99.5 2094.59   111.7 2081.16   127.9 2067.51  149.522062.794   160.3 2061.04
   196.8 2061.03   237.3 2061.21  241.982062.791   253.5 2069.46   257.5 2069.84
   338.7 2069.19   407.5 2071.54   448.4 2070.77   460.8 2068.66   522.8 2069.91
     576 2067.24   666.5    2068   703.6 2066.32   724.2 2072.22     753 2072.34
   769.4 2080.01   791.2 2085.96   822.9 2097.34   872.3    2103   877.2  2105.1
#Mann= 7 ,-1,0
       0      .1       0  149.52    .045       0  241.98      .1       0
     360     .06       0  568.77     .05       0  668.77     .06       0
  768.77      .1       0
#XS Ineff= 2 , 0
                          434.71         2076.38
Permanent Ineff=
       F       F
Bank Sta=149.52,241.98
XS Rating Curve= 0 ,0
Exp/Cntr(USF)=0,0
Exp/Cntr=0.3,0.1

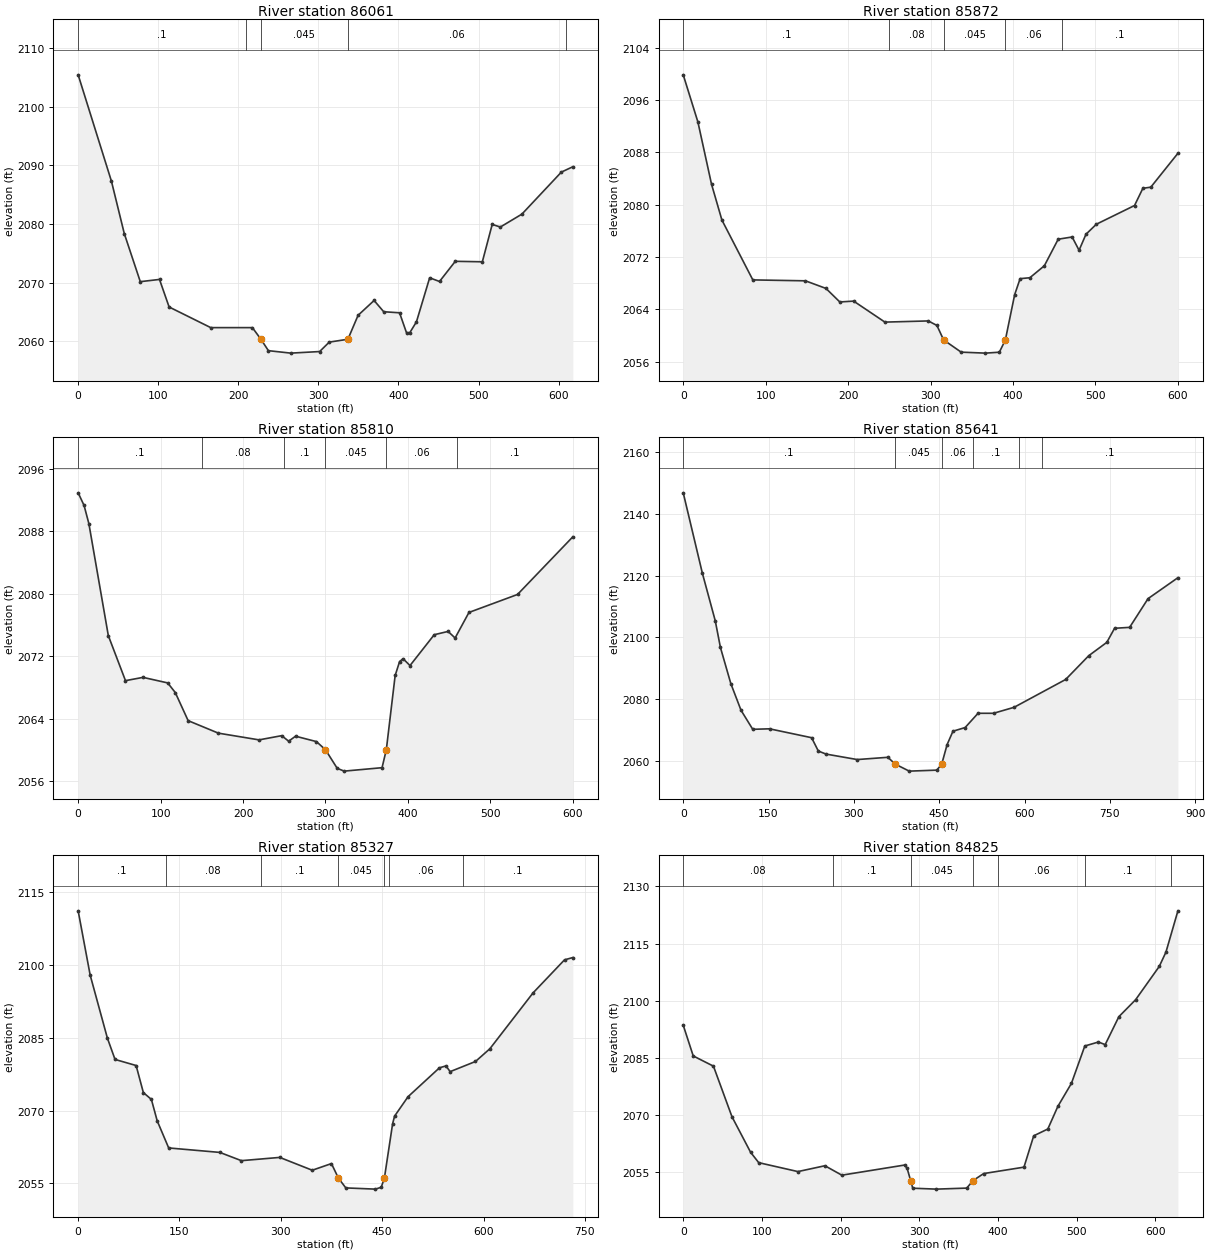
Type RM Length L Ch R = 1 ,86061   ,188.8,188.8,188.8
XS GIS Cut Line= 3
2241966.60295854660769.9705739042242356.10623816660770.947140634
2242578.03312621660824.484368525
#Sta/Elev= 30
       0 2105.46    41.6  2087.3    57.6 2078.39    77.6 2070.18   101.6 2070.56
   113.6 2065.86   165.6 2062.34   217.6 2062.34   228.2 2060.37   237.6 2058.41
   265.6 2057.99   301.6 2058.26   313.6 2059.87  336.892060.354   349.6 2064.44
   369.6 2066.97   381.6 2065.05   401.4 2064.87   410.1 2061.46   414.3  2061.5
   422.5 2063.33     439 2070.84   451.3 2070.21     471 2073.65   504.8 2073.57
   517.1 2079.94   527.3  2079.5   554.2  2081.7   603.5 2088.87   617.8 2089.78
#Mann= 5 ,-1,0
       0      .1       0     210     .08       0   228.2    .045       0
  336.89     .06       0   609.5      .1       0
Bank Sta=228.2,336.89
XS Rating Curve= 0 ,0
Exp/Cntr(USF)=0,0
Exp/Cntr=0.3,0.1

Type RM Length L Ch R = 1 ,85872   ,61.8,61.8,61.8
XS GIS Cut Line= 2
2241939.52074227660831.458746807 2242510.2444641661016.592302215
#Sta/Elev= 30
       0 2099.84    17.8 2092.63    34.3 2083.13    46.9 2077.65    84.4  2068.5
   148.2 2068.36   173.1  2067.2   189.9 2065.13   206.7 2065.26   244.6 2062.05
   297.2 2062.23   307.7 2061.54   315.8 2059.33   337.1 2057.46   366.5 2057.31
   383.4 2057.45  390.692059.309     402 2066.25   408.6 2068.69   420.4 2068.83
     438 2070.66   454.8 2074.72   471.7 2075.06   480.1 2073.03   488.5 2075.48
   501.1 2077.01   547.4 2079.87   557.5  2082.5   567.1 2082.67     600 2087.85
#Mann= 5 ,-1,0
       0      .1       0     250     .08       0   315.8    .045       0
  390.69     .06       0     460      .1       0
Bank Sta=315.8,390.69
XS Rating Curve= 0 ,0
Exp/Cntr(USF)=0,0
Exp/Cntr=0.3,0.1

Type RM Length L Ch R = 1 ,85810   ,169.1,169.1,169.1
XS GIS Cut Line= 2
2241937.32328453660895.6661425012242508.04700636661080.799697909
#Sta/Elev= 30
       0 2092.93     7.2 2091.31      13 2088.99    36.6 2074.65    57.4 2068.89
    78.7 2069.31   108.6  2068.6   117.8 2067.37   133.4 2063.77   170.1 2062.17
   219.4 2061.31   246.9 2061.85   255.3 2061.14   263.7 2061.78     289 2061.09
  299.982060.048   314.2 2057.67   322.6 2057.31   368.6 2057.75  373.792060.053
   384.5 2069.55   389.9 2071.34   394.1  2071.7   402.5 2070.82   431.9 2074.77
   448.7 2075.19   457.2 2074.35     474 2077.62   532.9 2079.92     600  2087.3
#Mann= 6 ,-1,0
       0      .1       0     150     .08       0     250      .1       0
  299.98    .045       0  373.79     .06       0     460      .1       0
Bank Sta=299.98,373.79
XS Rating Curve= 0 ,0
Exp/Cntr(USF)=0,0
Exp/Cntr=0.3,0.1

Type RM Length L Ch R = 1 ,85641   ,313.9,313.9,313.9
XS GIS Cut Line= 2
2241822.42186729660957.7366704412242590.54615823661365.624011039
#Sta/Elev= 30
       0 2146.79    33.7  2120.7    56.3 2105.33    65.4 2096.68    83.7 2084.96
   101.6 2076.34   122.2 2070.17   151.7 2070.33   225.7 2067.45   237.5 2063.13
   251.1 2062.14   305.9 2060.37   359.8  2061.1  372.582058.909   397.3 2056.62
   445.8 2056.94   454.52058.911   463.9 2065.21   474.2 2069.55   495.6 2070.74
   518.3 2075.36   545.5 2075.36   581.7  2077.3   672.3 2086.31     713 2094.03
   744.7 2098.34   758.3  2102.9   784.8  2103.2   817.2 2112.51   869.7 2119.29
#Mann= 6 ,-1,0
       0      .1       0  372.58    .045       0   454.5     .06       0
     510      .1       0     590     .06       0     630      .1       0
Bank Sta=372.58,454.5
XS Rating Curve= 0 ,0
Exp/Cntr(USF)=0,0
Exp/Cntr=0.3,0.1

Type RM Length L Ch R = 1 ,85327   ,501.9,501.9,501.9
XS GIS Cut Line= 2
2241734.80755276661153.4402762962242284.36382367661637.295057026
#Sta/Elev= 30
       0 2111.13    17.8 2097.89    43.3 2084.91    54.6 2080.53    85.8 2079.28
    96.5 2073.71   108.4  2072.3     117 2067.89     134 2062.31   209.7 2061.39
   241.6 2059.69   298.4 2060.36   346.5 2057.72   374.9 2059.09  385.272056.087
   396.2 2054.08   440.1 2053.83   448.6 2054.22  453.262056.088   465.5 2067.33
   468.4 2068.87   488.3 2072.86   534.8 2078.81   544.4  2079.2   550.6 2078.02
   588.1 2080.11   609.4 2082.73   673.3 2094.23   719.9 2101.04   732.2 2101.51
#Mann= 7 ,-1,0
       0      .1       0     130     .08       0     270      .1       0
  385.27    .045       0  453.26      .1       0     460     .06       0
     570      .1       0
Bank Sta=385.27,453.26
XS Rating Curve= 0 ,0
Exp/Cntr(USF)=0,0
Exp/Cntr=0.3,0.1

Type RM Length L Ch R = 1 ,84825   ,440.6,440.6,440.6
XS GIS Cut Line= 2
2241499.86708766661353.3391600972241727.12108677661939.334709732
#Sta/Elev= 30
       0  2093.6    12.7 2085.54    38.4 2082.86    61.9 2069.61    85.6 2060.28
    95.9 2057.56   145.7 2055.22     180 2056.75   201.5 2054.28   281.4 2056.94
   284.5 2056.03  288.932052.867   291.6 2050.86   321.7 2050.62   360.2 2050.89
  368.182052.863   381.7  2054.7   432.9 2056.38   445.3  2064.6   463.2 2066.38
     476 2072.33   493.2 2078.35   510.2 2088.15   527.5 2089.19   536.1 2088.51
   553.5 2095.84   574.7 2100.27   604.8 2109.01   613.3 2112.77   628.5 2123.59
#Mann= 7 ,-1,0
       0     .08       0     190      .1       0  288.93    .045       0
  368.18      .1       0     400     .06       0     510      .1       0
     620     .06       0
Bank Sta=288.93,368.18
XS Rating Curve= 0 ,0
Exp/Cntr(USF)=0,0
Exp/Cntr=0.3,0.1

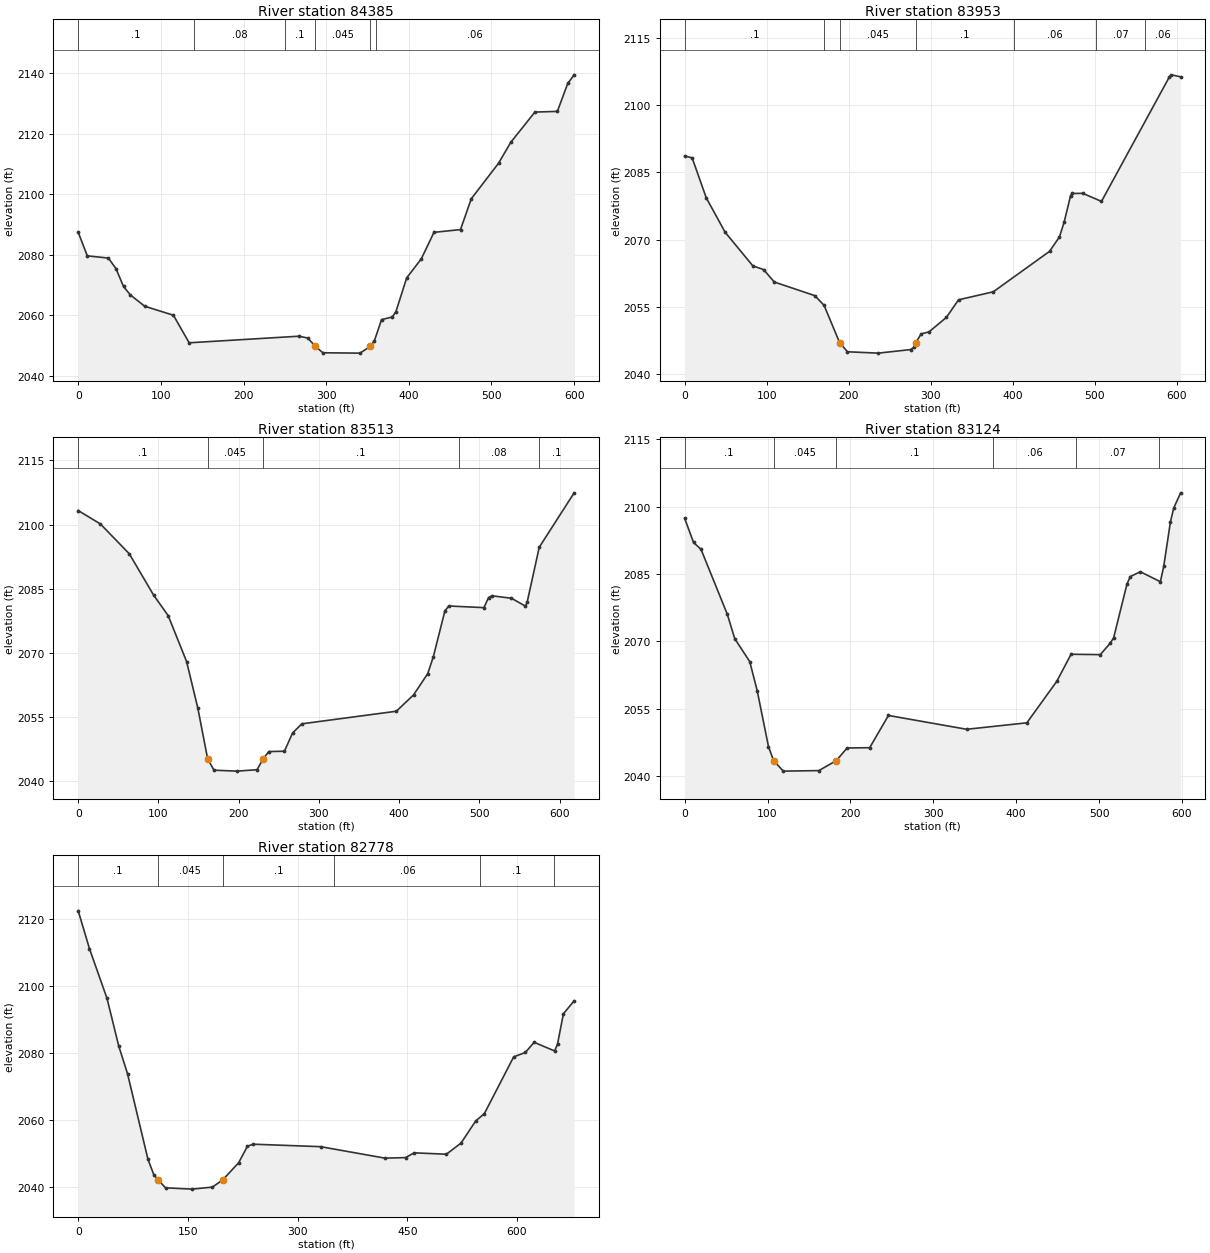
Type RM Length L Ch R = 1 ,84385   ,431.6,431.6,431.6
XS GIS Cut Line= 2
2241126.44108648661599.0667338652241359.73103412662151.855844044
#Sta/Elev= 30
       0  2087.4      11  2079.6    36.5 2078.87    45.7 2075.36    54.8 2069.47
    63.1 2066.68    80.4 2062.94   115.2 2059.95   134.2 2050.84   267.1 2053.02
   277.7 2052.41  286.882049.664     296 2047.54   340.9 2047.42  353.472049.663
   358.3 2051.49     367 2058.51     380 2059.38   384.4 2061.17   397.4 2072.32
   415.1 2078.62   430.4 2087.38   462.5 2088.29   475.5 2098.47   508.6 2110.27
   523.3 2117.16   552.5 2127.17   579.7 2127.39   592.2 2136.63     600 2139.49
#Mann= 6 ,-1,0
       0      .1       0     140     .08       0     250      .1       0
  286.88    .045       0  353.47      .1       0     360     .06       0
Bank Sta=286.88,353.47
XS Rating Curve= 0 ,0
Exp/Cntr(USF)=0,0
Exp/Cntr=0.3,0.1

Type RM Length L Ch R = 1 ,83953   ,439.8,439.8,439.8
XS GIS Cut Line= 3
2240732.28562249661773.0858000692240889.90371642662131.599545099
2241022.88885325662298.014140198
#Sta/Elev= 30
       0 2088.65     9.1 2088.22    26.3 2079.31    49.4 2071.61    83.1 2064.14
    96.2  2063.3   109.3 2060.53   158.7 2057.49     170 2055.32  188.882047.025
   198.5 2044.97   236.1 2044.67   275.4 2045.46   279.8 2045.98  281.852047.025
   288.3 2048.96   297.9 2049.41   319.1 2052.64   333.9 2056.56   376.3 2058.35
   444.9 2067.37     457 2070.59   462.7  2073.9   470.5 2079.77   472.2 2080.28
   485.4 2080.31   508.2 2078.51   590.7 2106.18   593.3 2106.74   604.7 2106.29
#Mann= 7 ,-1,0
       0      .1       0     170     .08       0  188.88    .045       0
  281.85      .1       0  401.63     .06       0  501.63     .07       0
  561.63     .06       0
Bank Sta=188.88,281.85
XS Rating Curve= 0 ,0
Exp/Cntr(USF)=0,0
Exp/Cntr=0.3,0.1

Type RM Length L Ch R = 1 ,83513   ,389,389,389
XS GIS Cut Line= 3
2240312.48874047662197.9468257052240406.47741649662197.657797262
 2240836.2830352662497.671224523
#Sta/Elev= 30
       0 2103.28    27.7 2100.14    63.7 2093.17      94 2083.52   112.1 2078.74
   135.1    2068   149.1 2057.11   161.32045.291   169.2 2042.63     198 2042.41
   222.9 2042.74  230.532045.289   237.5 2046.98     257 2047.06   267.2 2051.33
   278.7 2053.46   396.5  2056.4     418 2060.23   435.6 2065.18   442.6 2069.13
     457 2079.84   461.9 2080.99   505.7  2080.6   511.4 2082.96   515.6 2083.37
     540 2082.79   557.4 2080.95   559.5 2081.86   574.6 2094.71   618.1 2107.42
#Mann= 5 ,-1,0
       0      .1       0   161.3    .045       0  230.53      .1       0
  473.99     .08       0  573.99      .1       0
Bank Sta=161.3,230.53
XS Rating Curve= 0 ,0
Exp/Cntr(USF)=0,0
Exp/Cntr=0.3,0.1

Type RM Length L Ch R = 1 ,83124   ,346.4,346.4,346.4
XS GIS Cut Line= 3
2240166.73709848662525.7052294542240398.97079693662648.054971103
2240732.40143632662687.828671855
#Sta/Elev= 30
       0 2097.43    10.7 2092.05    19.7 2090.53    51.4 2076.07    60.4 2070.64
    78.5 2065.51    87.5 2059.03   101.1 2046.59  107.222043.467     119 2041.12
   161.9 2041.24  182.932043.467     196 2046.28   223.2 2046.34   245.8 2053.52
   340.2 2050.44   412.8 2051.88     449 2061.15   466.1 2067.15   501.4 2067.07
   513.5 2069.65   517.5 2070.82   533.6  2082.8   537.6 2084.46   549.7 2085.53
   573.9 2083.31   577.9  2086.7     586 2096.63     590 2099.73   598.3 2103.11
#Mann= 6 ,-1,0
       0      .1       0  107.22    .045       0  182.93      .1       0
  372.49     .06       0  472.49     .07       0  572.49      .1       0
Bank Sta=107.22,182.93
XS Rating Curve= 0 ,0
Exp/Cntr(USF)=0,0
Exp/Cntr=0.3,0.1

Type RM Length L Ch R = 1 ,82778   ,290.6,290.6,290.6
XS GIS Cut Line= 2
2240052.76106369662921.0206193872240730.81294675662915.007953607
#Sta/Elev= 30
       0 2122.51    15.4 2111.18    39.4  2096.3    55.4 2082.07    67.4  2073.8
    95.4 2048.16   103.4 2043.56  109.412041.977   119.4 2039.65   155.4 2039.26
   183.4 2039.86  197.342041.978   219.4 2047.16   231.4 2052.11   239.4  2052.7
   331.4 2051.96   419.4 2048.53   447.6 2048.69   459.4 2050.12   503.4  2049.7
   523.4 2053.03   543.4 2059.63   555.4 2061.87   595.4 2078.82   611.4 2080.14
   623.4 2083.18   651.4 2080.59   655.4 2082.68   663.4 2091.73   678.1 2095.58
#Mann= 6 ,-1,0
       0      .1       0  109.41    .045       0  197.34      .1       0
     350     .06       0     550      .1       0     650     .06       0
Bank Sta=109.41,197.34
XS Rating Curve= 0 ,0
Exp/Cntr(USF)=0,0
Exp/Cntr=0.3,0.1