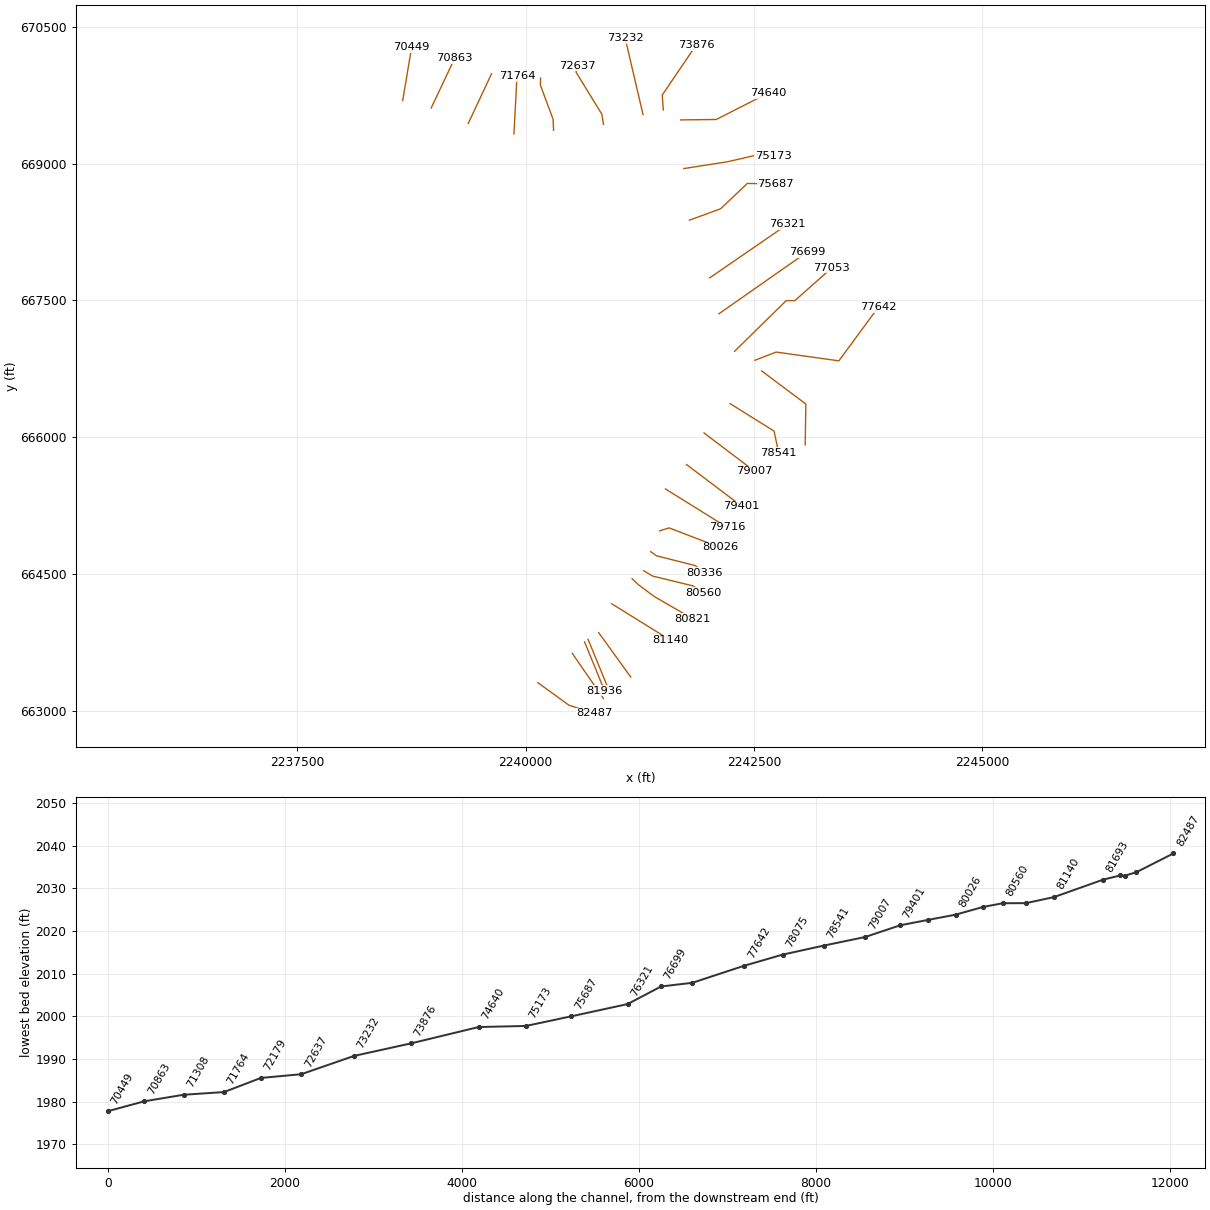
HEC-RAS study MIDFKRIV.prj: MIDFKRIV

--- MIDFKRIV.g01 (geometry) --- (continued)

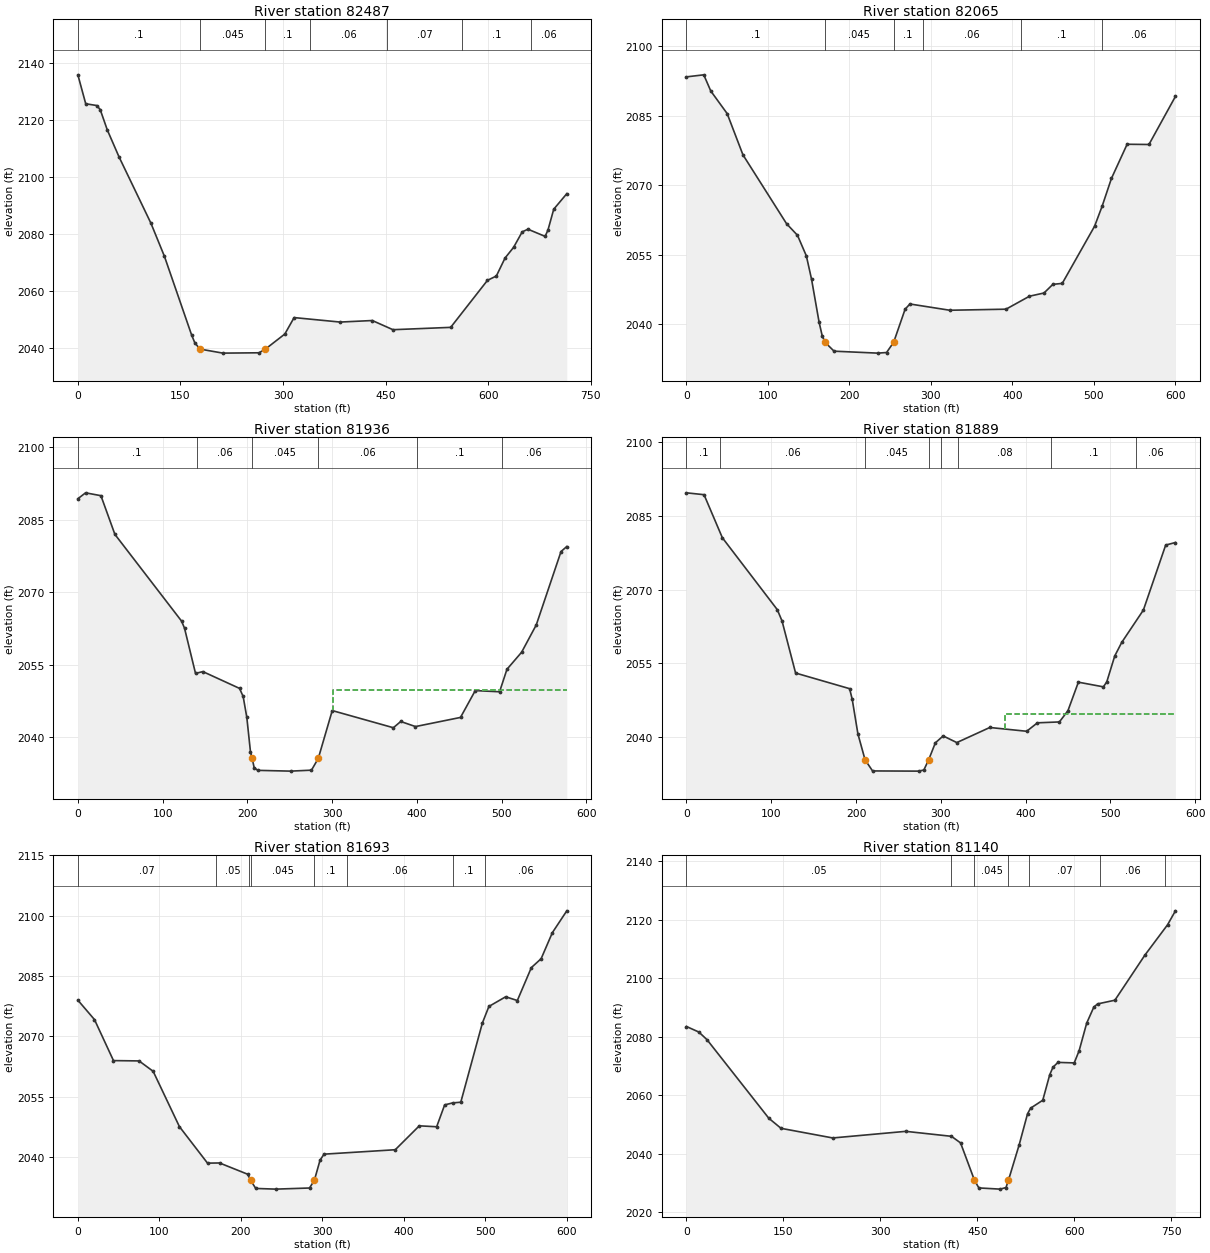
Type RM Length L Ch R = 1 ,82487   ,422.2,422.2,422.2
XS GIS Cut Line= 3
2240133.73232795663314.8226970722240475.53831648663066.924342774
2240754.28743678662977.898657619
#Sta/Elev= 30
       0 2135.87    11.5 2125.71    27.7  2125.1    32.7 2123.65      43 2116.56
    60.2 2107.07   106.8 2083.82   126.5 2072.23   166.3  2044.6     171 2041.84
  178.592039.638     212 2038.22   264.9 2038.34  274.222039.638   302.6 2044.92
   316.2 2050.69   383.5 2049.12   430.5 2049.66   460.7 2046.44   545.1 2047.26
   598.9 2063.76   611.9 2065.28   624.6 2071.59   637.1 2075.33   649.7 2080.77
   658.1  2081.7   683.2 2079.18   687.4 2081.43   695.8 2088.72   714.9 2094.17
#Mann= 7 ,-1,0
       0      .1       0  178.59    .045       0  274.22      .1       0
     340     .06       0  452.24     .07       0  562.24      .1       0
  662.24     .06       0
Bank Sta=178.59,274.22
XS Rating Curve= 0 ,0
Exp/Cntr(USF)=0,0
Exp/Cntr=0.3,0.1

Type RM Length L Ch R = 1 ,82065   ,128.9,128.9,128.9
XS GIS Cut Line= 2
2240511.77167474663634.2376246182240852.54318408 663140.40083131
#Sta/Elev= 30
       0 2093.37    21.2 2093.81    29.8 2090.32    49.9 2085.45    69.3 2076.54
   122.8 2061.69   136.2 2059.19   147.1 2054.74   153.5 2049.68   162.7 2040.46
   166.5 2037.53  170.012036.106   181.1 2034.19   234.6 2033.77   245.5  2033.9
  254.212036.108   268.3 2043.26   274.2 2044.37   323.1 2043.02   392.1 2043.25
   420.9 2046.05   438.7 2046.74   449.6 2048.61   461.1 2048.81   500.8 2061.15
     510 2065.44   521.5 2071.47   540.7 2078.83   567.5 2078.78     600 2089.15
#Mann= 6 ,-1,0
       0      .1       0  170.01    .045       0  254.21      .1       0
     290     .06       0     410      .1       0     510     .06       0
Bank Sta=170.01,254.21
XS Rating Curve= 0 ,0
Exp/Cntr(USF)=0,0
Exp/Cntr=0.3,0.1

Type RM Length L Ch R = 1 ,81936   ,47.8,47.8,47.8
XS GIS Cut Line= 2
 2240645.1527934663761.6387990892240863.67882959663227.834741204
#Sta/Elev= 30
       0 2089.36     9.1 2090.58    27.2 2089.99    43.7 2081.98   122.3 2064.05
   125.8 2062.59   138.8 2053.22   147.5 2053.59   190.7 2050.12     195 2048.45
   199.3 2044.13   203.6 2037.04  205.642035.642     208  2033.7   212.3 2033.16
   251.1    2033   275.6  2033.2  283.642035.641   300.1 2045.53   372.2 2041.98
   380.9 2043.27   398.3 2042.22   451.4 2044.11   468.8 2049.66   497.5 2049.42
   506.2 2054.07   523.5  2057.6   540.8 2063.26     570 2078.44   576.8 2079.47
#Mann= 6 ,-1,0
       0      .1       0     140     .06       0  205.64    .045       0
  283.64     .06       0     400      .1       0     500     .06       0
#XS Ineff= 2 , 0
                          300.85          2049.7
Permanent Ineff=
       F       F
Bank Sta=205.64,283.64
XS Rating Curve= 0 ,0
Exp/Cntr(USF)=0,0
Exp/Cntr=0.3,0.1

Type RM Length L Ch R = 1 ,81889   ,195.6,195.6,195.6
XS GIS Cut Line= 2
 2240684.3540289663788.329001984 2240902.8800651663254.524944098
#Sta/Elev= 30
       0 2089.69    20.7 2089.31    42.3 2080.55   107.1 2065.92   112.7 2063.62
   128.7 2053.02   192.4 2049.84   195.5 2047.68   202.2 2040.65  210.652035.364
   219.5  2033.1     274 2033.06     280 2033.29  285.682035.365   293.6 2038.82
   302.8 2040.22   318.9 2038.87   357.8 2041.94   401.3 2041.17     414 2042.89
   439.9 2043.07     450 2045.36   462.3 2051.16   491.8 2050.21   495.8 2051.22
   505.2 2056.49   513.4 2059.24     539 2065.84   565.3 2079.06   576.8 2079.58
#Mann= 8 ,-1,0
       0      .1       0      40     .06       0  210.65    .045       0
  285.68     .06       0     300      .1       0     320     .08       0
     430      .1       0     530     .06       0
#XS Ineff= 2 , 0
                          376.14          2044.7
Permanent Ineff=
       F       F
Bank Sta=210.65,285.68
XS Rating Curve= 0 ,0
Exp/Cntr(USF)=0,0
Exp/Cntr=0.3,0.1

Type RM Length L Ch R = 1 ,81693   ,552.9,552.9,552.9
XS GIS Cut Line= 2
2240800.23939602663862.196554319 2241151.3231815663375.637024999
#Sta/Elev= 30
       0 2079.02    20.4 2074.19    43.7    2064    75.1 2063.92    92.4 2061.34
   124.6  2047.6   159.1 2038.52   173.9 2038.56   208.4 2035.76  211.982034.258
   218.3 2032.23     243 2032.06   284.3 2032.34  290.232034.258   297.2 2039.26
   302.1 2040.75   389.5 2041.85     419 2047.79   440.3 2047.56   450.1 2052.99
     460 2053.49   469.9 2053.66   496.4 2073.34   504.4 2077.46     525 2079.86
   539.3 2078.93   556.5 2087.11   568.5 2089.32   582.3  2095.8     600 2101.22
#Mann= 8 ,-1,0
       0     .07       0     170     .05       0     210      .1       0
  211.98    .045       0  290.23      .1       0     330     .06       0
     460      .1       0     500     .06       0
Bank Sta=211.98,290.23
XS Rating Curve= 0 ,0
Exp/Cntr(USF)=0,0
Exp/Cntr=0.3,0.1

Type RM Length L Ch R = 1 ,81140   ,318.6,318.6,318.6
XS GIS Cut Line= 2
2240943.95137728664177.9040382482241586.51801196663778.551877443
#Sta/Elev= 30
       0 2083.56    19.1 2081.67    31.7 2079.07   127.4  2052.2   146.3 2048.76
   226.3 2045.47   339.4 2047.73     410 2046.03   424.1 2043.78  445.532031.068
   452.4 2028.39   485.3 2027.98   494.4 2028.51  498.282031.067   514.8 2043.13
   527.7  2053.7   532.4 2055.64   551.3 2058.36   562.1 2067.08   567.1 2069.64
   574.8  2071.3     600 2071.12   607.6 2075.31   619.3 2084.73   630.3 2090.19
   636.1 2091.28   662.9 2092.55   709.4 2107.98   744.4 2118.32   756.6  2123.1
#Mann= 7 ,-1,0
       0     .05       0     410      .1       0  445.53    .045       0
  498.28      .1       0     530     .07       0     640     .06       0
     740      .1       0
Bank Sta=445.53,498.28
XS Rating Curve= 0 ,0
Exp/Cntr(USF)=0,0
Exp/Cntr=0.3,0.1

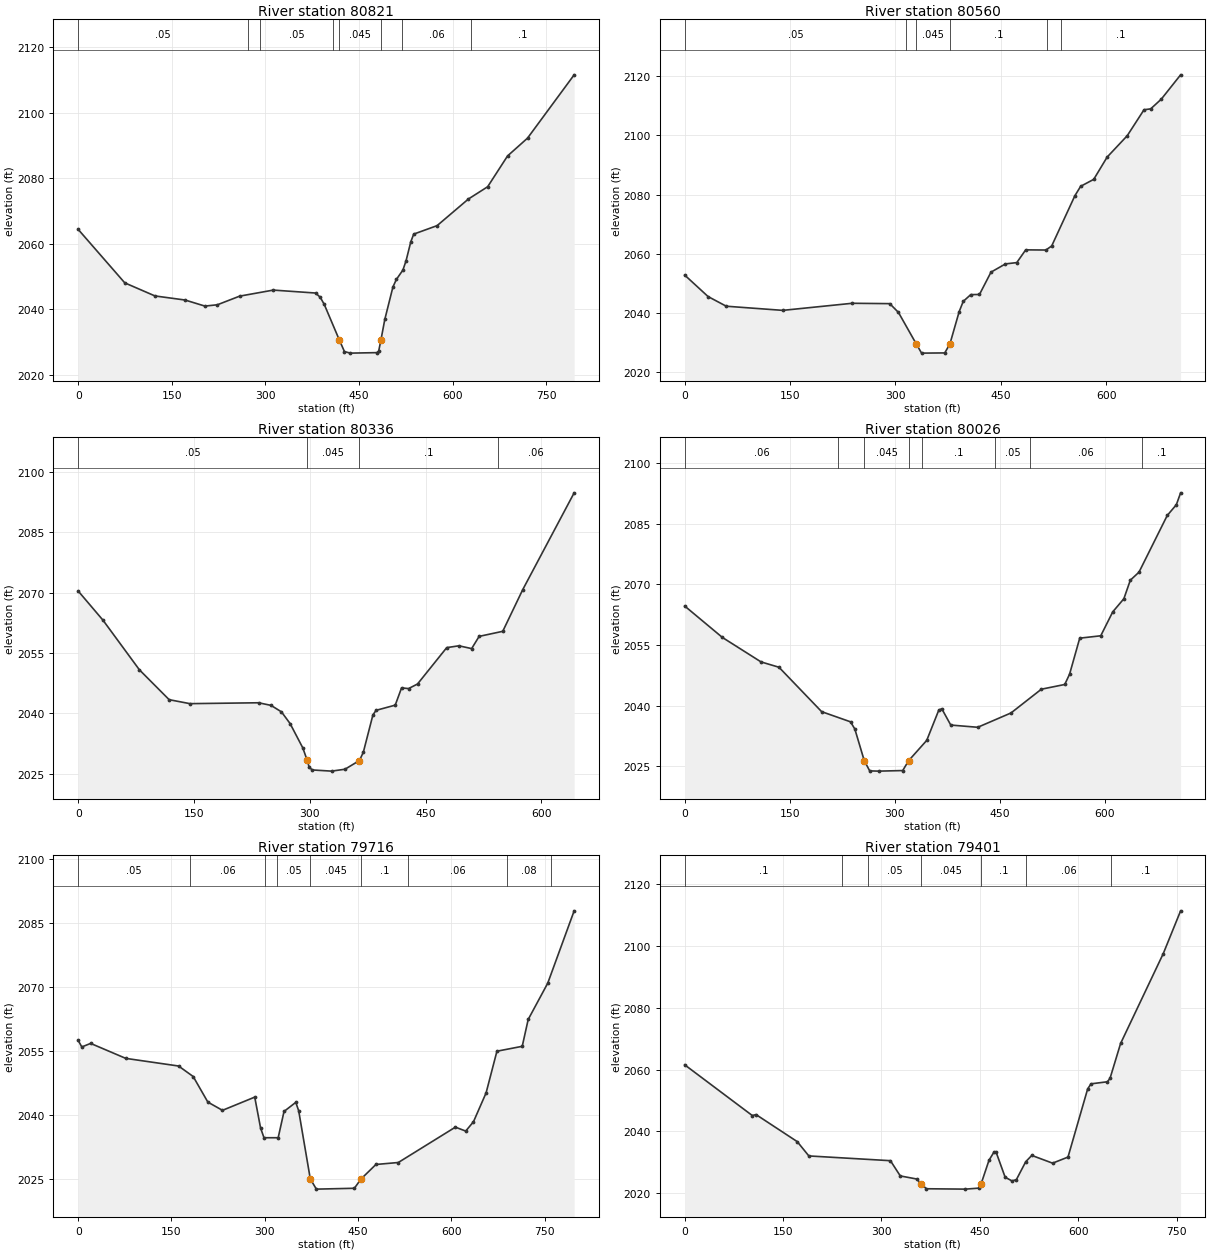
Type RM Length L Ch R = 1 ,80821   ,261.4,261.4,261.4
XS GIS Cut Line= 4
2241166.14731637664452.6463142912241232.20556853664389.590709953
2241406.35914242664258.975529539  2241826.729838664015.761055665
#Sta/Elev= 30
       0 2064.36    74.6 2048.03     123 2044.03   171.3 2042.78     203 2040.93
     223 2041.33   258.7 2043.97   312.6 2045.82   380.4 2044.92   387.8 2043.63
   394.3 2041.43  418.582030.495   426.6 2027.03   435.9 2026.55   478.5  2026.7
   481.5 2027.18  485.022030.499   491.3 2036.87   504.3 2046.77   509.8 2049.07
   520.3 2051.94   525.4 2054.82   532.9 2060.56   537.6 2062.93   575.1 2065.52
   625.4 2073.68   656.1 2077.41     688 2086.83     720 2092.27   794.7 2111.62
#Mann= 8 ,-1,0
       0     .05       0  271.32      .1       0  291.32     .05       0
  409.01      .1       0  418.58    .045       0  485.02      .1       0
  519.01     .06       0  629.01      .1       0
Bank Sta=418.58,485.02
XS Rating Curve= 0 ,0
Exp/Cntr(USF)=0,0
Exp/Cntr=0.3,0.1

Type RM Length L Ch R = 1 ,80560   ,224,224,224
XS GIS Cut Line= 4
2241293.19468729664539.819250349 2241392.8472272664481.171468634
2241831.23380974664374.5774708252241947.84991685664298.808301586
#Sta/Elev= 30
       0 2052.86    33.3 2045.61    59.2 2042.35   139.6 2040.95   238.4 2043.34
   291.9 2043.22   304.3 2040.25  329.58 2029.65   337.2 2026.53   370.2  2026.6
  377.542029.649   390.7 2040.52   396.5 2043.99   407.2 2046.26   419.6 2046.31
     436 2053.84   456.6 2056.62   472.7 2057.06   485.4 2061.36   514.2  2061.3
   522.4 2062.68   555.4 2079.61   563.6 2082.79   582.2 2085.13   601.3 2092.64
   629.9 2099.85   653.8 2108.61   663.3 2108.91   678.4 2112.19   705.9 2120.39
#Mann= 6 ,-1,0
       0     .05       0  315.63      .1       0  329.58    .045       0
  377.54      .1       0  515.63     .06       0  535.63      .1       0
Bank Sta=329.58,377.54
XS Rating Curve= 0 ,0
Exp/Cntr(USF)=0,0
Exp/Cntr=0.3,0.1

Type RM Length L Ch R = 1 ,80336   ,310.1,310.1,310.1
XS GIS Cut Line= 4
2241369.73426187664748.5680391512241434.88429676664703.367407729
2241856.75631626 664596.773409922241955.48789953664515.200726259
#Sta/Elev= 30
       0 2070.43    32.2 2063.16    79.3 2050.84   117.8 2043.42   144.7 2042.43
   233.7 2042.65   249.8    2042   263.3 2040.39   274.5 2037.48     291 2031.41
  296.712028.294   299.3 2026.57   303.4 2025.94   328.2 2025.65   345.6 2026.12
   364.42028.293   369.4 2030.37   381.8 2039.63   385.9 2040.77   410.7 2042.06
   418.9 2046.35     428 2046.18   439.6 2047.32   477.4 2056.36   493.2 2056.82
   509.7 2056.12   519.4 2059.16     550 2060.42   575.9 2070.79   642.5 2094.86
#Mann= 4 ,-1,0
       0     .05       0  296.71    .045       0   364.4      .1       0
  544.42     .06       0
Bank Sta=296.71,364.4
XS Rating Curve= 0 ,0
Exp/Cntr(USF)=0,0
Exp/Cntr=0.3,0.1

Type RM Length L Ch R = 1 ,80026   ,309.7,309.7,309.7
XS GIS Cut Line= 4
2241467.48474861664977.1314775542241571.50477283 665009.63748594
2241808.71395105 664918.05672726 2242130.5974698 664795.01512936
#Sta/Elev= 30
       0 2064.66    53.8 2056.89     109 2050.84   134.6 2049.52   195.5 2038.54
   236.7 2036.03   242.9 2034.24  256.292026.448   264.1  2023.9   276.8 2023.84
   311.2 2023.98   319.8 2026.45   345.5 2031.44   362.7 2038.92     367 2039.26
   379.8 2035.23   418.3 2034.68   465.8 2038.22   509.1 2044.09   542.5 2045.26
   549.4 2047.81   563.9 2056.71   593.9  2057.3     611 2063.21   626.9 2066.46
   636.1 2071.04   648.5 2073.03   688.8 2087.04   701.8  2089.7   707.9 2092.64
#Mann= 8 ,-1,0
       0     .06       0  218.98     .03       0  256.29    .045       0
   319.8     .03       0  338.98      .1       0  443.25     .05       0
  493.25     .06       0  653.25      .1       0
Bank Sta=256.29,319.8
XS Rating Curve= 0 ,0
Exp/Cntr(USF)=0,0
Exp/Cntr=0.3,0.1

Type RM Length L Ch R = 1 ,79716   ,315.8,315.8,315.8
XS GIS Cut Line= 2
2241531.21162245665435.8354499982242208.17808255665014.153141632
#Sta/Elev= 30
       0 2057.47     5.8 2055.95      20 2056.78    76.5 2053.27   161.4 2051.48
   184.9 2049.02   208.5 2043.02     232 2041.09   283.9 2044.19   293.3 2036.94
   298.8 2034.67   321.6 2034.67     331 2040.83   349.9 2042.96   354.6 2040.98
  373.232025.025     383 2022.62   444.1 2022.82  455.052025.029   478.8  2028.4
   514.8 2028.86   606.6 2037.15   623.2 2036.23   635.7 2038.42     656 2045.19
   673.4 2054.95   714.1  2056.1   723.7  2062.4   755.1 2070.89   797.6 2087.86
#Mann= 9 ,-1,0
       0     .05       0     180     .06       0     300     .07       0
     320     .05       0  373.23    .045       0  455.05      .1       0
     530     .06       0     690     .08       0     760      .1       0
Bank Sta=373.23,455.05
XS Rating Curve= 0 ,0
Exp/Cntr(USF)=0,0
Exp/Cntr=0.3,0.1

Type RM Length L Ch R = 1 ,79401   ,393.4,393.4,393.4
XS GIS Cut Line= 2
2241761.91564748665703.2660372272242365.19549763665247.495517856
#Sta/Elev= 30
       0 2061.58   103.1 2045.16   108.8 2045.47   171.6 2036.72   189.3 2032.09
   313.7 2030.55   328.7 2025.62   353.8 2024.62  360.09 2023.11   368.6 2021.47
   428.1 2021.35   448.1 2021.67  452.012023.113     464 2030.71   471.4 2033.29
   474.6 2033.43   488.6 2025.19   499.1    2024   505.7 2024.42     520 2030.23
   529.2 2032.26   560.9 2029.75   584.4 2031.72   614.4 2053.79   619.5 2055.42
   644.5 2056.09   648.5 2057.21   664.6 2068.48   729.7 2097.59   756.1  2111.4
#Mann= 7 ,-1,0
       0      .1       0     240     .07       0     280     .05       0
  360.09    .045       0  452.01      .1       0     520     .06       0
     650      .1       0
Bank Sta=360.09,452.01
XS Rating Curve= 0 ,0
Exp/Cntr(USF)=0,0
Exp/Cntr=0.3,0.1

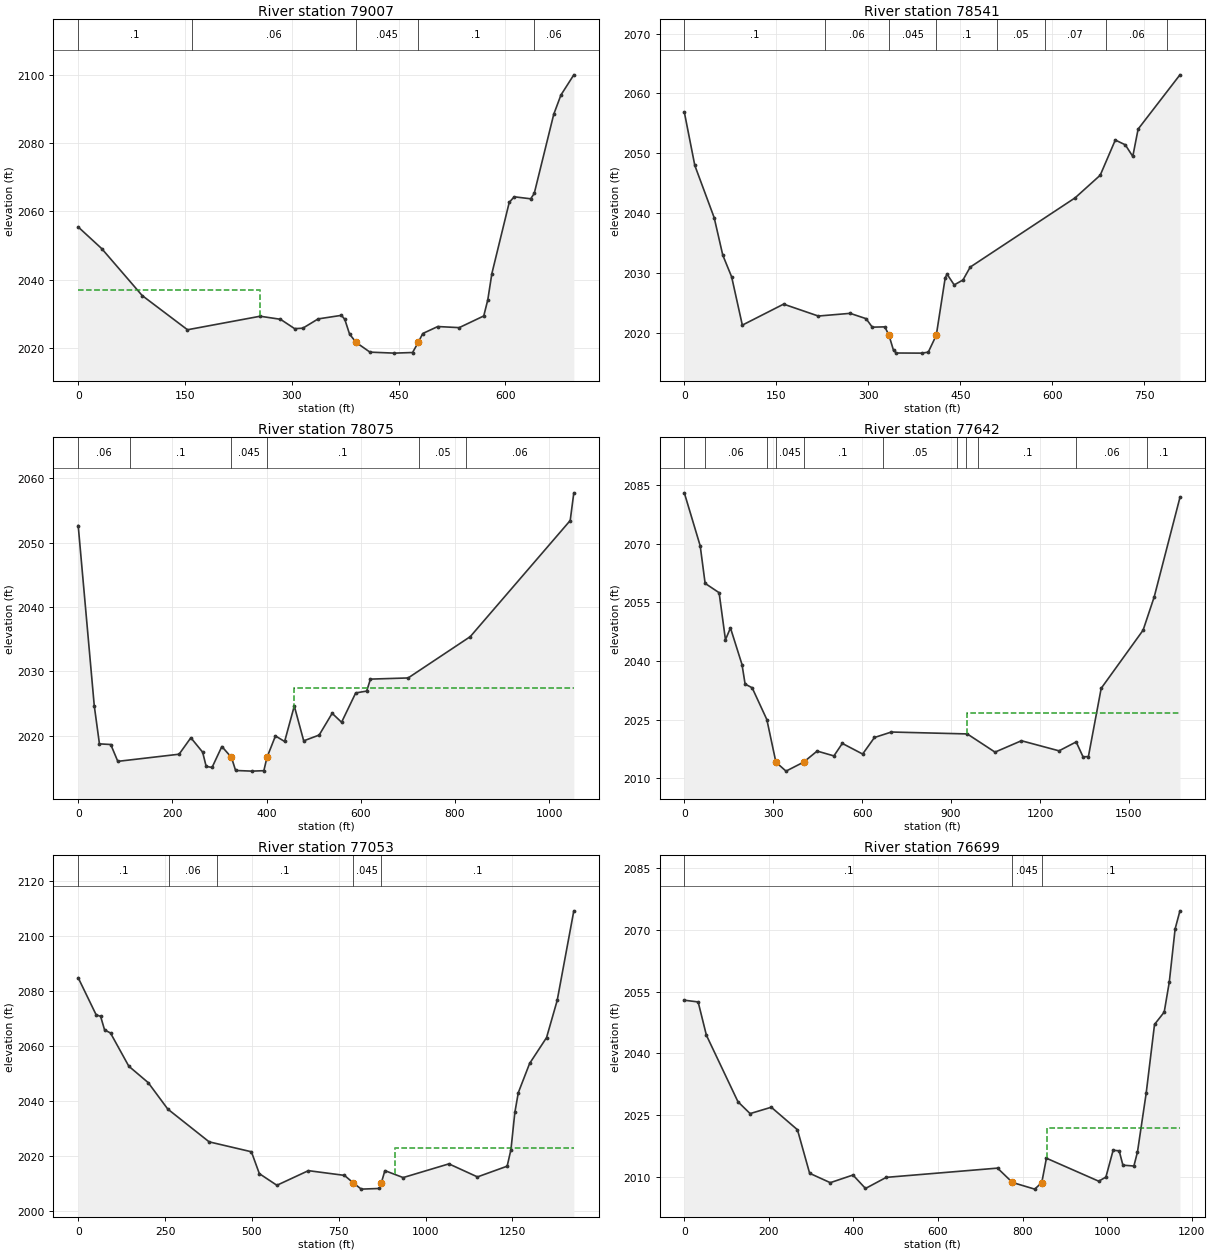
Type RM Length L Ch R = 1 ,79007   ,466.3,466.3,466.3
XS GIS Cut Line= 2
2241953.83525591666048.8222158682242508.44793421665628.165361742
#Sta/Elev= 30
       0 2055.48    33.1 2049.14    89.9 2035.43   153.5 2025.44   255.5 2029.39
   284.1  2028.5     304 2025.76   315.5  2025.9     337 2028.61   369.7 2029.65
   374.4 2028.49   381.1 2024.19   390.3 2021.74   409.8  2018.9   443.9 2018.61
   469.6 2018.79  477.612021.742   483.9 2024.34     505 2026.38   535.1 2026.06
   569.6 2029.47   575.3 2034.22     581 2041.86   605.4 2062.67   612.4  2064.3
   635.5 2063.71   640.5 2065.27   667.9 2088.41     678 2094.04   696.1 2099.94
#Mann= 5 ,-1,0
       0      .1       0     160     .06       0   390.3    .045       0
  477.61      .1       0     640     .06       0
#XS Ineff= 2 , 0
          255.23 2037.06
Permanent Ineff=
       F       F
Bank Sta=390.3,477.61
XS Rating Curve= 0 ,0
Exp/Cntr(USF)=0,0
Exp/Cntr=0.3,0.1

Type RM Length L Ch R = 1 ,78541   ,465.3,465.3,465.3
XS GIS Cut Line= 3
2242238.85666531 666370.256676552242720.01756612666069.572168379
2242769.81950585665833.996452443
#Sta/Elev= 30
       0 2056.89    17.1 2047.98    48.7 2039.24    62.7 2032.99    77.2 2029.34
    94.6 2021.28   161.9 2024.79   218.5  2022.8   270.4 2023.25   296.4 2022.36
   306.5 2020.94     327 2020.99  333.692019.592   341.2 2017.04   345.9 2016.62
     387  2016.6   397.8 2016.76  410.892019.591   425.5 2029.24   428.5 2029.79
   440.1    2028   454.4 2028.83   466.2 2030.98   637.3 2042.56   678.2 2046.34
   702.8 2052.22   719.1 2051.42   731.3 2049.48     740 2054.05   808.2 2063.12
#Mann= 8 ,-1,0
       0      .1       0     230     .06       0  333.69    .045       0
  410.89      .1       0     510     .05       0  587.39     .07       0
  687.39     .06       0  787.39      .1       0
Bank Sta=333.69,410.89
XS Rating Curve= 0 ,0
Exp/Cntr(USF)=0,0
Exp/Cntr=0.3,0.1

Type RM Length L Ch R = 1 ,78075   ,433.6,433.6,433.6
XS GIS Cut Line= 3
2242584.87559634666728.2421848052243067.94227025666365.738864736
2243060.39650694665917.482752678
#Sta/Elev= 30
       0 2052.67    34.1 2024.65    45.1 2018.72    69.1 2018.62    84.1    2016
   214.2 2017.11   239.2 2019.67   264.2 2017.43   271.7 2015.22   284.2 2015.05
     305 2018.31  325.422016.613   334.2 2014.58   369.2 2014.48   394.2 2014.55
  400.812016.615   418.8 2019.95   438.3 2019.09   458.8 2024.61   478.8 2019.19
   511.6 2020.09   539.2 2023.47   559.2 2022.08   589.2 2026.64   612.5 2026.93
   620.5 2028.79   700.5 2028.97   832.5  2035.4  1044.6 2053.45  1052.3 2057.76
#Mann= 6 ,-1,0
       0     .06       0     110      .1       0  325.42    .045       0
  400.81      .1       0  723.96     .05       0  823.96     .06       0
#XS Ineff= 2 , 0
                          457.21          2027.4
Permanent Ineff=
       F       F
Bank Sta=325.42,400.81
XS Rating Curve= 0 ,0
Exp/Cntr(USF)=0,0
Exp/Cntr=0.3,0.1

Type RM Length L Ch R = 1 ,77642   ,588.4,588.4,588.4
XS GIS Cut Line= 4
2242510.73042008666845.2823362092242742.79660598666935.095688142
2243429.27301786666839.0454905932243861.81034535667427.191619327
#Sta/Elev= 30
       0 2083.04    53.6 2069.48    70.2 2059.89   117.4  2057.5   138.8 2045.48
   155.7  2048.5   194.6 2039.14   205.1 2034.14   228.9 2033.19   278.5 2025.05
  308.972014.177   343.1 2011.88  402.442014.178   448.1 2017.01   504.7 2015.77
     533 2018.97   601.6 2016.25   641.5 2020.48   698.6 2021.88   954.6 2021.39
  1048.2 2016.74  1137.3 2019.65  1264.2 2017.07    1322 2019.35  1345.2 2015.53
  1363.3 2015.61  1406.4 2033.05  1547.8 2047.92  1585.2 2056.41  1672.1 2081.85
#Mann= 11 ,-1,0
       0      .1       0      70     .06       0  278.84      .1       0
  308.97    .045       0  402.44      .1       0  668.84     .05       0
  918.84     .07       0     952     .05       0     992      .1       0
    1322     .06       0    1562      .1       0
#XS Ineff= 2 , 0
                           952.4         2026.78
Permanent Ineff=
       F       F
Bank Sta=308.97,402.44
XS Rating Curve= 0 ,0
Exp/Cntr(USF)=0,0
Exp/Cntr=0.3,0.1

Type RM Length L Ch R = 1 ,77053   ,354,354,354
XS GIS Cut Line= 4
2242288.23788526666943.9686643952242852.64987683667498.652590754
2242946.55672446667497.9627928132243351.71678498667857.266593513
#Sta/Elev= 30
       0 2084.85    51.7 2071.35    64.5  2070.8    75.9 2065.88      93 2064.73
   145.7 2052.64   201.5 2046.66   257.9 2037.02     377 2025.08   498.6 2021.47
   521.5  2013.5     572 2009.26   662.7 2014.59   766.4 2012.87  791.41 2010.19
   814.9 2007.86   866.9  2008.1  872.75 2010.19   882.9  2014.6   935.5 2012.07
  1067.2 2017.06  1149.4 2012.31  1234.9 2016.22  1245.8 2022.26    1257 2035.79
    1267    2043  1299.5 2053.63  1348.3 2063.06  1378.9 2076.58  1426.8 2109.24
#Mann= 5 ,-1,0
       0      .1       0     260     .06       0     400      .1       0
  791.41    .045       0  872.75      .1       0
#XS Ineff= 2 , 0
                          910.68         2022.99
Permanent Ineff=
       F       F
Bank Sta=791.41,872.75
XS Rating Curve= 0 ,0
Exp/Cntr(USF)=0,0
Exp/Cntr=0.3,0.1

Type RM Length L Ch R = 1 ,76699   ,378,378,378
XS GIS Cut Line= 2
2242117.42799193667355.1624805122243077.58233931668027.661018112
#Sta/Elev= 30
       0 2052.94    32.7 2052.52    52.2 2044.43   126.9 2028.24   155.6 2025.36
   205.7 2026.91   267.6 2021.43   296.4 2010.84   345.2 2008.56   398.9 2010.42
   428.5 2007.15   477.6 2009.85   740.8  2012.1     776 2008.61   828.7 2006.99
  845.382008.564   856.4 2014.51   980.1 2008.92   997.1 2009.92  1014.2 2016.44
  1028.5 2016.31  1037.3 2012.82  1063.3 2012.61  1071.8 2016.05  1092.4 2030.35
  1112.1 2047.05    1135 2050.05    1147 2057.35  1160.8 2070.28  1172.2 2074.68
#Mann= 3 ,-1,0
       0      .1       0     776    .045       0  845.38      .1       0
#XS Ineff= 2 , 0
                          856.76         2021.81
Permanent Ineff=
       F       F
Bank Sta=776,845.38
XS Rating Curve= 0 ,0
Exp/Cntr(USF)=0,0
Exp/Cntr=0.3,0.1

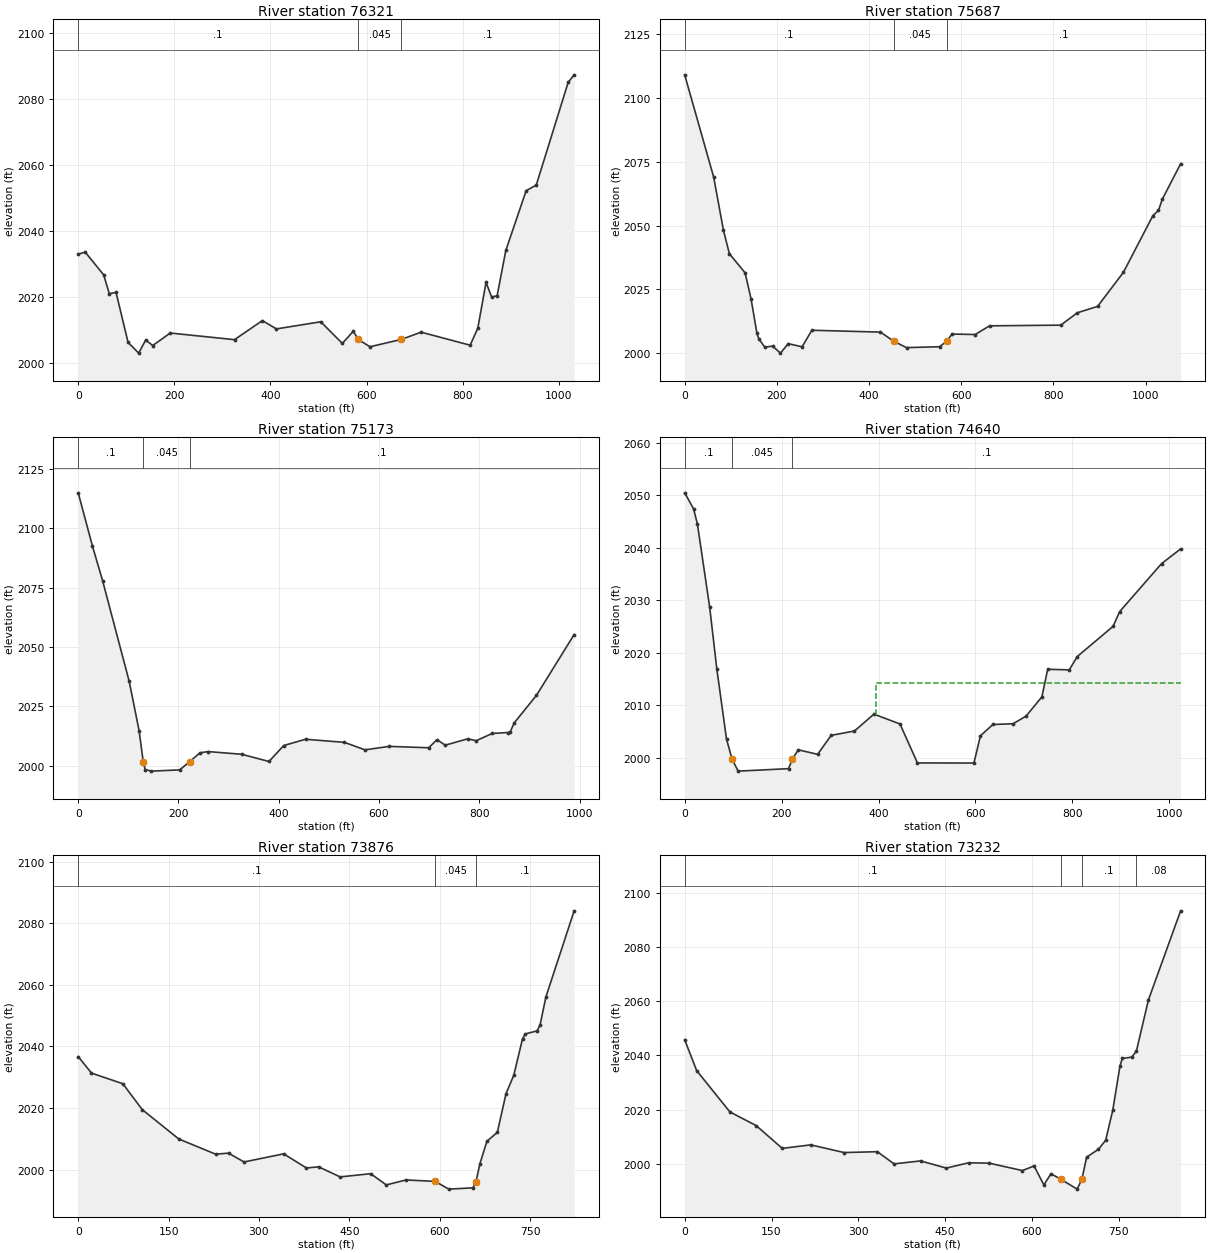
Type RM Length L Ch R = 1 ,76321   ,634.2,634.2,634.2
XS GIS Cut Line= 2
2242016.55200619667748.5281829822242866.34652732668333.845837837
#Sta/Elev= 30
       0 2032.87    14.6 2033.46      53 2026.58    64.6 2020.88    78.7 2021.27
   103.7 2006.12   125.8 2002.86   140.4 2006.83     155 2005.16   191.5 2008.95
   325.2 2006.94   383.2 2012.72   412.4  2010.2   504.7 2012.36   549.5  2005.8
   572.5 2009.51   582.4 2007.02     607 2004.79   672.4 2007.02   713.5 2009.21
   815.5 2005.26   831.4 2010.41   848.6 2024.31   860.1 2019.87   871.6 2020.22
   889.7 2033.97     932 2052.08   953.1  2053.8  1019.5 2084.94  1031.9  2087.2
#Mann= 3 ,0,0
       0      .1       0   582.4    .045       0   672.4      .1       0
Bank Sta=582.4,672.4
XS Rating Curve= 0 ,0
Exp/Cntr(USF)=0,0
Exp/Cntr=0.3,0.1

Type RM Length L Ch R = 1 ,75687   ,513.9,513.9,513.9
XS GIS Cut Line= 4
 2241793.0919315668379.4077446382242135.78338033668505.105447962
2242427.40153818668781.9526474252242736.25231254668776.349671908
#Sta/Elev= 30
       0 2109.09    62.9 2069.01    84.2 2048.09      97 2038.97   131.1 2031.47
   144.1 2021.19   156.7 2007.84   160.9 2005.61   173.7 2002.35   190.7 2002.74
   207.8    2000   224.8 2003.71   254.7 2002.48     276 2008.97   424.8 2008.24
  453.45 2004.67   481.3 2002.16   553.1 2002.51   568.5 2004.65   580.1 2007.48
   630.3 2007.29   661.4  2010.7     816 2010.97   851.9 2015.82   895.9 2018.32
   951.9 2031.68  1015.9 2053.91    1028 2055.94    1036 2060.22    1076 2074.22
#Mann= 3 ,0,0
       0      .1       0  453.45    .045       0   568.5      .1       0
Bank Sta=453.45,568.5
XS Rating Curve= 0 ,0
Exp/Cntr(USF)=0,0
Exp/Cntr=0.3,0.1

Type RM Length L Ch R = 1 ,75173   ,533.4,533.4,533.4
XS GIS Cut Line= 4
2241732.14588415668945.1208299842242207.32220481669018.884278334
2242525.05099657669091.7453171662242707.35563181669084.455233335
#Sta/Elev= 30
       0 2114.95    28.4 2092.51    48.6 2077.96   101.7 2035.55   121.5 2014.71
   129.7  2001.7   133.6 1998.39   145.8 1997.73   202.4 1998.25   222.7 2001.78
   242.9 2005.44   259.1 2005.97   325.9 2004.83   380.5 2001.79     410 2008.51
   453.4 2011.15     531 2009.85     572  2006.7   620.4 2008.15   699.2 2007.57
   715.7 2010.99   732.1 2008.66   777.1 2011.34     794 2010.55     826  2013.6
     858    2014     862 2014.41     870 2018.12   914.1 2029.64   989.3 2055.26
#Mann= 3 ,0,0
       0      .1       0   129.7    .045       0   222.7      .1       0
Bank Sta=129.7,222.7
XS Rating Curve= 0 ,0
Exp/Cntr(USF)=0,0
Exp/Cntr=0.3,0.1

Type RM Length L Ch R = 1 ,74640   ,764,764,764
XS GIS Cut Line= 3
2241697.89161528 669477.880747482242086.80578828669482.516872353
2242652.45527313669769.760843833
#Sta/Elev= 30
       0 2050.47    18.3 2047.44    26.3 2044.51    51.6 2028.68    66.3 2016.95
    86.3 2003.59   97.661999.785   110.3 1997.48   214.3 1997.95   222.3 1999.75
   234.3 2001.54   274.3 2000.68   302.3 2004.29   350.3 2005.12   390.5 2008.33
   444.3 2006.46   480.2 1999.04   596.8 1999.02   610.3 2004.21   635.9 2006.36
   677.6  2006.5   704.5 2007.96   737.1 2011.63     749 2016.87   793.6 2016.76
     810 2019.29     884 2025.05   897.4 2027.84     984 2036.99  1023.3 2039.79
#Mann= 3 ,-1,0
       0      .1       0   97.66    .045       0   222.3      .1       0
#XS Ineff= 2 , 0
                          395.48         2014.18
Permanent Ineff=
       F       F
Bank Sta=97.66,222.3
XS Rating Curve= 0 ,0
Exp/Cntr(USF)=0,0
Exp/Cntr=0.3,0.1

Type RM Length L Ch R = 1 ,73876   ,643.4,643.4,643.4
XS GIS Cut Line= 3
2241507.92636553669587.2539694632241496.04591184669750.647738783
2241866.35846323 670296.09566397
#Sta/Elev= 30
       0 2036.69      22 2031.33    74.1 2027.87   106.3 2019.46   166.9 2009.93
   228.1 2004.99   249.5 2005.33   275.2 2002.46   340.9  2005.1   378.8 2000.51
     399 2000.88   434.7 1997.61   485.4 1998.65   511.3 1995.01     544 1996.62
   592.3 1996.16     615 1993.64   655.2 1994.06   660.21996.058   666.8 2001.96
   678.3 2009.19   695.6 2012.07     710 2024.63   722.9 2030.62   737.4 2042.46
   742.2 2044.05   761.6 2045.05   766.4 2046.85   776.2 2056.05   823.1 2084.03
#Mann= 3 ,-1,0
       0      .1       0   592.3    .045       0   660.2      .1       0
Bank Sta=592.3,660.2
XS Rating Curve= 0 ,0
Exp/Cntr(USF)=0,0
Exp/Cntr=0.3,0.1

Type RM Length L Ch R = 1 ,73232   ,595.9,595.9,595.9
XS GIS Cut Line= 2
2241285.50850613669536.9914161682241090.55852912 670371.34954026
#Sta/Elev= 30
       0 2045.78    20.7 2034.38    78.2 2019.14   123.4 2014.14   168.6 2005.72
   217.9 2007.02   275.4 2004.18   332.9  2004.5   361.7    2000   407.5  2001.1
     452 1998.46   490.7 2000.41     526 2000.28   583.5 1997.54   603.6 1999.25
   620.5 1992.24   632.8 1996.36  650.111994.306     678  1990.7   686.2 1994.32
   694.4 2002.48   714.9  2005.4   727.3 2008.71   739.6 2019.81   751.9 2035.91
     756 2038.87   772.4 2039.36   780.4 2041.59   801.2 2060.43   856.8 2093.28
#Mann= 4 ,-1,0
       0      .1       0  650.11    .045       0   686.2      .1       0
     780     .08       0
Bank Sta=650.11,686.2
XS Rating Curve= 0 ,0
Exp/Cntr(USF)=0,0
Exp/Cntr=0.3,0.1

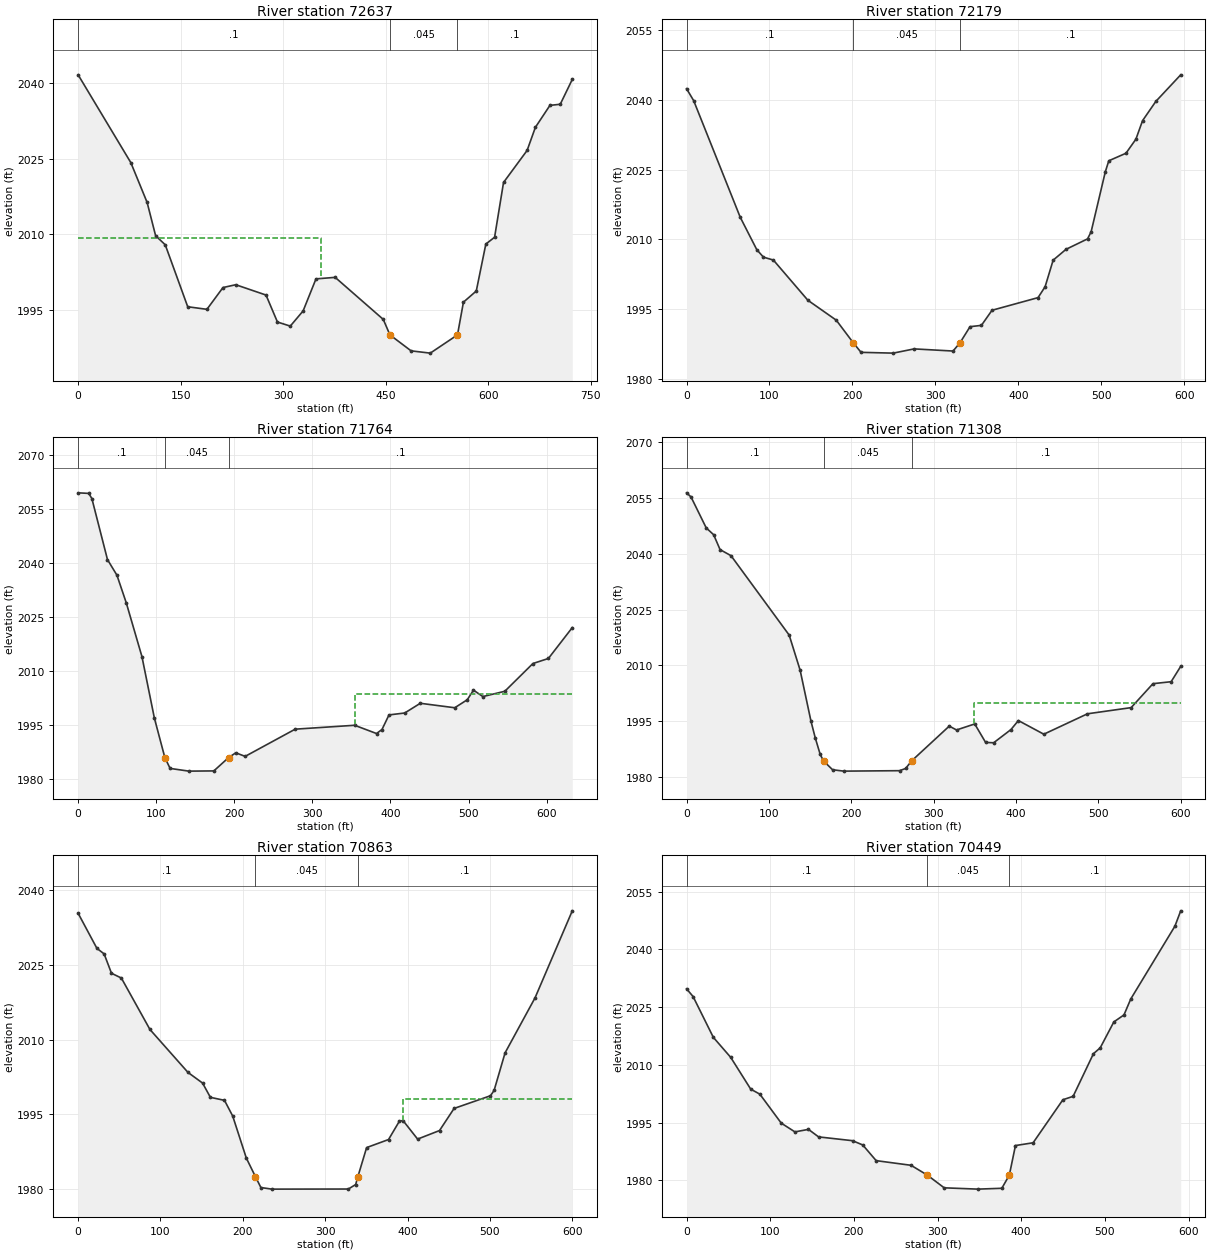
Type RM Length L Ch R = 1 ,72637   ,457.2,457.2,457.2
XS GIS Cut Line= 4
2240852.04695892669429.3121118662240835.52841161669539.194941679
2240552.13806498670001.3391992672240561.75742582 670070.69277082
#Sta/Elev= 30
       0 2041.62    77.1 2024.21     101  2016.3   113.4 2009.71   127.5  2007.9
   160.4 1995.61   188.5  1995.1     212 1999.42   230.7 1999.98     275 1997.93
   291.7 1992.58   310.5 1991.77   329.3 1994.79   348.1 2001.14   376.2 2001.44
   446.6  1993.1  456.321990.029   487.3 1986.86   515.4 1986.41  555.191990.028
   563.9 1996.52   582.7 1998.73   596.7 2008.05   609.5  2009.4   622.6 2020.27
   657.1 2026.62   669.2  2031.2   690.5 2035.56   705.6 2035.78   723.2 2040.71
#Mann= 3 ,-1,0
       0      .1       0  456.32    .045       0  555.19      .1       0
#XS Ineff= 2 , 0
             355 2009.28
Permanent Ineff=
       F       F
Bank Sta=456.32,555.19
XS Rating Curve= 0 ,0
Exp/Cntr(USF)=0,0
Exp/Cntr=0.3,0.1

Type RM Length L Ch R = 1 ,72179   ,415.3,415.3,415.3
XS GIS Cut Line= 4
2240306.41555962 669364.576739612240301.44660449669484.696798096
2240161.93135692 669859.644025952240164.29324727669935.109625899
#Sta/Elev= 30
       0 2042.42     8.6 2039.84    64.7 2014.77    84.7 2007.78    92.7 2006.18
   104.7 2005.55   146.3  1996.9   180.5 1992.62  200.941987.769   210.4  1985.7
   249.1 1985.53   274.4 1986.44   321.3 1985.98  329.75 1987.77   341.8 1991.22
   355.5  1991.5   368.3 1994.75   423.8 1997.47   432.3 1999.81     442 2005.53
   457.5 2007.86   483.5 2010.11   487.8 2011.64   504.9 2024.54   509.1 2026.91
   529.8 2028.53   541.8 2031.56   549.8 2035.54   565.8 2039.68   595.8  2045.4
#Mann= 3 ,-1,0
       0      .1       0  200.94    .045       0  329.75      .1       0
Bank Sta=200.94,329.75
XS Rating Curve= 0 ,0
Exp/Cntr(USF)=0,0
Exp/Cntr=0.3,0.1

Type RM Length L Ch R = 1 ,71764   ,455.8,455.8,455.8
XS GIS Cut Line= 2
2239872.74082042669323.5847460292239906.06650371669955.507575979
#Sta/Elev= 30
       0 2059.55    13.6 2059.39    17.6 2057.97    37.6 2040.99    49.7 2036.66
    61.7 2028.95    81.7 2014.06    97.7 1996.91  111.051985.995   117.8 1982.97
   141.8 1982.22   173.8 1982.28  192.741985.995   201.9 1987.31   213.9 1986.32
     278 1993.88   354.1 1994.96   382.1 1992.67   389.1 1993.78   398.1 1997.84
   418.2 1998.37   438.2 2001.07   482.3 1999.83   498.3 2002.05   506.3 2004.72
   518.3 2002.94   546.4 2004.41   582.4 2012.12   602.2 2013.52   632.8  2022.1
#Mann= 3 ,-1,0
       0      .1       0  111.05    .045       0  192.74      .1       0
#XS Ineff= 2 , 0
                          354.15         2003.62
Permanent Ineff=
       F       F
Bank Sta=111.05,192.74
XS Rating Curve= 0 ,0
Exp/Cntr(USF)=0,0
Exp/Cntr=0.3,0.1

Type RM Length L Ch R = 1 ,71308   ,445.1,445.1,445.1
XS GIS Cut Line= 2
2239373.30204547669440.2812830822239627.62536388669983.714489387
#Sta/Elev= 30
       0 2056.44     5.4 2055.34    23.9    2047    32.9 2045.17    40.7 2041.17
      54 2039.53   124.6 2018.18   137.9 2008.74   151.1    1995   156.3 1990.51
   162.3 1986.07  166.351984.324   177.3 1981.96   190.9 1981.59   258.6 1981.71
     266  1982.3   273.21984.325     319  1993.7   327.8 1992.66   349.9 1994.28
   363.1 1989.31   372.9 1989.22   393.9 1992.77   402.9 1995.19   433.8 1991.52
   486.8 1997.01   539.8 1998.67   566.3 2005.11   588.4 2005.64     600 2009.77
#Mann= 3 ,-1,0
       0      .1       0  166.35    .045       0   273.2      .1       0
#XS Ineff= 2 , 0
                          348.67          1999.8
Permanent Ineff=
       F       F
Bank Sta=166.35,273.2
XS Rating Curve= 0 ,0
Exp/Cntr(USF)=0,0
Exp/Cntr=0.3,0.1

Type RM Length L Ch R = 1 ,70863   ,413.8,413.8,413.8
XS GIS Cut Line= 2
2238966.87723878669608.5719449342239223.50585968670150.920311698
#Sta/Elev= 30
       0 2035.29    22.8 2028.27    31.6 2027.15    40.5 2023.28    52.5 2022.32
    87.2 2012.02   133.4 2003.42   151.1 2001.29   160.6 1998.43   177.7 1997.83
   187.7 1994.68   204.2 1986.28  215.361982.524   221.9 1980.37   235.2 1980.05
   328.1 1980.07     337 1980.97  339.631982.526   350.3 1988.37   376.9 1989.98
   390.1 1993.66   394.5 1993.78   412.2 1990.07   438.8 1991.78   456.5 1996.21
   500.7 1998.75   505.1 1999.83   518.4 2007.34   554.8 2018.36     600 2035.78
#Mann= 3 ,-1,0
       0      .1       0  215.36    .045       0  339.63      .1       0
#XS Ineff= 2 , 0
                          394.46         1998.17
Permanent Ineff=
       F       F
Bank Sta=215.36,339.63
XS Rating Curve= 0 ,0
Exp/Cntr(USF)=0,0
Exp/Cntr=0.3,0.1

Type RM Length L Ch R = 1 ,70449   ,474.8,474.8,474.8
XS GIS Cut Line= 2
2238655.03707264669689.4969136382238752.41783478670272.010477048
#Sta/Elev= 30
       0 2029.75     7.8 2027.75      32 2017.15    52.8 2011.94    76.7 2003.69
    87.6 2002.39   113.2 1994.86   129.5 1992.59   145.7 1993.24   157.8 1991.29
   198.4  1990.3   210.6 1989.19   226.6 1985.12   268.3 1983.91  287.891981.344
   307.9 1978.06   348.2 1977.72   376.8 1977.94  385.751981.347   393.1 1989.04
   414.2 1989.76   449.8 2000.94     462 2001.82   486.3  2012.9   494.4 2014.42
   510.7 2021.16   522.8 2022.97   530.9 2027.11   583.7 2046.03   590.6 2050.01
#Mann= 3 ,-1,0
       0      .1       0  287.89    .045       0  385.75      .1       0
Bank Sta=287.89,385.75
XS Rating Curve= 0 ,0
Exp/Cntr(USF)=0,0
Exp/Cntr=0.3,0.1