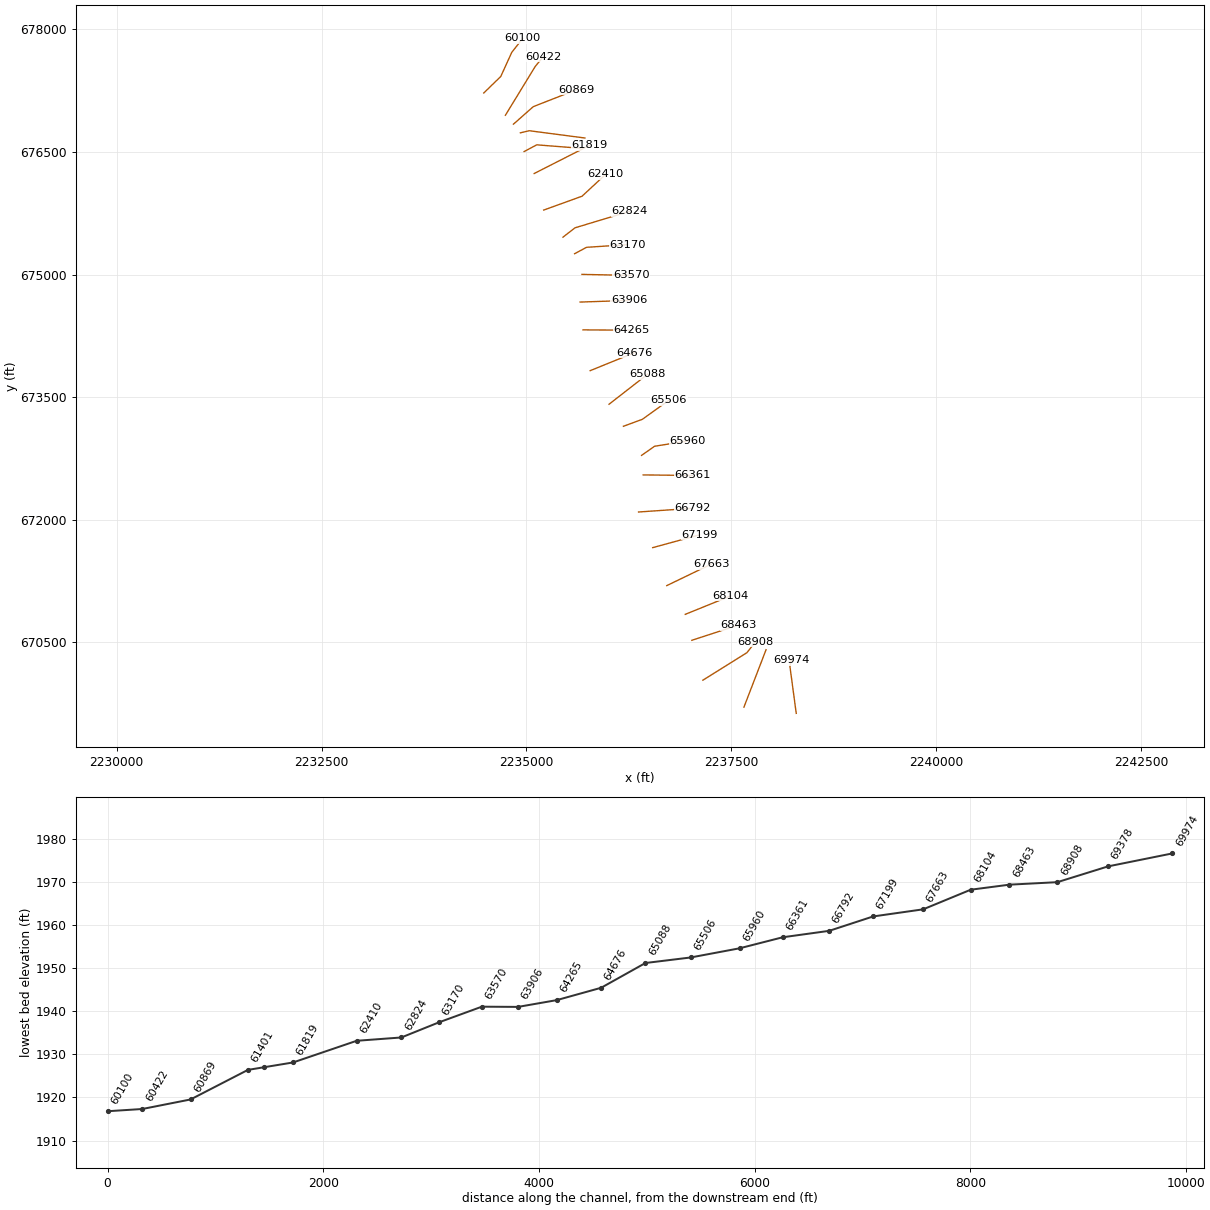
HEC-RAS study MIDFKRIV.prj: MIDFKRIV

--- MIDFKRIV.g01 (geometry) --- (continued)

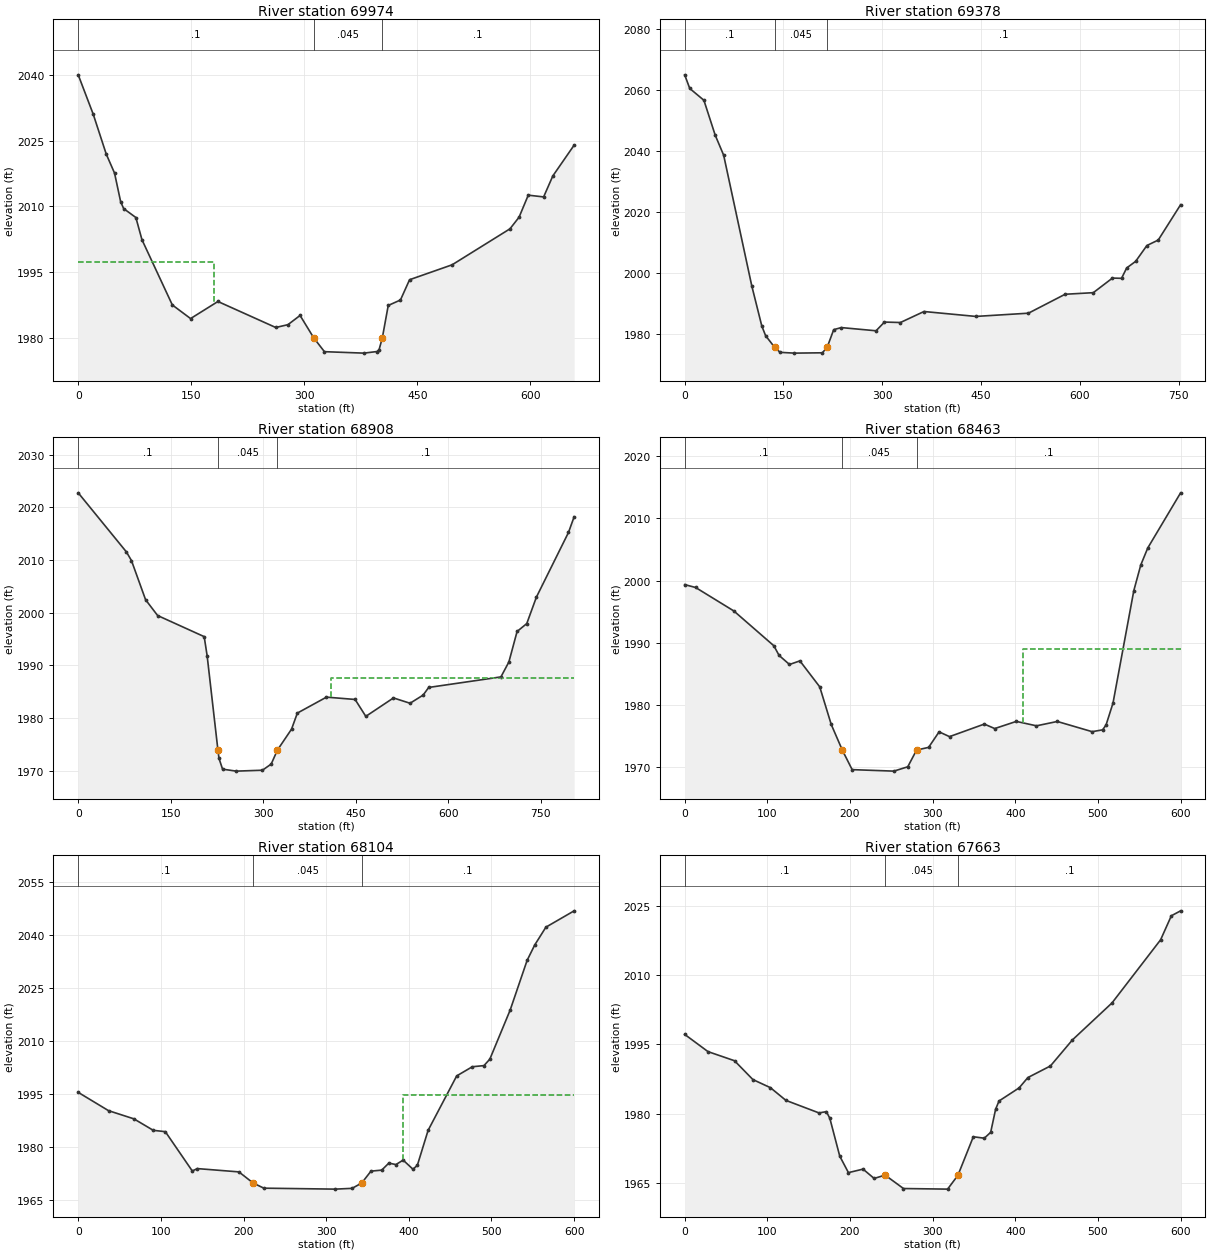
Type RM Length L Ch R = 1 ,69974   ,596.8,596.8,596.8
XS GIS Cut Line= 3
2238294.20497394669629.3680622512238217.43759386670204.072293397
2238231.93704663670281.016299808
#Sta/Elev= 30
       0 2039.98      20 2030.97    37.2 2021.92    48.2  2017.6    56.3 2011.09
    60.3 2009.51    76.5 2007.48    84.6 2002.42   124.9 1987.56   149.1 1984.46
   185.4 1988.35   262.1 1982.43   278.3 1983.07   294.4 1985.17   312.51980.079
   326.7 1976.92   379.1 1976.59   396.8 1976.96   399.3 1977.41  403.561980.073
   411.4 1987.45   427.6 1988.69   439.7 1993.31   496.2 1996.71   572.9  2004.9
     585 2007.55   597.2 2012.57   617.6 2012.17   629.8 2016.95   658.1 2023.97
#Mann= 3 ,-1,0
       0      .1       0   312.5    .045       0  403.56      .1       0
#XS Ineff= 2 , 0
          180.05 1997.26
Permanent Ineff=
       F       F
Bank Sta=312.5,403.56
XS Rating Curve= 0 ,0
Exp/Cntr(USF)=0,0
Exp/Cntr=0.3,0.1

Type RM Length L Ch R = 1 ,69378   ,470,470,470
XS GIS Cut Line= 2
2237656.09163537669705.9522400392237926.19464898 670408.91323236
#Sta/Elev= 30
       0 2064.87     7.7  2060.4    29.2 2056.52    46.3 2045.11    59.2  2038.5
     102 1995.53   117.1 1982.49   122.9  1979.3  136.441975.531   144.9 1973.84
   166.3 1973.58   209.1 1973.69  216.451975.532   226.3 1981.28   237.8 1981.96
   290.6 1980.91   303.4 1983.77   327.6 1983.62   363.4 1987.23   442.1 1985.62
     522 1986.68   577.7 1992.89   620.5 1993.41   649.6  1998.2   663.4 1998.12
   671.2 2001.52   684.8 2003.68   701.9 2008.88   719.1 2010.67   753.1 2022.27
#Mann= 3 ,-1,0
       0      .1       0  136.44    .045       0  216.45      .1       0
Bank Sta=136.44,216.45
XS Rating Curve= 0 ,0
Exp/Cntr(USF)=0,0
Exp/Cntr=0.3,0.1

Type RM Length L Ch R = 1 ,68908   ,444.3,444.3,444.3
XS GIS Cut Line= 3
2237155.06882524 670035.722925672237692.07548972670371.926575633
2237797.90200922670505.367636819
#Sta/Elev= 30
       0 2022.77    78.1 2011.55    86.3 2009.91   109.2 2002.47   128.7 1999.47
   204.2 1995.46     209 1991.82  226.451973.932   228.2 1972.34     234 1970.29
   256.1 1969.92   298.6 1970.09   312.8 1971.26  322.991973.934   345.8 1977.89
   355.2 1980.94   402.4 1983.97   448.8 1983.53   466.2 1980.32     511 1983.82
   537.9 1982.81   559.1 1984.36   568.1 1985.81   685.2 1987.81   698.1 1990.65
   711.4 1996.44   727.1 1997.94   742.7 2002.96   794.7 2015.24   803.9 2018.23
#Mann= 3 ,-1,0
       0      .1       0  226.45    .045       0  322.99      .1       0
#XS Ineff= 2 , 0
                          409.27          1987.7
Permanent Ineff=
       F       F
Bank Sta=226.45,322.99
XS Rating Curve= 0 ,0
Exp/Cntr(USF)=0,0
Exp/Cntr=0.3,0.1

Type RM Length L Ch R = 1 ,68463   ,359.2,359.2,359.2
XS GIS Cut Line= 2
2237019.65229305670523.6412309022237589.94134368670710.109455364
#Sta/Elev= 30
       0 1999.35    13.2 1998.89    59.5 1995.11   107.9 1989.51   114.2 1987.96
   126.8  1986.5   139.4 1987.08   163.4  1982.9   177.3 1976.85  190.671972.733
   202.6 1969.58   253.1 1969.34   269.9 1970.04  280.561972.734   295.1 1973.16
   307.8 1975.66   320.4 1974.89   362.5 1976.91   375.1 1976.19   401.2 1977.34
   425.6 1976.63   450.8 1977.33   492.9 1975.69   505.6 1975.98   509.8 1976.77
   518.2 1980.29   543.4  1998.4   551.8 2002.51   560.3 2005.26     600 2014.12
#Mann= 3 ,-1,0
       0      .1       0  190.67    .045       0  280.56      .1       0
#XS Ineff= 2 , 0
                          408.74         1988.97
Permanent Ineff=
       F       F
Bank Sta=190.67,280.56
XS Rating Curve= 0 ,0
Exp/Cntr(USF)=0,0
Exp/Cntr=0.3,0.1

Type RM Length L Ch R = 1 ,68104   ,441.1,441.1,441.1
XS GIS Cut Line= 2
2236940.11184288670841.4246453022237495.83344884 671067.64024307
#Sta/Elev= 30
       0  1995.5    36.7 1990.33    67.4 1988.02    90.8 1984.78   105.4  1984.4
     138  1973.3   144.1 1973.97   194.4 1973.04  211.691969.886   224.6 1968.44
     311 1968.17   331.3 1968.39  342.971969.886   354.2 1973.25   367.2 1973.54
   375.8 1975.52   384.4 1975.11   393.1 1976.37     405 1973.79   410.3  1974.9
   423.3 1984.77   457.9 2000.15   476.8 2002.74   490.9 2003.06     498 2004.89
   522.6 2018.76   543.1 2032.79   552.3 2037.13   565.8 2042.16     600 2046.78
#Mann= 3 ,-1,0
       0      .1       0  211.69    .045       0  342.97      .1       0
#XS Ineff= 2 , 0
                          392.35         1994.83
Permanent Ineff=
       F       F
Bank Sta=211.69,342.97
XS Rating Curve= 0 ,0
Exp/Cntr(USF)=0,0
Exp/Cntr=0.3,0.1

Type RM Length L Ch R = 1 ,67663   ,463.7,463.7,463.7
XS GIS Cut Line= 2
2236713.89562237 671192.88840488 2237253.9541995671454.301360321
#Sta/Elev= 30
       0 1997.19    28.2 1993.45    60.3 1991.47    82.5 1987.39   103.7 1985.63
   122.5 1982.87   162.5 1980.15   171.4 1980.43   175.6 1978.99   187.6 1970.78
   198.1  1967.2   215.8 1967.96   229.2 1965.94   242.5 1966.66   264.7 1963.75
   318.1 1963.62  330.581966.619   349.2 1974.98   362.5 1974.67   370.2 1975.94
   376.2 1980.97   380.3 1982.74   404.6 1985.58   415.2 1987.82   442.5 1990.34
   469.1 1995.99     517 2004.01   575.8 2017.71   588.8 2022.92     600 2023.99
#Mann= 3 ,-1,0
       0      .1       0   242.5    .045       0  330.58      .1       0
Bank Sta=242.5,330.58
XS Rating Curve= 0 ,0
Exp/Cntr(USF)=0,0
Exp/Cntr=0.3,0.1

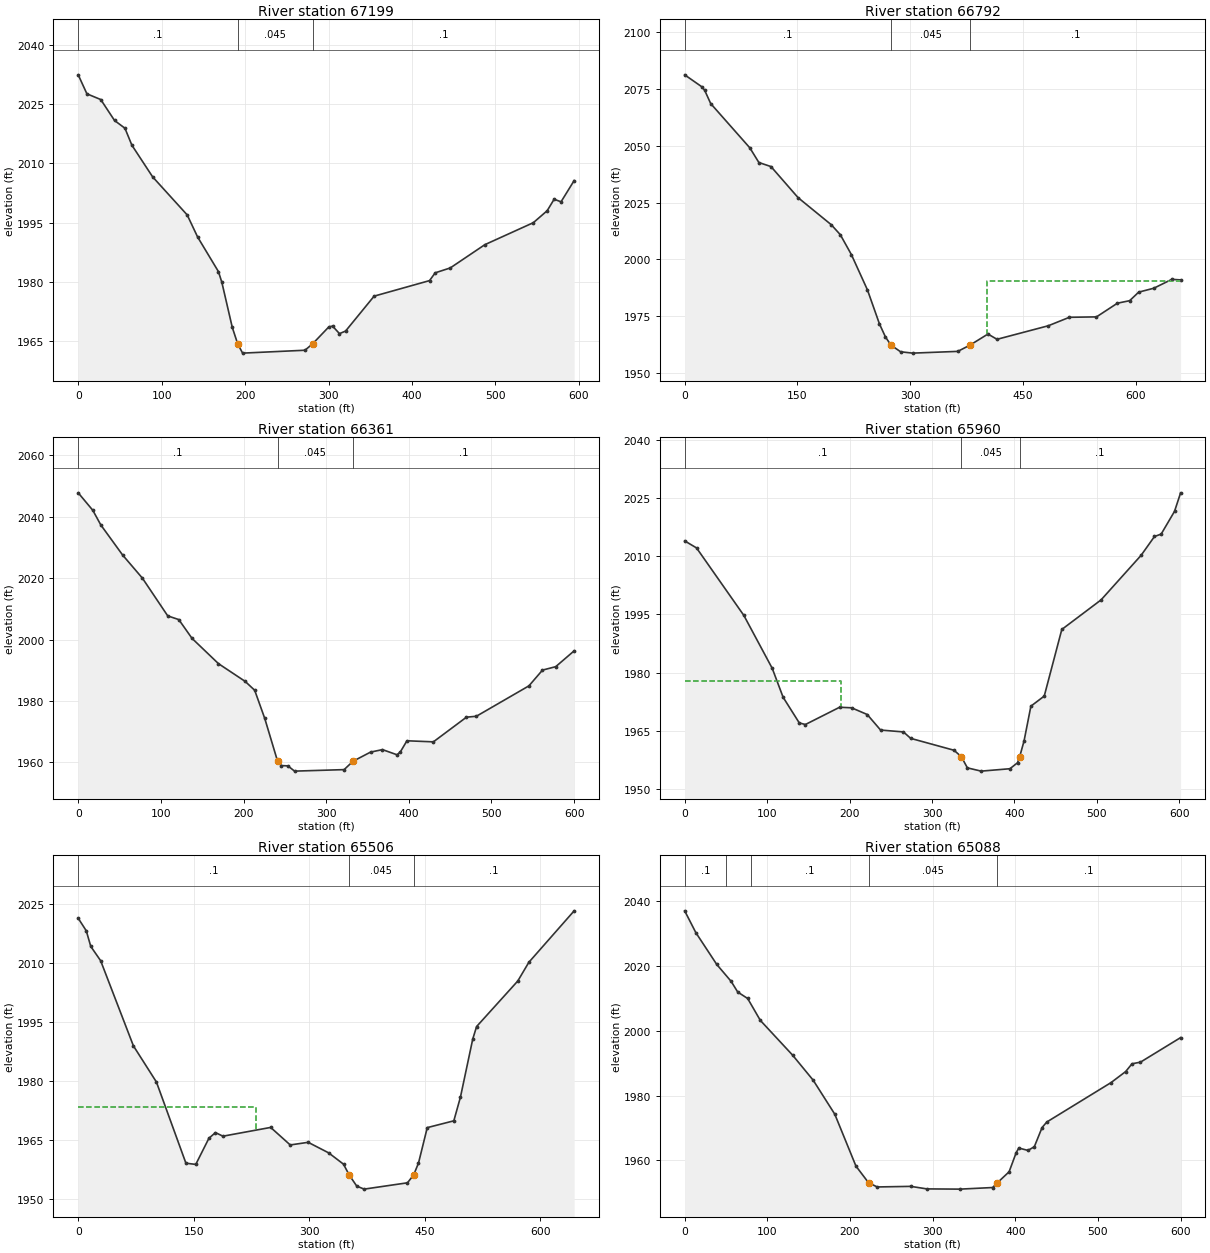
Type RM Length L Ch R = 1 ,67199   ,407.8,407.8,407.8
XS GIS Cut Line= 2
2236542.17276741671657.5859621272237115.39120025671814.581069683
#Sta/Elev= 30
       0 2032.35    10.4 2027.55      27  2026.1    43.5 2020.81      56 2018.84
    64.3 2014.56    89.2 2006.54   130.6 1996.92   143.1 1991.33     168  1982.6
   172.1  1979.9   184.6  1968.5  191.111964.304     197 1961.97   271.7  1962.7
  280.811964.305   300.4 1968.62   304.8  1968.8   313.1  1966.9   320.4 1967.55
   354.6 1976.38     421 1980.31   427.8 1982.28   445.8 1983.51   487.3  1989.4
   545.4 1994.96     562 1997.99   570.3 2000.89   578.6 2000.24   594.3 2005.61
#Mann= 3 ,-1,0
       0      .1       0  191.11    .045       0  280.81      .1       0
Bank Sta=191.11,280.81
XS Rating Curve= 0 ,0
Exp/Cntr(USF)=0,0
Exp/Cntr=0.3,0.1

Type RM Length L Ch R = 1 ,66792   ,430.8,430.8,430.8
XS GIS Cut Line= 2
 2236369.6782757672093.9997742892237027.80412134672139.173326609
#Sta/Elev= 30
       0 2081.27    22.5 2076.07    26.6 2074.46    34.6 2068.61    86.7 2049.08
    98.7 2042.63   114.8 2040.84   150.9 2027.13     195 2015.21     207 2010.83
   221.7 2002.09   243.1 1986.51   259.1  1971.5   267.1 1965.74  274.411962.157
   287.2 1959.23   303.2 1958.63   363.3  1959.4   379.51962.155   403.4 1967.04
   415.5 1964.72   483.6 1970.68   511.7 1974.42   547.8  1974.6   575.6 1980.63
   591.9 1981.74   603.9  1985.5     624 1987.23     648 1991.14   659.7  1990.9
#Mann= 3 ,-1,0
       0      .1       0  274.41    .045       0   379.5      .1       0
#XS Ineff= 1 ,-1
  401.64659.6744 1990.24
Permanent Ineff=
       F
Bank Sta=274.41,379.5
XS Rating Curve= 0 ,0
Exp/Cntr(USF)=0,0
Exp/Cntr=0.3,0.1

Type RM Length L Ch R = 1 ,66361   ,400.4,400.4,400.4
XS GIS Cut Line= 2
2236426.49242423672547.8410461382237026.45293126672540.957006504
#Sta/Elev= 30
       0 2047.83    17.7 2042.12    27.3 2037.38    53.7 2027.57    77.7 2020.01
   108.3 2007.73   121.7 2006.52   137.7  2000.4   169.7 1992.16     202 1986.38
   213.5 1983.49   225.7 1974.29  241.211960.355   245.7 1958.95   253.7 1958.85
   261.7 1957.14   321.7 1957.63  332.431960.353   353.7 1963.34   368.1 1964.15
   385.7 1962.47   389.7 1963.39   397.7 1967.03   429.7 1966.68   469.7 1974.72
   481.7 1975.02   545.3 1984.93   561.7 1990.06   577.7 1991.18     600 1996.34
#Mann= 3 ,-1,0
       0      .1       0  241.21    .045       0  332.43      .1       0
Bank Sta=241.21,332.43
XS Rating Curve= 0 ,0
Exp/Cntr(USF)=0,0
Exp/Cntr=0.3,0.1

Type RM Length L Ch R = 1 ,65960   ,454,454,454
XS GIS Cut Line= 3
2236406.60478975672786.7324979662236565.27187299672898.678504734
2236967.53204733672962.875278369
#Sta/Elev= 30
       0 2013.95    14.4 2012.13    71.8 1994.72   106.2 1981.08   119.4 1973.62
     139 1967.01   146.4  1966.6   187.9 1971.05   202.4 1970.91   221.4 1969.18
   237.6 1965.17   265.3 1964.69   274.1 1963.03   326.7 1959.96  335.521958.298
   342.9 1955.42   359.6 1954.58   394.5  1955.2   403.7 1956.74  406.311958.301
   411.6 1962.35   419.9 1971.33   436.1 1973.93   457.4 1991.11     505 1998.73
   553.6 2010.23   569.8 2015.08   577.9  2015.7   594.1 2021.56   601.5 2026.34
#Mann= 3 ,-1,0
       0      .1       0  335.52    .045       0  406.31      .1       0
#XS Ineff= 2 , 0
          189.15 1977.94
Permanent Ineff=
       F       F
Bank Sta=335.52,406.31
XS Rating Curve= 0 ,0
Exp/Cntr(USF)=0,0
Exp/Cntr=0.3,0.1

Type RM Length L Ch R = 1 ,65506   ,418.6,418.6,418.6
XS GIS Cut Line= 3
2236184.87272963673143.0439290462236416.16495214673228.283277126
2236739.09360021673460.465300726
#Sta/Elev= 30
       0 2021.37    10.5 2018.17    16.3 2014.21    29.1 2010.58    71.7  1988.9
   101.6  1979.7   139.9 1959.05   152.7 1958.74   169.8  1965.4   178.3 1966.83
     188 1965.92     250 1968.15   275.4 1963.69   298.7 1964.36   325.3 1961.68
   344.6  1958.8  351.921956.072   361.8 1953.22   371.4 1952.45   427.7 1954.06
  435.731956.071     442 1959.07   453.4  1968.1   487.9 1969.83   496.5 1975.86
   512.5 1990.65   517.5 1993.82     571 2005.41   585.3 2010.15   644.2 2023.26
#Mann= 3 ,-1,0
       0      .1       0  351.92    .045       0  435.73      .1       0
#XS Ineff= 2 , 0
           230.7 1973.32
Permanent Ineff=
       F       F
Bank Sta=351.92,435.73
XS Rating Curve= 0 ,0
Exp/Cntr(USF)=0,0
Exp/Cntr=0.3,0.1

Type RM Length L Ch R = 1 ,65088   ,411.4,411.4,411.4
XS GIS Cut Line= 2
2236009.59861781673412.8661030372236482.50849832 673782.13056777
#Sta/Elev= 30
       0 2036.92    13.5  2030.2    38.8  2020.4    56.2 2015.19    64.2 2011.89
    76.2 2009.91    91.5 2003.17   130.5 1992.47   155.5 1984.72   181.6 1974.26
   207.2 1958.27  222.441953.145   232.9 1951.84   273.5 1952.02     293 1951.24
   333.1 1951.17   372.5 1951.66  378.351953.142   392.5 1956.51     401 1962.36
   404.2 1963.83   415.3  1963.1     423 1964.23   432.4 1970.15   438.1 1971.85
   515.8 1983.99   533.5 1987.39   541.2 1989.79   551.4 1990.29     600 1997.86
#Mann= 5 ,-1,0
       0      .1       0      50     .05       0      80      .1       0
  222.44    .045       0  378.35      .1       0
Bank Sta=222.44,378.35
XS Rating Curve= 0 ,0
Exp/Cntr(USF)=0,0
Exp/Cntr=0.3,0.1

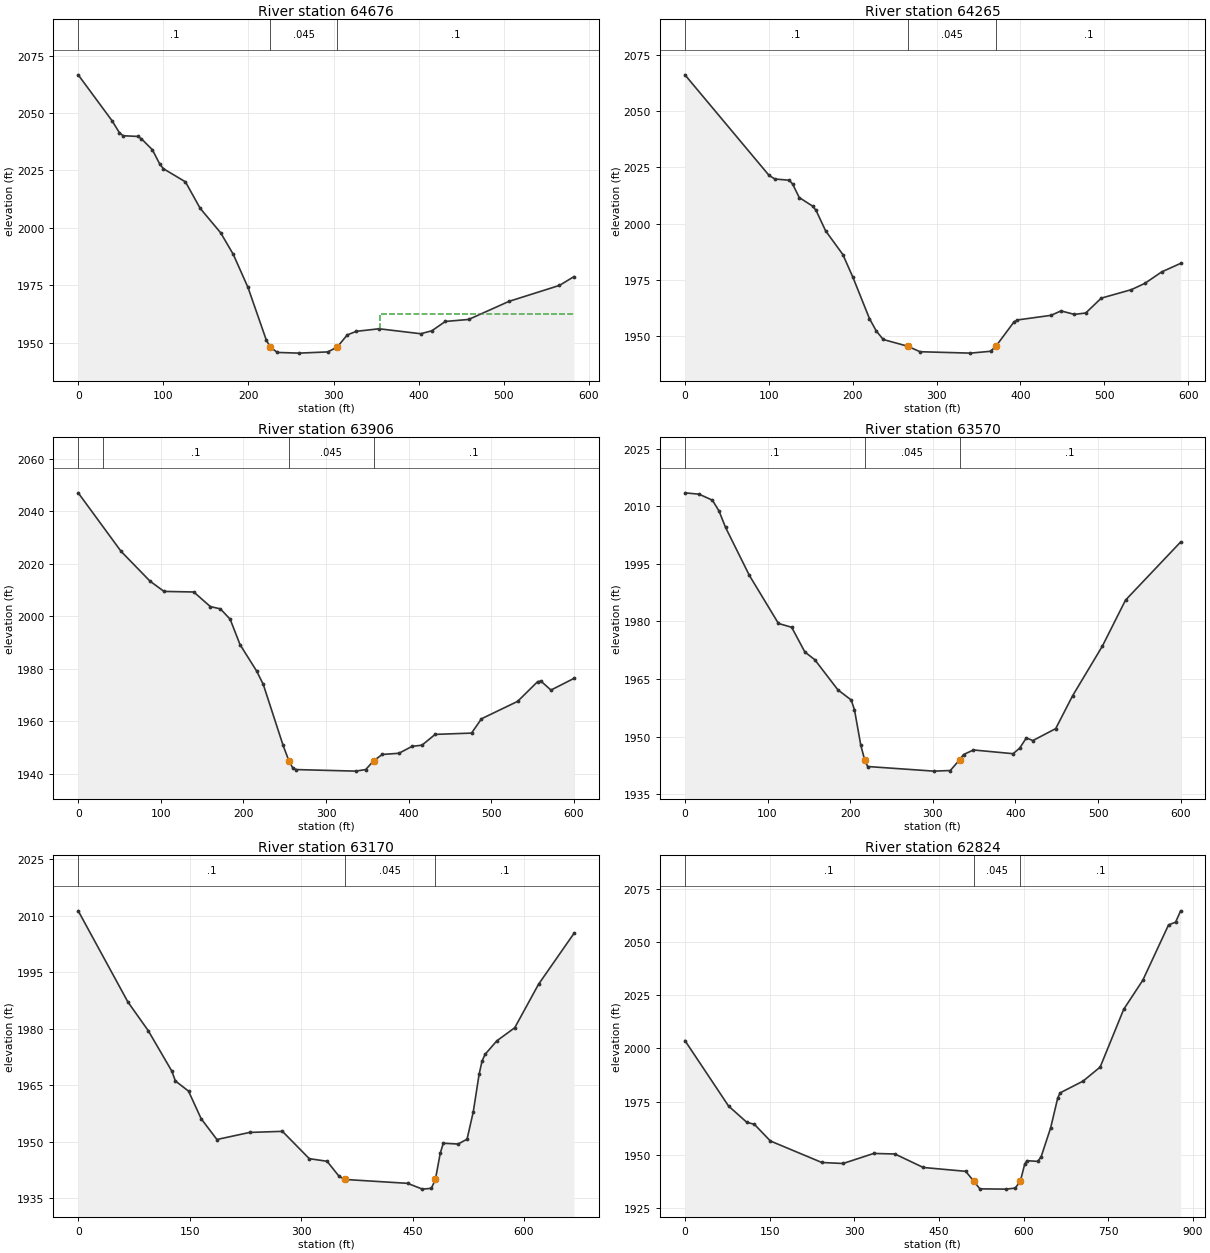
Type RM Length L Ch R = 1 ,64676   ,411.3,411.3,411.3
XS GIS Cut Line= 2
2235779.46071465673823.694514917 2236318.7460425674043.586643667
#Sta/Elev= 30
       0 2066.68    39.6 2046.76    48.3 2041.55    52.6 2040.14    69.9 2039.85
    74.2 2038.84    87.2 2034.02    95.8 2027.81   100.1 2025.78     126 2020.05
   143.3 2008.51   167.4 1997.85   182.2 1988.45   199.5 1974.03   221.1    1951
  225.851948.004     234 1945.72   259.4 1945.42   293.2 1945.95  304.161948.003
   316.1 1953.36   326.8 1954.92   353.5 1956.03   402.5 1953.87   415.5 1955.16
   431.3 1959.22   458.7 1960.09   506.2 1967.98   565.4 1974.92   582.4 1978.74
#Mann= 3 ,-1,0
       0      .1       0  225.85    .045       0  304.16      .1       0
#XS Ineff= 1 ,-1
  354.57582.3926 1962.41
Permanent Ineff=
       F
Bank Sta=225.85,304.16
XS Rating Curve= 0 ,0
Exp/Cntr(USF)=0,0
Exp/Cntr=0.3,0.1

Type RM Length L Ch R = 1 ,64265   ,358.7,358.7,358.7
XS GIS Cut Line= 2
2235691.89776188674322.8723383552236282.77469718674318.955627515
#Sta/Elev= 30
       0 2066.09   100.3 2021.44   107.3 2019.84   124.3 2019.31   128.3 2017.65
   136.3 2011.61   152.3 2007.79   156.3 2005.93   167.7 1996.85   188.3 1986.29
   200.3 1976.17     220 1957.87   228.1  1952.4   236.4 1948.61  265.331945.649
   280.3 1943.18   340.3 1942.56   364.3 1943.38  370.74 1945.65   392.3 1956.43
   396.3 1957.28   436.3 1959.33   448.3  1961.3   464.3 1959.75   477.8 1960.38
   496.3 1966.97   532.3 1970.75   548.3 1973.54   568.3 1978.61   590.9  1982.4
#Mann= 3 ,-1,0
       0      .1       0  265.33    .045       0  370.74      .1       0
Bank Sta=265.33,370.74
XS Rating Curve= 0 ,0
Exp/Cntr(USF)=0,0
Exp/Cntr=0.3,0.1

Type RM Length L Ch R = 1 ,63906   ,335.8,335.8,335.8
XS GIS Cut Line= 2
2235656.33929422674663.2497635252236256.00655484674683.229166188
#Sta/Elev= 30
       0 2047.02    51.9 2024.72    86.9 2013.38   103.9 2009.46   139.9 2009.24
   159.9 2003.69   172.1 2002.81   183.9 1998.88   195.9 1989.18     216 1979.12
     224 1974.04     248 1950.81  255.051944.911     260 1942.04     264 1941.58
     336 1940.99     348 1941.59  357.531944.909     368 1947.34   388.1 1947.79
   404.1 1950.42   416.1 1950.88   432.1 1954.99   476.1 1955.48   488.1 1960.93
   531.9 1967.57   556.1 1975.08   560.1 1975.29   572.2 1971.87     600 1976.31
#Mann= 4 ,-1,0
       0     .08       0      30      .1       0  255.05    .045       0
  357.53      .1       0
Bank Sta=255.05,357.53
XS Rating Curve= 0 ,0
Exp/Cntr(USF)=0,0
Exp/Cntr=0.3,0.1

Type RM Length L Ch R = 1 ,63570   ,400.5,400.5,400.5
XS GIS Cut Line= 2
  2235679.024037675001.9069044942236278.89769477674989.594523626
#Sta/Elev= 30
       0  2013.5    17.2 2013.14    33.2 2011.59    41.2  2008.8    49.2 2004.48
      78    1992   113.2 1979.49   129.2 1978.49   145.2 1972.05   157.2 1970.05
   185.2 1962.19   201.2 1959.57   205.2 1957.04   212.8 1947.87  217.481944.009
   221.2 1942.24   301.2 1941.04   321.2  1941.2  332.53 1944.01   337.2 1945.35
   349.2 1946.55   397.2 1945.58   405.2 1947.03   413.2 1949.68   421.2    1949
   448.8 1952.11   469.2 1960.65   505.3  1973.6   533.3 1985.57     600  2000.7
#Mann= 3 ,-1,0
       0      .1       0  217.48    .045       0  332.53      .1       0
Bank Sta=217.48,332.53
XS Rating Curve= 0 ,0
Exp/Cntr(USF)=0,0
Exp/Cntr=0.3,0.1

Type RM Length L Ch R = 1 ,63170   ,345.7,345.7,345.7
XS GIS Cut Line= 3
2235589.26737443675254.9707506932235734.98175587675333.437567465
2236235.65973385675365.512585334
#Sta/Elev= 30
       0 2011.35    66.9 1987.12    94.2 1979.52     126 1968.75   130.8 1966.14
   148.5 1963.43   165.5 1956.09   186.7 1950.57   230.8 1952.45   274.9 1952.74
     311 1945.48     335 1944.78   351.2 1940.77   359.1 1939.95   443.3 1938.92
   463.3 1937.38   475.3 1937.59  480.781939.948   487.3 1946.91   491.4 1949.58
   511.4 1949.36   523.4 1950.66   531.8 1957.97   539.6 1967.89   543.5 1971.37
   547.5 1973.17   563.5  1976.8   587.6 1980.28   619.6 1991.83   667.2 2005.33
#Mann= 3 ,-1,0
       0      .1       0   359.1    .045       0  480.78      .1       0
Bank Sta=359.1,480.78
XS Rating Curve= 0 ,0
Exp/Cntr(USF)=0,0
Exp/Cntr=0.3,0.1

Type RM Length L Ch R = 1 ,62824   ,414.4,414.4,414.4
XS GIS Cut Line= 3
2235447.22307809675457.667701812 2235593.7225677675571.812447499
2236256.66717727675772.252990306
#Sta/Elev= 30
       0 2003.68    77.3 1972.93   109.8 1965.24   122.9 1964.38   151.4 1956.51
   242.6 1946.41   280.2 1945.94   334.5 1950.66   372.1  1950.4   422.3 1944.07
   497.5 1942.26   511.41937.758   522.6 1934.03   568.6  1933.9   585.3 1934.38
  594.38 1937.76     602 1945.57   605.9 1947.26   625.2 1946.93   631.2 1949.15
     648  1962.7   660.5 1976.66   664.7 1979.11   705.4 1984.63   735.7 1991.23
   777.5 2018.39   811.3 2032.03   856.9 2058.01   869.4 2059.29   878.3 2064.61
#Mann= 3 ,-1,0
       0      .1       0   511.4    .045       0  594.38      .1       0
Bank Sta=511.4,594.38
XS Rating Curve= 0 ,0
Exp/Cntr(USF)=0,0
Exp/Cntr=0.3,0.1

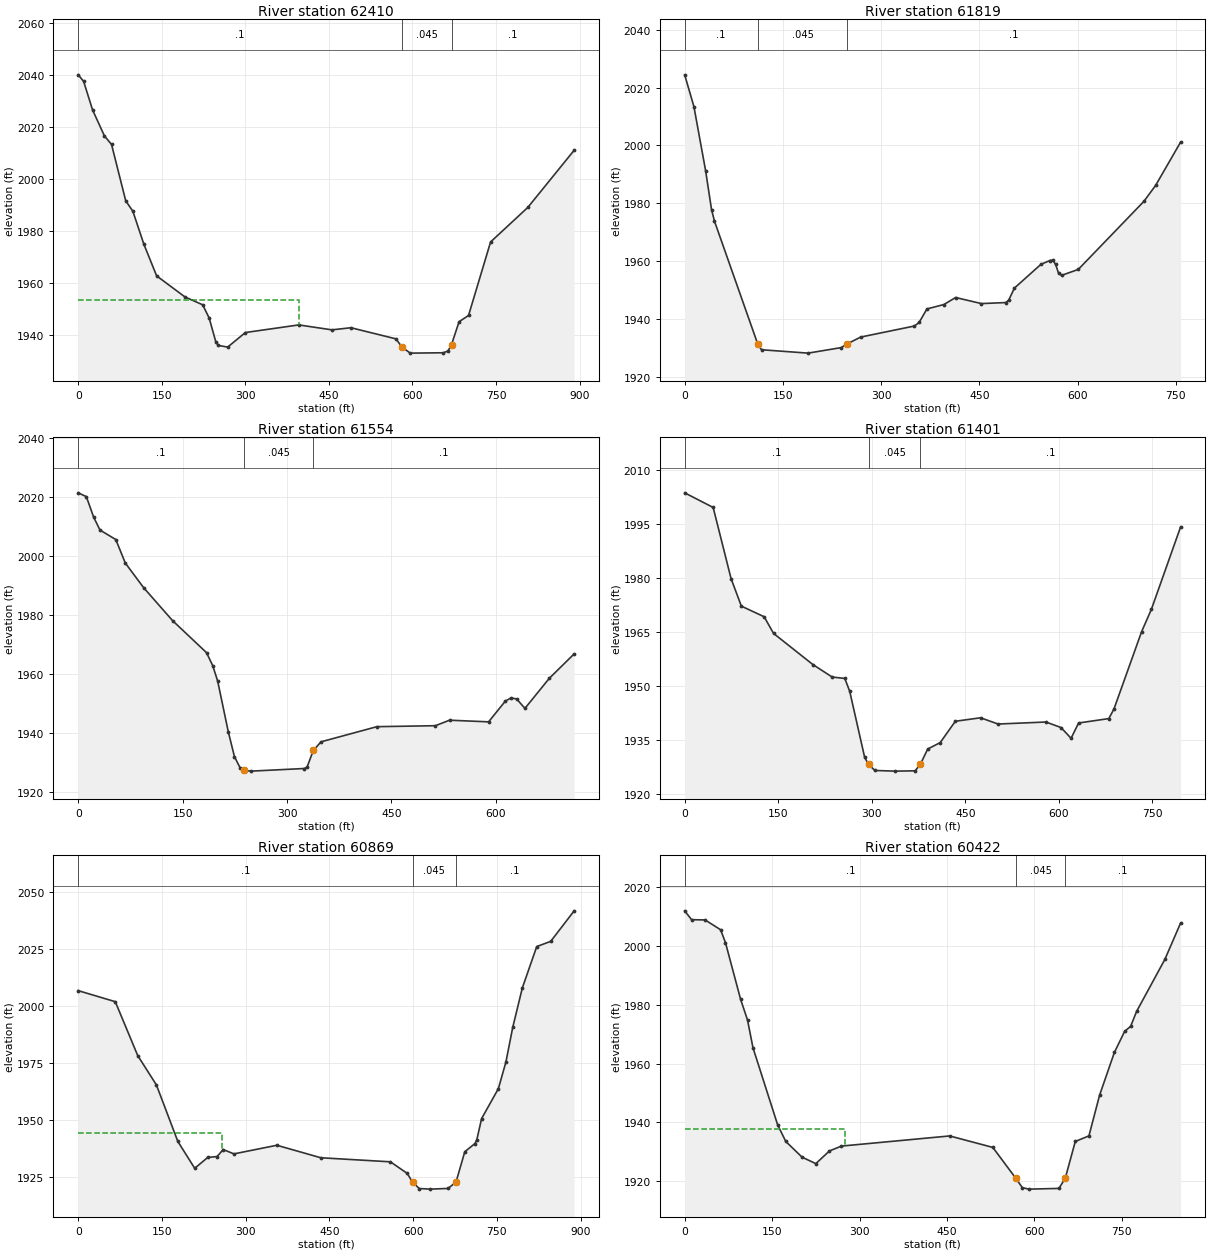
Type RM Length L Ch R = 1 ,62410   ,590.3,590.3,590.3
XS GIS Cut Line= 3
2235211.94818676675789.0187944422235680.22869187675958.833445582
2235967.35610769676225.910611337
#Sta/Elev= 30
       0 2040.16     9.7 2037.65    25.8 2026.65      47 2016.69    59.8  2013.4
    85.3 1991.71    98.1  1987.7   117.8 1975.05   140.8 1962.83   191.7 1954.73
   223.4 1951.72   235.1 1946.63     247 1937.47   251.3 1936.11   268.3 1935.45
   300.1 1941.05   395.9 1943.98   455.5 1942.08   489.6  1942.9   570.5 1938.61
   580.9 1935.53     596 1933.13   655.4 1933.27   663.9 1933.96   670.2 1936.43
   683.7 1945.21   700.7 1947.61   740.3 1975.89     807 1989.14   890.3 2011.15
#Mann= 3 ,-1,0
       0      .1       0   580.9    .045       0   670.2      .1       0
#XS Ineff= 2 , 0
           395.7 1953.42
Permanent Ineff=
       F       F
Bank Sta=580.9,670.2
XS Rating Curve= 0 ,0
Exp/Cntr(USF)=0,0
Exp/Cntr=0.3,0.1

Type RM Length L Ch R = 1 ,61819   ,265.1,265.1,265.1
XS GIS Cut Line= 2
2235095.63232704676236.370654162 2235770.1850508676580.140959731
#Sta/Elev= 30
       0 2024.43    14.1 2013.43      32  1991.2      41 1977.78    45.5 1973.76
  111.381931.351   117.3 1929.27   188.4  1928.1   238.9 1930.01  248.491931.349
   268.7 1933.66   350.8 1937.49   357.9 1938.71   369.8 1943.39   395.7 1944.92
   413.6 1947.35     453 1945.25     490  1945.6   494.5 1946.37   503.4 1950.62
   543.8 1958.82   557.3 1960.14   561.8 1960.33   566.3  1958.8   570.8 1955.73
   575.3 1955.02   600.8 1957.06     701 1980.62   718.9 1986.14   757.1 2001.14
#Mann= 3 ,-1,0
       0      .1       0  111.38    .045       0  248.49      .1       0
Bank Sta=111.38,248.49
XS Rating Curve= 0 ,0
Exp/Cntr(USF)=0,0
Exp/Cntr=0.3,0.1

Type RM Length L Ch R = 1 ,61554   ,153,153,153
XS GIS Cut Line= 3
2234972.57964715676504.9348175612235127.10350803676587.464606896
2235662.66916222676545.321735746
#Sta/Elev= 30
       0 2021.49    11.7 2020.19    22.2 2013.22    31.3 2008.84      54 2005.63
    67.6 1997.67    93.9 1989.31   135.6 1978.09   184.3 1967.24   193.2 1962.83
   200.3 1957.61   215.5 1940.46   224.4 1931.94   232.4 1928.21   237.8 1927.27
   248.5 1927.01   324.7  1927.9   328.7 1928.34   337.71934.025   348.8 1936.96
     429  1942.1   513.1 1942.43   533.4  1944.3   589.5 1943.74   613.6 1950.79
   621.6 1951.85   629.7 1951.53   641.7 1948.31   676.7 1958.52   712.4 1966.81
#Mann= 3 ,-1,0
       0      .1       0   237.8    .045       0   337.7      .1       0
Bank Sta=237.8,337.7
XS Rating Curve= 0 ,0
Exp/Cntr(USF)=0,0
Exp/Cntr=0.3,0.1

Type RM Length L Ch R = 1 ,61401   ,532.2,532.2,532.2
XS GIS Cut Line= 3
2234927.73606764676734.7215951042235035.74877443676760.155367963
2235714.39819153676671.078144692
#Sta/Elev= 30
       0 2003.56    45.7  1999.5    74.4 1979.77    90.9 1972.14   127.5 1969.19
   142.5 1964.58   205.5 1955.95   236.5 1952.48   256.8 1952.08   264.7 1948.51
   288.7 1930.16  294.951928.259     305 1926.56   337.3 1926.38   369.6 1926.46
  377.931928.259   389.8 1932.51   409.9  1934.3   434.1 1940.21   474.5 1941.17
   502.7 1939.44   579.4    1940   603.6 1938.46   619.7 1935.49   631.8 1939.73
   680.2 1940.95   688.5 1943.61   732.7 1964.99   748.6 1971.29   795.4 1994.12
#Mann= 3 ,-1,0
       0      .1       0  294.95    .045       0  377.93      .1       0
Bank Sta=294.95,377.93
XS Rating Curve= 0 ,0
Exp/Cntr(USF)=0,0
Exp/Cntr=0.3,0.1

Type RM Length L Ch R = 1 ,60869   ,447.3,447.3,447.3
XS GIS Cut Line= 3
2234842.42050583676840.3948450272235085.18949029677055.033923264
2235610.54572348677261.229651983
#Sta/Elev= 30
       0  2006.8    66.4 2001.95   106.6 1978.25   140.1 1965.33   178.5 1940.47
   208.7 1928.68   231.9 1933.43   248.8 1933.86   259.7 1936.92     279 1935.02
   355.8 1938.81   434.7 1933.31   559.3 1931.53   589.4 1926.43  598.851922.605
   610.9 1919.78   630.4 1919.52   662.4 1919.82  676.771922.609   692.5 1935.97
   710.7 1939.56     714 1941.19   722.6 1950.53   752.7 1963.72   766.2 1975.46
   778.4 1990.67   795.6 2008.01   821.4 2026.19   846.4 2028.47   888.4  2041.9
#Mann= 3 ,-1,0
       0      .1       0  598.85    .045       0  676.77      .1       0
#XS Ineff= 2 , 0
          258.34 1944.02
Permanent Ineff=
       F       F
Bank Sta=598.85,676.77
XS Rating Curve= 0 ,0
Exp/Cntr(USF)=0,0
Exp/Cntr=0.3,0.1

Type RM Length L Ch R = 1 ,60422   ,321.7,321.7,321.7
XS GIS Cut Line= 3
2234744.07229634676949.1253293652235108.14410837677545.909602149
2235203.80954271677663.736417645
#Sta/Elev= 30
       0 2012.02    11.8 2009.01      35 2008.92    61.6 2005.59      70 2001.18
      96 1981.86   107.8 1974.86   117.2  1965.4   159.4 1939.24   173.4 1933.54
   201.5 1928.17     225 1925.99   248.4 1930.31     269 1931.96   454.6 1935.41
   528.6 1931.51  568.261920.952   579.2 1917.82   590.4 1917.31     642 1917.55
  652.811920.954   670.1 1933.53   693.5 1935.43   711.8 1949.29   737.2 1963.84
   754.8    1971   765.1 1972.72   775.4 1977.84   823.7 1995.46   850.8 2007.88
#Mann= 3 ,-1,0
       0      .1       0  568.26    .045       0  652.81      .1       0
#XS Ineff= 2 , 0
          274.73 1937.69
Permanent Ineff=
       F       F
Bank Sta=568.26,652.81
XS Rating Curve= 0 ,0
Exp/Cntr(USF)=0,0
Exp/Cntr=0.3,0.1

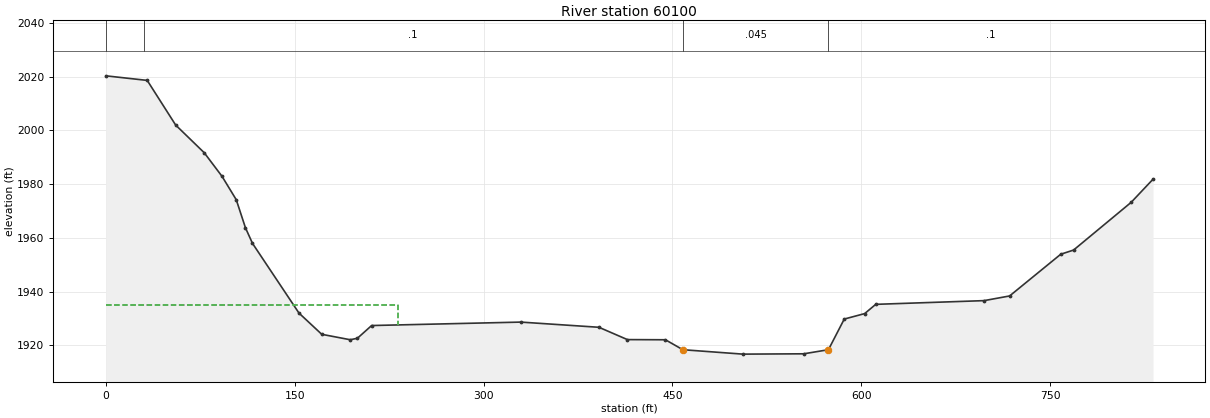
Type RM Length L Ch R = 1 ,60100   ,404.1,404.1,404.1
XS GIS Cut Line= 4
2234480.77911327677222.0468329252234687.89802357677424.073552354
2234822.09425233677718.9521076552234956.58359559677890.869211704
#Sta/Elev= 30
       0 2020.27    32.9 2018.57    55.5 2001.97    78.2 1991.66    92.3  1982.9
   103.6 1974.21   110.9 1963.78   116.5 1957.97   153.4 1932.06   171.5 1924.16
   194.1 1922.14   199.8 1922.69   211.1 1927.42   329.6  1928.7   391.6 1926.77
   414.2 1922.19   444.4 1922.13  458.231918.431   505.9 1916.79   554.2 1916.91
  573.831918.431   586.4 1929.83   602.6 1931.86   611.4  1935.3   697.4 1936.68
   717.7 1938.42   758.3 1953.93   768.5 1955.49   814.2 1973.22   831.6 1981.84
#Mann= 4 ,-1,0
       0     .08       0      30      .1       0  458.23    .045       0
  573.83      .1       0
#XS Ineff= 2 , 0
          231.77    1935
Permanent Ineff=
       F       F
Bank Sta=458.23,573.83
XS Rating Curve= 0 ,0
Exp/Cntr(USF)=0,0
Exp/Cntr=0.3,0.1