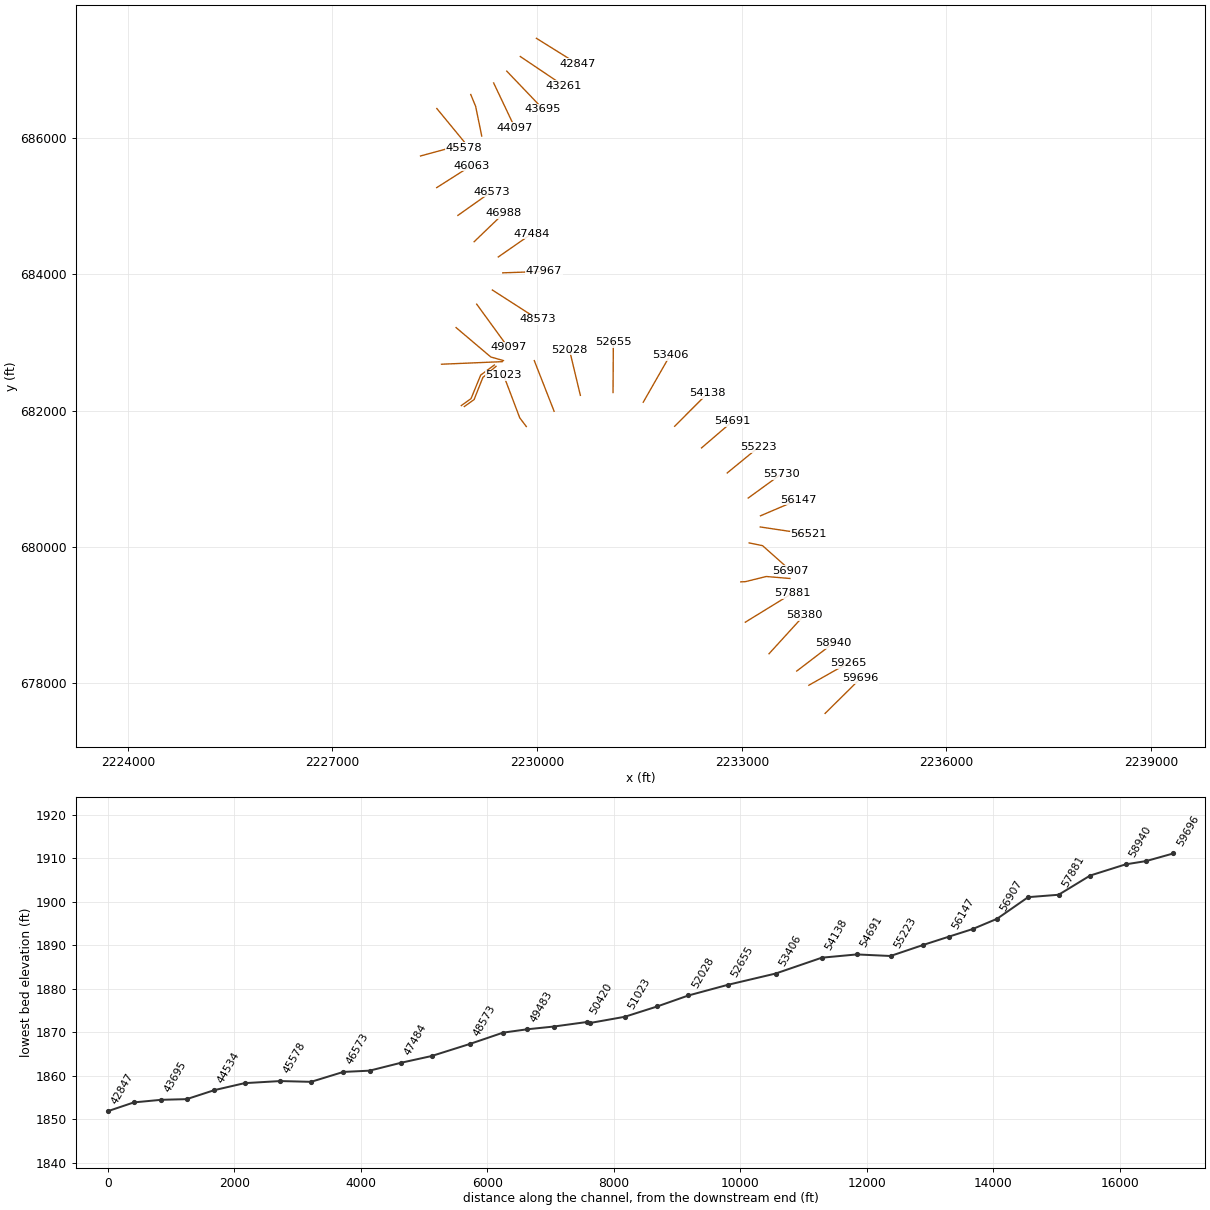
HEC-RAS study MIDFKRIV.prj: MIDFKRIV

--- MIDFKRIV.g01 (geometry) --- (continued)

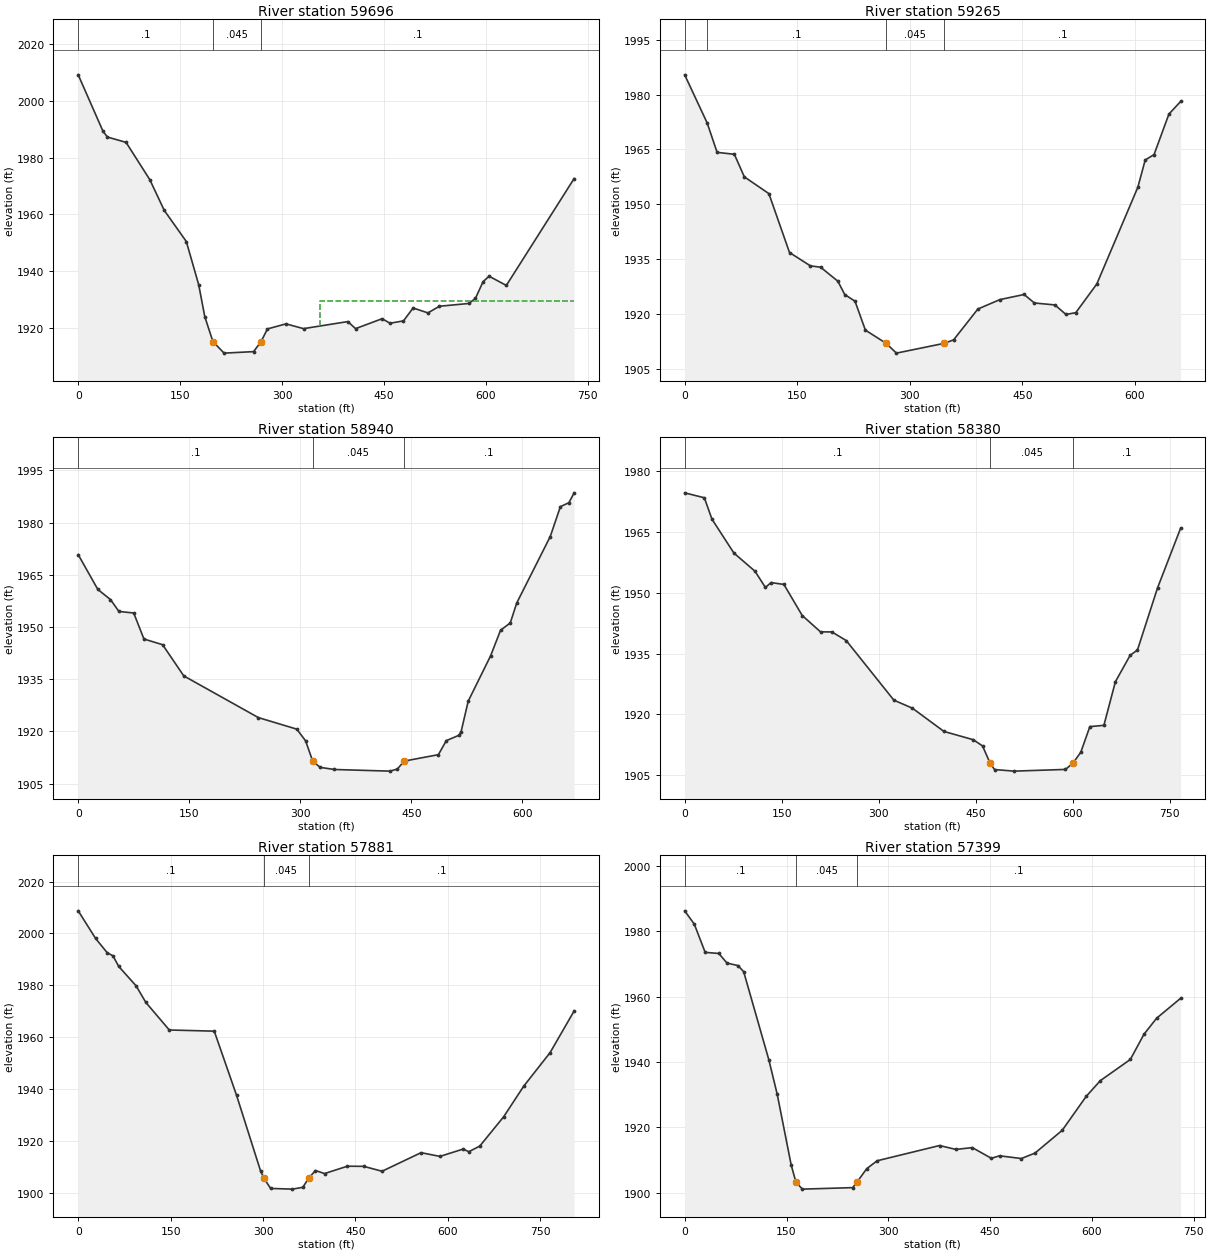
Type RM Length L Ch R = 1 ,59696   ,430.9,430.9,430.9
XS GIS Cut Line= 2
2234222.11274197677558.2301504842234741.17498457678071.332273241
#Sta/Elev= 30
       0 2009.18    36.6 1989.23    43.1 1987.25    70.4 1985.38   105.4 1972.22
   126.6 1961.42   159.1 1950.44   177.3 1935.22   186.3 1923.94  198.23 1915.18
   214.7  1911.1   258.1 1911.63  269.161915.182   278.5 1919.63   305.8 1921.41
   331.6 1919.73   396.8 1922.22   408.2 1919.73   447.2 1923.22   458.9 1921.64
   478.7 1922.46   492.9 1927.01   514.7 1925.28   531.6 1927.62   574.9  1928.6
   584.6 1930.38   595.9 1936.29   604.7  1938.2   630.1 1934.96   729.9 1972.64
#Mann= 3 ,-1,0
       0      .1       0  198.23    .045       0  269.16      .1       0
#XS Ineff= 2 , 0
                          356.36          1929.4
Permanent Ineff=
       F       F
Bank Sta=198.23,269.16
XS Rating Curve= 0 ,0
Exp/Cntr(USF)=0,0
Exp/Cntr=0.3,0.1

Type RM Length L Ch R = 1 ,59265   ,325.7,325.7,325.7
XS GIS Cut Line= 2
2233982.56466325677970.394831217 2234557.7613811678295.846916366
#Sta/Elev= 30
       0 1985.41      30 1972.24    43.2 1964.22    66.2 1963.69    79.5 1957.52
   112.2 1952.94   139.7 1936.84   167.6 1933.19   181.1 1932.83   204.1 1929.01
   213.3 1925.35     227 1923.53   240.8 1915.63   268.4 1912.03   282.2 1909.34
   346.2 1912.03   358.4 1912.97   390.7 1921.39     420 1923.97   452.3 1925.37
     466 1923.05   493.4 1922.51   508.1 1919.91   521.2  1920.4   549.2 1928.23
   603.9 1954.68   613.7 1962.13   625.5 1963.61   645.3 1974.68   660.9 1978.12
#Mann= 4 ,-1,0
       0     .08       0      30      .1       0   268.4    .045       0
   346.2      .1       0
Bank Sta=268.4,346.2
XS Rating Curve= 0 ,0
Exp/Cntr(USF)=0,0
Exp/Cntr=0.3,0.1

Type RM Length L Ch R = 1 ,58940   ,559.7,559.7,559.7
XS GIS Cut Line= 2
2233805.64431456678178.5609522172234337.81024197 678585.57271498
#Sta/Elev= 30
       0 1970.77    26.5 1960.78    43.6 1957.86      55 1954.46      75    1954
    88.8 1946.53     114  1944.9   142.6 1935.94   243.4 1923.96   295.3 1920.64
   307.2 1917.28  316.761911.458   326.9 1909.66   346.1 1909.05   421.2 1908.58
   431.2 1909.18  440.311911.458   486.6 1913.31   497.3 1917.34   514.4 1918.88
   517.3 1919.94   526.9 1928.69   557.1 1941.69   570.6 1949.06   583.7 1951.15
   592.4 1956.87   637.7 1975.97   651.4 1984.55   662.9  1985.7     670 1988.53
#Mann= 3 ,-1,0
       0      .1       0  316.76    .045       0  440.31      .1       0
Bank Sta=316.76,440.31
XS Rating Curve= 0 ,0
Exp/Cntr(USF)=0,0
Exp/Cntr=0.3,0.1

Type RM Length L Ch R = 1 ,58380   ,499.2,499.2,499.2
XS GIS Cut Line= 2
2233399.71722567678432.9231833962233916.06220568678999.510845228
#Sta/Elev= 30
       0 1974.68    30.4 1973.46    42.2 1968.17    76.1 1959.82   108.6 1955.35
   124.8 1951.34   133.6 1952.54   153.4 1952.07   181.7 1944.41     210 1940.37
   227.6 1940.36   249.7 1938.23   323.3 1923.53   352.1 1921.53   400.8  1915.8
   446.1 1913.76   460.4 1912.23   472.11907.972     479  1906.4   509.1 1906.01
   588.6 1906.43  600.151907.973   612.3 1910.67   626.3 1916.99     648 1917.31
   665.8 1928.08   688.6 1934.59   699.9  1935.9   730.9 1951.21   766.6 1965.95
#Mann= 3 ,-1,0
       0      .1       0   472.1    .045       0  600.15      .1       0
Bank Sta=472.1,600.15
XS Rating Curve= 0 ,0
Exp/Cntr(USF)=0,0
Exp/Cntr=0.3,0.1

Type RM Length L Ch R = 1 ,57881   ,481.4,481.4,481.4
XS GIS Cut Line= 2
2233052.13996906678895.7184228492233737.68703228679317.407488316
#Sta/Elev= 30
       0 2008.72    28.2 1998.09      47  1992.6    56.3 1991.42    65.8  1987.3
      94 1979.83   109.7 1973.48   147.8 1962.85   220.8  1962.4     257  1937.7
   295.9 1908.63  301.271905.864   312.2 1901.86   347.6 1901.59   364.5 1902.28
  374.231905.863   385.1 1908.76   399.8 1907.58   436.8 1910.41   463.4 1910.36
   493.1 1908.47   556.4 1915.62   587.1 1914.19   624.6    1917     634    1916
   651.7 1918.15   690.4 1929.42   723.2 1941.27   765.8 1954.12   804.9 1970.19
#Mann= 3 ,-1,0
       0      .1       0  301.27    .045       0  374.23      .1       0
Bank Sta=301.27,374.23
XS Rating Curve= 0 ,0
Exp/Cntr(USF)=0,0
Exp/Cntr=0.3,0.1

Type RM Length L Ch R = 1 ,57399   ,492.4,492.4,492.4
XS GIS Cut Line= 4
2232985.96674987679486.9888734682233052.82292052679489.989179313
2233358.29591494679565.9159929532233705.96910332679536.777763157
#Sta/Elev= 30
       0 1986.28    14.2 1982.19    30.2 1973.56    50.3 1973.22    62.3 1970.29
    78.6  1969.5    86.9 1967.64     124 1940.64   136.3 1930.11   156.9 1908.44
  163.841903.201   173.4 1901.04   247.6  1901.5  253.911903.203   268.2 1907.31
   283.6 1909.73   375.4 1914.39   399.6  1913.2   423.7 1913.76   451.8 1910.48
   463.9 1911.25     496 1910.41     516 1912.07   556.2 1919.06   591.5 1929.45
   612.4 1934.28   656.5 1940.75   676.6 1948.47   695.2 1953.38   730.6 1959.49
#Mann= 3 ,-1,0
       0      .1       0  163.84    .045       0  253.91      .1       0
Bank Sta=163.84,253.91
XS Rating Curve= 0 ,0
Exp/Cntr(USF)=0,0
Exp/Cntr=0.3,0.1

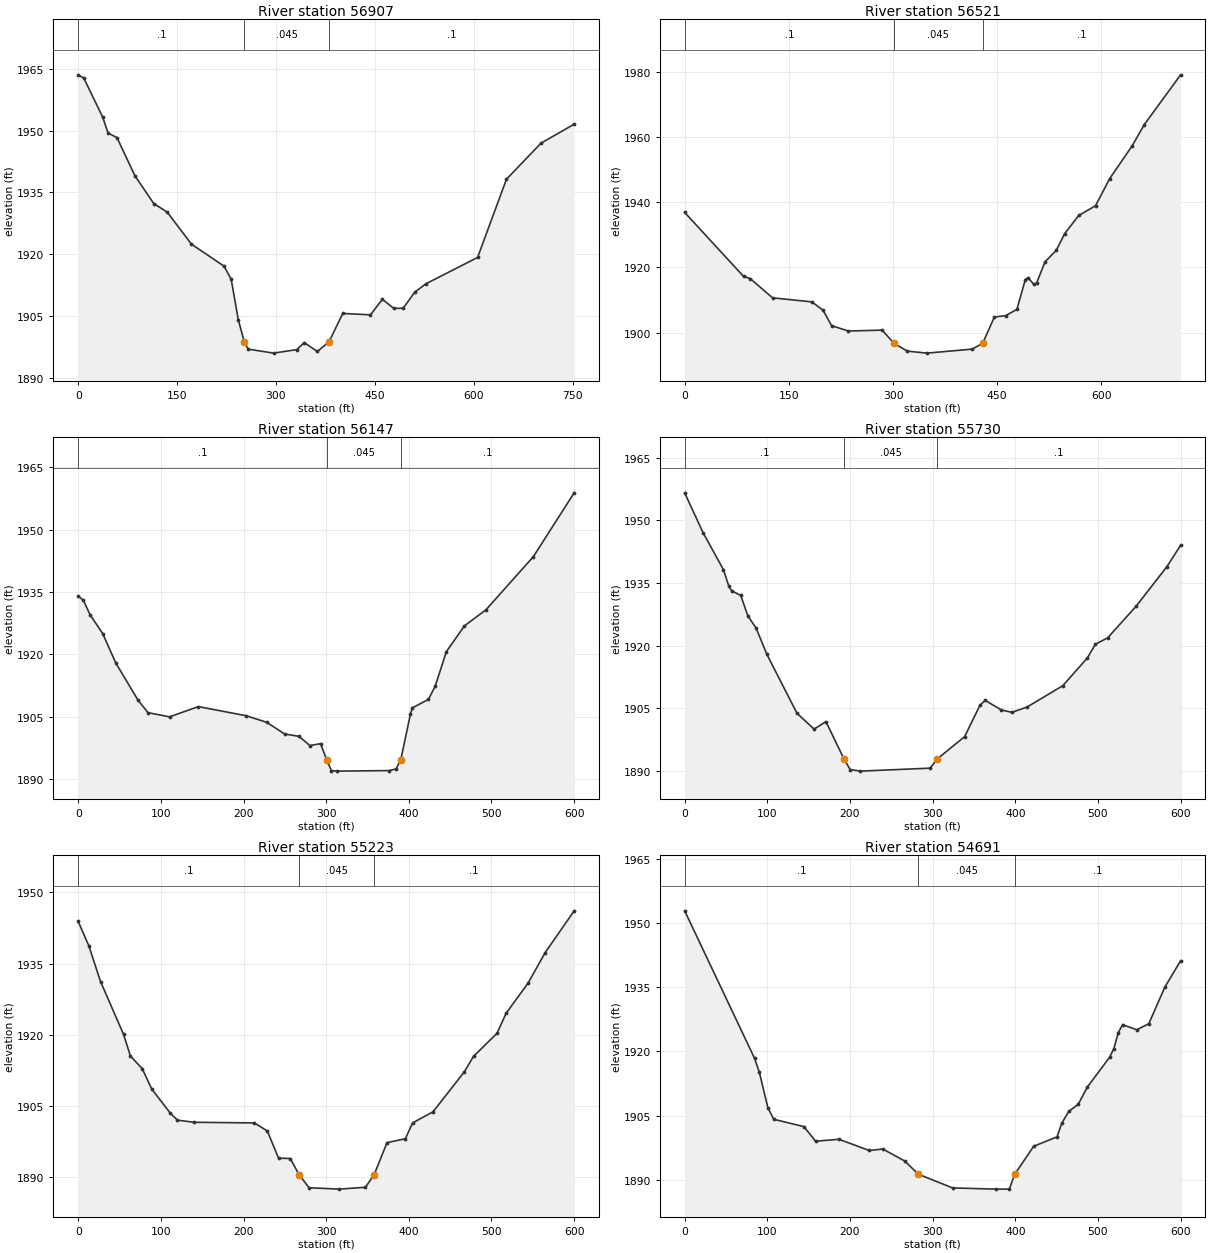
Type RM Length L Ch R = 1 ,56907   ,386.1,386.1,386.1
XS GIS Cut Line= 3
2233107.89570247680058.4125357712233305.32371937680017.945395091
2233716.83475052679651.798740701
#Sta/Elev= 30
       0 1963.49     8.5 1962.69      37 1953.27    45.3  1949.4    58.9 1948.26
      86 1939.03   114.6 1932.31     135 1930.23   171.8 1922.46   221.1 1917.15
   232.1 1913.95   242.8 1904.18  251.981898.763   257.9 1897.03   296.4 1896.06
   331.6 1896.91   342.9 1898.61   362.8 1896.46  380.471898.765   401.3 1905.67
   443.4 1905.34   461.4  1909.1   478.9 1906.89   493.1 1906.95   510.5 1910.83
   527.6 1912.87   605.9 1919.24   649.7 1938.19   702.1 1946.93   752.4 1951.53
#Mann= 3 ,-1,0
       0      .1       0  251.98    .045       0  380.47      .1       0
Bank Sta=251.98,380.47
XS Rating Curve= 0 ,0
Exp/Cntr(USF)=0,0
Exp/Cntr=0.3,0.1

Type RM Length L Ch R = 1 ,56521   ,373.5,373.5,373.5
XS GIS Cut Line= 2
2233271.02087511680292.3448974772233977.30089889680186.856725623
#Sta/Elev= 30
       0 1936.82    84.7 1917.24    94.2 1916.57   126.5 1910.65   183.2 1909.41
   199.3 1906.84   211.5 1902.12   235.7 1900.48   284.3 1900.75  301.551896.662
   320.7 1894.31   348.6  1893.7   413.7 1894.92  428.961896.662     446 1904.78
   462.2 1905.18   478.4 1907.12   490.5 1916.25   494.6 1916.82   502.7 1914.76
   506.7 1915.17   518.8 1921.66     535 1925.21   547.2 1930.33   567.4  1935.9
   591.6 1938.88   611.9 1947.17   644.2 1957.19   661.8 1963.75   714.1    1979
#Mann= 3 ,-1,0
       0      .1       0  301.55    .045       0  428.96      .1       0
Bank Sta=301.55,428.96
XS Rating Curve= 0 ,0
Exp/Cntr(USF)=0,0
Exp/Cntr=0.3,0.1

Type RM Length L Ch R = 1 ,56147   ,417.5,417.5,417.5
XS GIS Cut Line= 2
2233274.54012965680456.0110775092233826.31398773680691.692238264
#Sta/Elev= 30
       0 1933.93     6.1 1933.07    14.3 1929.53    29.6 1925.01    45.3    1918
    72.2 1909.06    84.4    1906   110.5    1905   145.4 1907.46   203.3 1905.26
     228 1903.69   249.7 1900.88   267.1 1900.32   280.2 1898.11   293.2 1898.55
  300.631894.669   306.3 1892.09     313 1891.96   375.8 1892.09   384.5 1892.47
  390.241894.674   401.9 1905.65   404.4 1907.17   423.7 1909.19   431.9 1912.37
   445.4 1920.65   467.2 1926.85   493.3 1930.71   550.7 1943.49     600 1958.81
#Mann= 3 ,-1,0
       0      .1       0  300.63    .045       0  390.24      .1       0
Bank Sta=300.63,390.24
XS Rating Curve= 0 ,0
Exp/Cntr(USF)=0,0
Exp/Cntr=0.3,0.1

Type RM Length L Ch R = 1 ,55730   ,506.4,506.4,506.4
XS GIS Cut Line= 2
2233094.23463012680716.3588453042233579.53049606681069.187305748
#Sta/Elev= 30
       0 1956.56    22.2 1947.04    46.9 1938.18    53.5 1934.17    56.8 1933.14
    67.8 1932.03    76.4 1927.15    86.5 1924.17    99.3 1917.99   135.9 1903.82
   156.6 1900.05   170.9 1901.84  192.641892.948   200.2 1890.38   212.3    1890
   296.9 1890.71  305.741892.945   338.7 1898.25   357.1  1905.7   363.4 1906.93
   383.2 1904.63   395.9 1904.06   414.3 1905.33   457.4 1910.43   487.1 1917.04
   496.9 1920.35   511.8 1921.89   546.4 1929.49   583.3 1938.88     600 1944.01
#Mann= 3 ,-1,0
       0      .1       0  192.64    .045       0  305.74      .1       0
Bank Sta=192.64,305.74
XS Rating Curve= 0 ,0
Exp/Cntr(USF)=0,0
Exp/Cntr=0.3,0.1

Type RM Length L Ch R = 1 ,55223   ,532.2,532.2,532.2
XS GIS Cut Line= 2
2232787.27959156681084.9952346782233251.26101406681465.417683511
#Sta/Elev= 30
       0 1943.88    12.9 1938.73      27 1931.23    54.8 1920.12    63.2 1915.54
    77.5 1912.87    88.9  1908.6   111.6 1903.47   120.1 1902.03     140 1901.59
   213.2 1901.45   228.8 1899.75   242.4 1894.03   256.6 1893.96  267.151890.559
   279.3  1887.8   315.7 1887.51   347.5  1887.9   358.1 1890.58   373.6  1897.3
   395.8 1898.12   404.6 1901.46   429.3  1903.8   466.9 1912.16   478.3 1915.48
   506.7 1920.33   517.6 1924.52   544.3 1930.91     565 1937.34     600 1946.12
#Mann= 3 ,-1,0
       0      .1       0  267.15    .045       0   358.1      .1       0
Bank Sta=267.15,358.1
XS Rating Curve= 0 ,0
Exp/Cntr(USF)=0,0
Exp/Cntr=0.3,0.1

Type RM Length L Ch R = 1 ,54691   ,553.7,553.7,553.7
XS GIS Cut Line= 2
2232410.46826022 681451.547019172232865.37343643681842.777489164
#Sta/Elev= 30
       0 1952.84    84.6 1918.38    90.3 1915.17   100.7 1906.84   107.8 1904.17
   144.2 1902.47   158.4 1899.06   186.7  1899.5   223.3 1896.89   239.7 1897.23
   266.2 1894.44  282.681891.354   324.1 1888.15   376.8 1887.87   392.7 1887.88
  399.411891.358   422.2 1897.87   450.5 1900.07   456.2 1903.24   464.7 1906.03
   476.1 1907.66   487.1 1911.68     514 1918.63   519.3 1920.69   524.6 1924.42
   529.8 1926.25     547 1925.07   561.5 1926.48     581 1935.06     600 1941.18
#Mann= 3 ,-1,0
       0      .1       0  282.68    .045       0  399.41      .1       0
Bank Sta=282.68,399.41
XS Rating Curve= 0 ,0
Exp/Cntr(USF)=0,0
Exp/Cntr=0.3,0.1

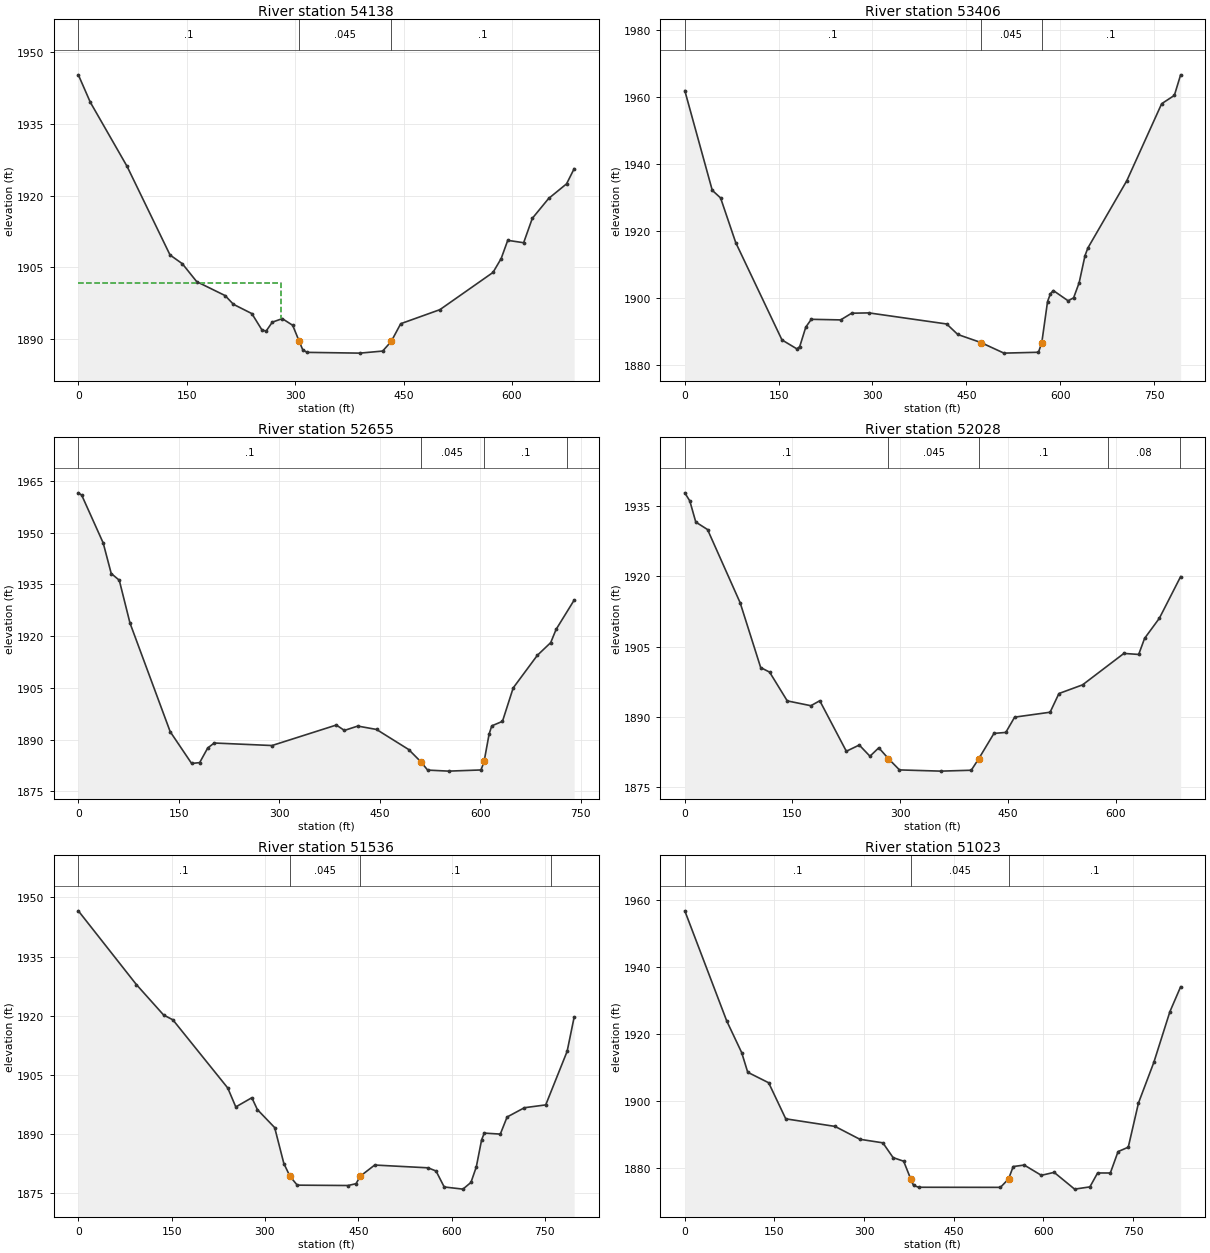
Type RM Length L Ch R = 1 ,54138   ,731.2,731.2,731.2
XS GIS Cut Line= 2
2232016.43785499681769.4114677372232501.05412835682255.028714403
#Sta/Elev= 30
       0  1945.2    16.6 1939.47    67.5 1926.08   126.9  1907.6   143.9 1905.78
   163.8 1902.04   203.1 1899.13   214.6 1897.31   240.1 1895.37   254.2 1891.93
   259.9 1891.73   268.4 1893.58   282.2 1894.32   296.6 1892.93  305.721889.551
   310.5 1887.83   316.4 1887.28   389.6 1887.12   421.1 1887.55  432.94 1889.55
   446.1 1893.26   500.3 1896.19   573.8 1903.96   585.1 1906.86   594.2 1910.66
   616.2 1910.16   628.2 1915.25   650.8  1919.4   675.6 1922.45   686.1 1925.61
#Mann= 3 ,-1,0
       0      .1       0  305.72    .045       0  432.94      .1       0
#XS Ineff= 2 , 0
          279.76 1901.72
Permanent Ineff=
       F       F
Bank Sta=305.72,432.94
XS Rating Curve= 0 ,0
Exp/Cntr(USF)=0,0
Exp/Cntr=0.3,0.1

Type RM Length L Ch R = 1 ,53406   ,751.7,751.7,751.7
XS GIS Cut Line= 2
2231555.79978446682121.6795394022231948.81436603682809.813245151
#Sta/Elev= 30
       0 1962.01    43.9 1932.18    57.2  1929.9    81.4 1916.54   155.3 1887.42
   179.1 1884.75   183.7 1885.43   193.4 1891.26   202.2 1893.59   249.1 1893.41
   266.7 1895.41   294.2 1895.51   418.6 1892.19   436.3 1889.05   473.21886.648
   510.1 1883.47   565.3 1883.73   570.6 1886.62   579.8 1898.91   584.4 1901.23
     589  1902.2   612.7 1899.12   621.5 1900.03   630.3 1904.53   639.7 1912.66
   644.3 1914.94   706.5 1935.06   762.2 1958.09   782.5 1960.58   792.5 1966.73
#Mann= 3 ,-1,0
       0      .1       0   473.2    .045       0   570.6      .1       0
Bank Sta=473.2,570.6
XS Rating Curve= 0 ,0
Exp/Cntr(USF)=0,0
Exp/Cntr=0.3,0.1

Type RM Length L Ch R = 1 ,52655   ,626.1,626.1,626.1
XS GIS Cut Line= 2
2231113.28921326682264.0475345882231117.73834006683004.146069181
#Sta/Elev= 30
       0 1961.56     5.1 1960.86    37.1 1947.03    49.1 1938.17    61.1 1936.23
    77.1 1923.81   137.1 1892.33   169.1 1883.11   181.1 1883.36   193.1 1887.59
   202.8 1889.04   289.1 1888.31   385.1 1894.25   397.1 1892.69   417.1 1893.95
   445.1 1892.97   493.1 1887.15  511.111883.632   521.4 1881.19   552.7 1880.89
   601.1 1881.23  605.681883.681   613.1 1891.58   617.1 1894.01   633.1 1895.32
   649.1 1905.01   685.1 1914.45   705.1 1918.14   713.1 1921.96   740.1 1930.46
#Mann= 4 ,-1,0
       0      .1       0  511.11    .045       0  605.68      .1       0
     730     .08       0
Bank Sta=511.11,605.68
XS Rating Curve= 0 ,0
Exp/Cntr(USF)=0,0
Exp/Cntr=0.3,0.1

Type RM Length L Ch R = 1 ,52028   ,492.2,492.2,492.2
XS GIS Cut Line= 2
 2230634.2356678682222.3453995362230473.61857503682894.057625379
#Sta/Elev= 30
       0 1937.82       7 1936.08    15.3 1931.58    31.7 1929.98    77.1 1914.36
   105.7 1900.53   118.1 1899.56   142.7 1893.42   175.6 1892.39     188 1893.45
     225 1882.67     243    1884   257.9 1881.61   270.2 1883.41  283.661881.088
     299 1878.69   356.6 1878.43     399 1878.62  409.441881.086   430.6 1886.48
   447.1 1886.69   459.4 1889.95   508.8    1891   521.1 1894.99     554 1896.84
   611.6 1903.55   632.2 1903.33   640.4 1906.76     661 1911.06   690.6 1919.94
#Mann= 5 ,-1,0
       0      .1       0  283.66    .045       0  409.44      .1       0
     590     .08       0     690      .1       0
Bank Sta=283.66,409.44
XS Rating Curve= 0 ,0
Exp/Cntr(USF)=0,0
Exp/Cntr=0.3,0.1

Type RM Length L Ch R = 1 ,51536   ,513.6,513.6,513.6
XS GIS Cut Line= 2
2230249.41877858681989.4863686512229959.04727191682731.726624696
#Sta/Elev= 30
       0 1946.61    93.3 1927.88   137.1 1920.14     152 1918.92   240.2  1901.6
   253.1 1896.79   278.9 1899.13   287.8 1896.12   315.6 1891.54   330.4  1882.4
   340.3 1879.14   351.9 1876.92   433.5 1876.83   446.4 1877.29  453.151879.194
   476.4 1882.03   562.3 1881.32     575 1880.51   588.1 1876.46   618.2 1875.91
   631.1 1877.61   639.7 1881.55   648.2  1888.4   652.5 1890.14   678.3 1889.89
   689.2 1894.23     717 1896.59   751.3 1897.31   785.7 1910.91     797 1919.62
#Mann= 4 ,-1,0
       0      .1       0   340.3    .045       0  453.15      .1       0
     760     .08       0
Bank Sta=340.3,453.15
XS Rating Curve= 0 ,0
Exp/Cntr(USF)=0,0
Exp/Cntr=0.3,0.1

Type RM Length L Ch R = 1 ,51023   ,555.3,555.3,555.3
XS GIS Cut Line= 3
2229842.00600493681765.0889116682229745.59217754681893.161118022
2229508.68034005682519.103179565
#Sta/Elev= 30
       0 1956.86    70.2 1923.87    95.2  1914.4   105.3 1908.52   140.3 1905.38
   168.9 1894.58   251.4 1892.31   292.9 1888.46   331.4 1887.39   348.5 1882.97
   366.2 1881.89   378.1 1876.53   382.7 1874.64   391.3 1874.09   528.1 1874.06
  541.63 1876.56   549.5 1880.29   567.9 1880.74   596.6 1877.66     618 1878.55
   652.2 1873.53   677.8  1874.2   690.7 1878.37     712 1878.36   724.9 1884.76
     742 1886.09   759.1 1899.34   784.8  1911.5   811.6 1926.64   829.6 1934.12
#Mann= 3 ,-1,0
       0      .1       0   378.1    .045       0  541.63      .1       0
Bank Sta=378.1,541.63
XS Rating Curve= 0 ,0
Exp/Cntr(USF)=0,0
Exp/Cntr=0.3,0.1

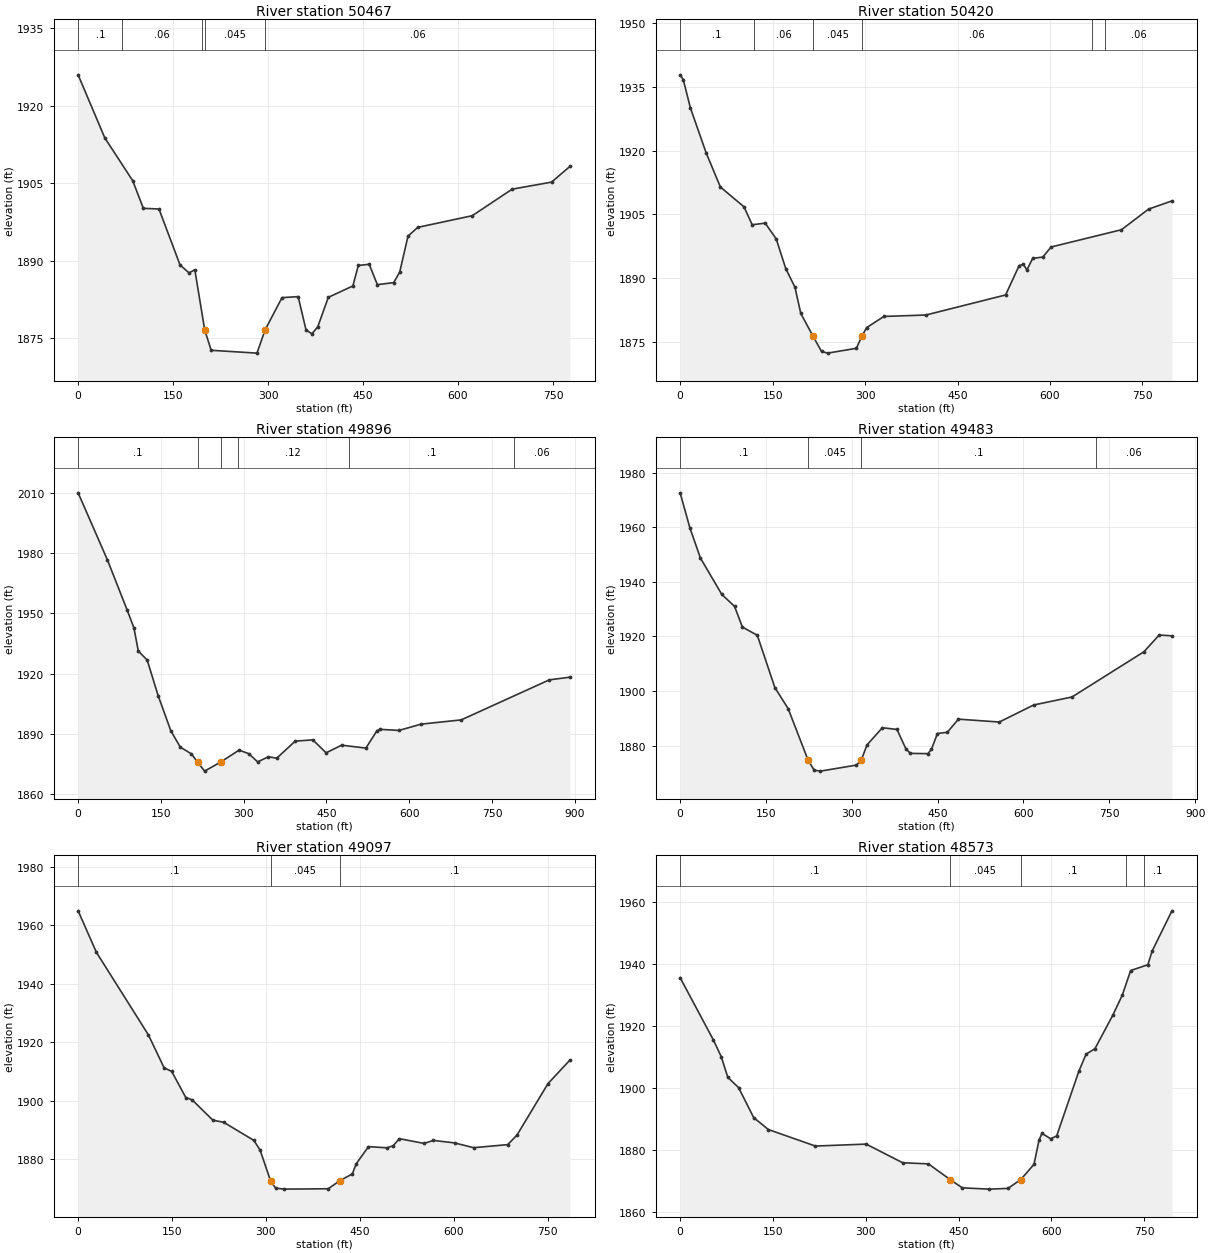
Type RM Length L Ch R = 1 ,50467   ,47.3,47.3,47.3
XS GIS Cut Line= 4
2228933.95703236 682059.025500692229076.56215578682160.723964817
2229205.71619273 682486.000080182229398.32546388682647.792709999
#Sta/Elev= 30
       0 1925.96      42 1913.78    86.2 1905.47     103 1900.12   127.7 1899.99
   160.9 1889.17   175.2 1887.62   184.3 1888.23   199.9 1876.59   210.1 1872.64
   282.5 1872.09   295.3 1876.59     322 1882.83   347.5 1883.03     360 1876.55
   369.3 1875.84   378.5 1877.19   395.1 1882.89   433.9 1885.09   442.5 1889.06
   459.7 1889.29   472.6 1885.34   498.4 1885.74   507.9 1887.78     521 1894.74
   536.3 1896.43   622.4 1898.69   685.5 1903.83   747.7 1905.19   776.7 1908.23
#Mann= 5 ,-1,0
       0      .1       0      70     .06       0  195.15      .1       0
   199.9    .045       0   295.3     .06       0
Bank Sta=199.9,295.3
XS Rating Curve= 0 ,0
Exp/Cntr(USF)=0,0
Exp/Cntr=0.3,0.1

Type RM Length L Ch R = 1 ,50420   ,524.1,524.1,524.1
XS GIS Cut Line= 4
2228889.20571361682073.0400840162229031.81083703682174.738548144
2229173.60773533682520.5593131932229374.11879481682668.128723998
#Sta/Elev= 30
       0 1937.81     5.1 1936.66    16.6 1930.04    42.4 1919.37    65.3 1911.41
   103.6 1906.75   116.9 1902.53     138 1902.91   155.9 1899.19   171.4 1892.18
   186.3 1887.83   195.7 1881.66   215.6 1876.31   229.4 1872.71   239.4 1872.32
   285.9 1873.46  295.07 1876.37   302.6 1878.33   330.6 1880.95   398.8 1881.29
     528 1886.01     550 1892.91   556.9 1893.23   562.6 1891.89     572 1894.62
   588.4 1894.93   601.8 1897.29     716 1901.36     760 1906.21   797.9 1908.14
#Mann= 6 ,-1,0
       0      .1       0     120     .06       0   215.6    .045       0
  295.07     .06       0  668.92      .1       0  688.92     .06       0
Bank Sta=215.6,295.07
XS Rating Curve= 0 ,0
Exp/Cntr(USF)=0,0
Exp/Cntr=0.3,0.1

Type RM Length L Ch R = 1 ,49896   ,413.3,413.3,413.3
XS GIS Cut Line= 2
2228599.16010338 682679.262134632229489.60603593 682716.96768049
#Sta/Elev= 30
       0 2010.23    53.1 1976.73    89.1 1951.53   101.1 1942.82   109.1 1931.18
   125.1 1926.78   145.1  1908.9     168 1891.41   185.2 1883.26   205.2 1879.91
   216.4 1875.81   229.2 1871.28  258.171875.788   291.7 1881.77   309.3 1879.99
   325.3 1875.89   344.7 1878.43     360 1877.76   393.4 1886.26   425.4 1886.88
   449.4 1880.41   477.4 1884.24   521.5 1882.78   541.5 1891.44   546.7 1892.14
   581.5 1891.61   621.6 1894.74   694.2 1896.86   853.8 1916.84   891.2 1918.19
#Mann= 6 ,-1,0
       0      .1       0   216.4    .045       0  258.17      .1       0
     290     .12       0     490      .1       0     790     .06       0
Bank Sta=216.4,258.17
XS Rating Curve= 0 ,0
Exp/Cntr(USF)=0,0
Exp/Cntr=0.3,0.1

Type RM Length L Ch R = 1 ,49483   ,385.4,385.4,385.4
XS GIS Cut Line= 3
2228813.15724026683216.1877963462229321.69031766682785.347272433
2229507.30990183682732.688903765
#Sta/Elev= 30
       0 1972.56      17 1959.75    35.4  1948.7    72.7 1935.39    95.1 1930.98
   108.8 1923.39   134.8 1920.42   165.5 1901.26   188.8 1893.52  223.771874.573
   234.2 1871.02   245.1 1870.66     308 1872.87  316.42 1874.57   326.4 1880.24
   353.4 1886.54   378.9 1885.93   394.5 1878.82   402.4 1877.16   432.8 1877.06
   439.1 1878.62   449.6 1884.43   466.9 1884.88   486.3 1889.69   557.7 1888.64
   617.7 1894.87   684.8 1897.81   810.5 1914.37   837.1  1920.5   859.4 1920.19
#Mann= 4 ,-1,0
       0      .1       0  223.77    .045       0  316.42      .1       0
  726.51     .06       0
Bank Sta=223.77,316.42
XS Rating Curve= 0 ,0
Exp/Cntr(USF)=0,0
Exp/Cntr=0.3,0.1

Type RM Length L Ch R = 1 ,49097   ,524.2,524.2,524.2
XS GIS Cut Line= 2
2229114.52079033683560.3398163232229576.66564916682924.753786791
#Sta/Elev= 30
       0 1964.93    29.2 1950.76   112.3 1922.55   137.4 1911.31   149.5 1910.08
   172.1 1901.14     182 1900.41   215.3 1893.42   232.5 1892.72   280.9 1886.51
   290.8 1883.19  307.441872.729   315.5 1870.23   329.3 1869.88   399.6 1870.01
  417.931872.727   438.1 1875.08   444.4 1878.54   463.9 1884.39   493.5 1883.99
   503.4 1884.71   513.3 1887.11   552.9 1885.49   567.6 1886.52   601.4 1885.67
     632 1884.03   686.4 1885.08   701.2 1888.33   750.8 1905.93   785.8 1913.96
#Mann= 3 ,-1,0
       0      .1       0  307.44    .045       0  417.93      .1       0
Bank Sta=307.44,417.93
XS Rating Curve= 0 ,0
Exp/Cntr(USF)=0,0
Exp/Cntr=0.3,0.1

Type RM Length L Ch R = 1 ,48573   ,605.9,605.9,605.9
XS GIS Cut Line= 2
 2229344.2935005683767.8440107042230012.87747543683337.737714092
#Sta/Elev= 30
       0 1935.56    53.9 1915.38    66.4 1910.05    77.1 1903.37    94.5 1900.06
   118.8 1890.41   142.5 1886.53   218.6 1881.19   300.7 1881.82   359.8 1875.79
   401.3 1875.44  436.31 1870.38   456.2 1867.69   499.7 1867.28   529.9 1867.51
  550.651870.378     572 1875.28   580.1 1883.06   584.9 1885.29   599.1 1883.53
   608.7 1884.48   644.4 1905.27   656.2 1910.87   670.5 1912.62   699.4 1923.44
   714.7  1929.9   728.3 1937.87   756.1 1939.74     763 1944.15     795 1957.15
#Mann= 5 ,-1,0
       0      .1       0  436.31    .045       0  550.65      .1       0
     720     .06       0     750      .1       0
Bank Sta=436.31,550.65
XS Rating Curve= 0 ,0
Exp/Cntr(USF)=0,0
Exp/Cntr=0.3,0.1

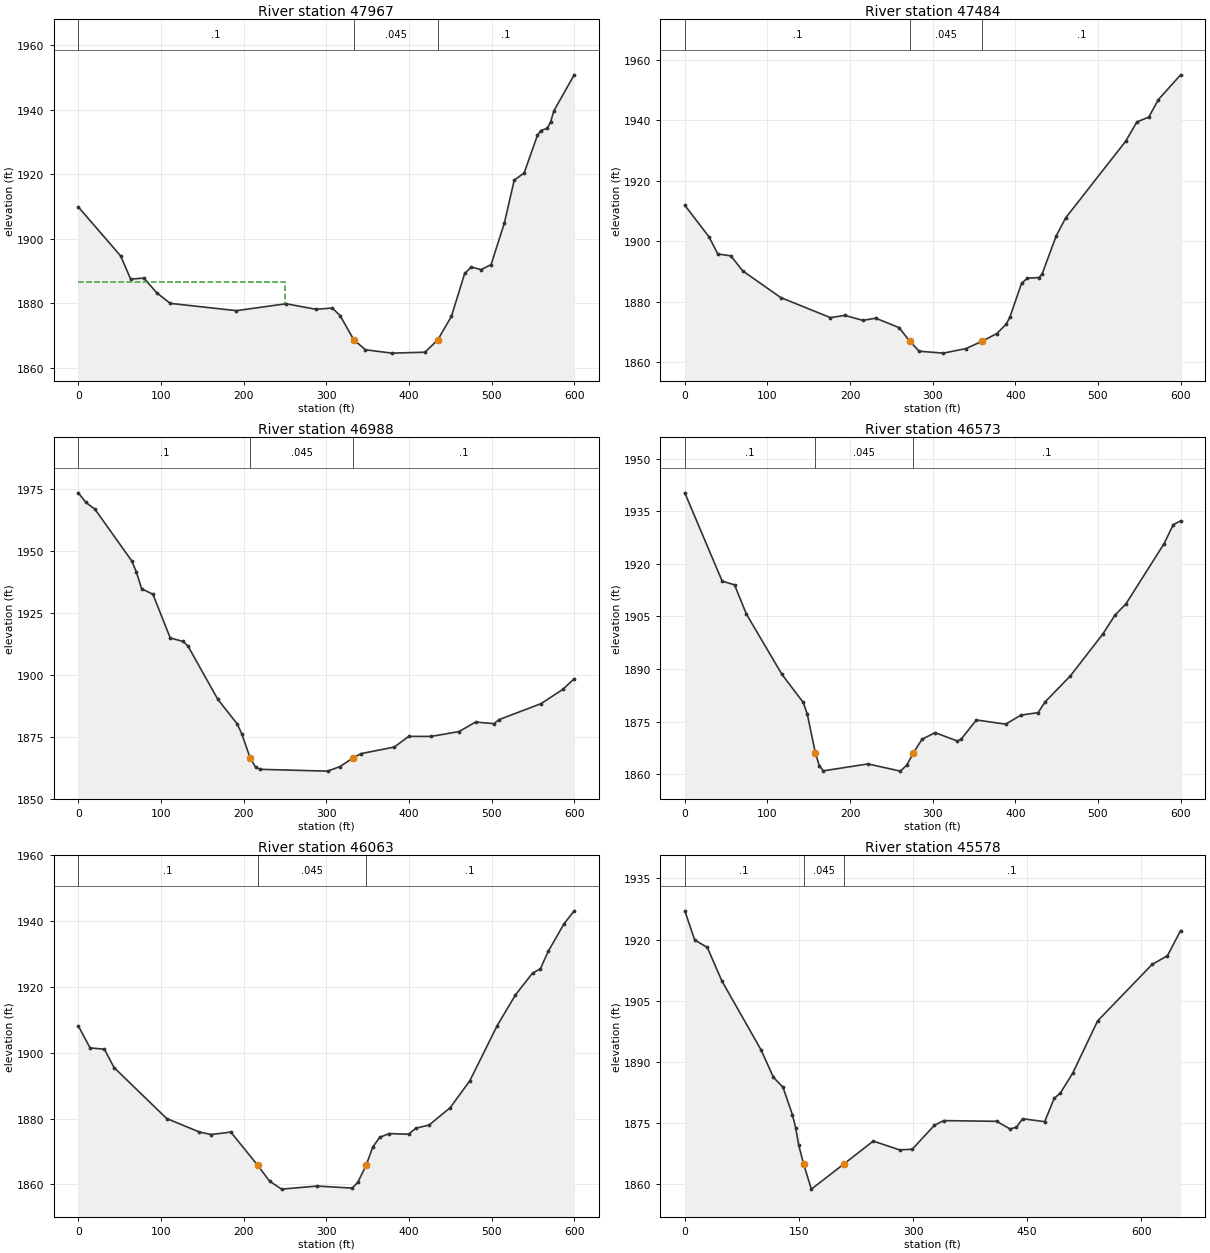
Type RM Length L Ch R = 1 ,47967   ,483.6,483.6,483.6
XS GIS Cut Line= 2
2229496.96022196684019.7304303972230096.61600319684040.051454832
#Sta/Elev= 30
       0 1909.85    51.2 1894.67    63.3 1887.47    79.3 1887.78    95.3 1883.11
   111.3 1879.94   191.3 1877.68   251.4 1879.82   287.4 1878.11   307.4 1878.49
   316.7 1876.17  333.331868.645   347.4 1865.54   379.4  1864.5   419.5 1864.79
  435.011868.643   451.5 1875.93   467.5 1889.22   475.5 1891.22   487.5 1890.41
   499.5 1891.99   515.5 1904.84   527.5 1918.18   539.5 1920.41   555.5 1932.05
   559.5 1933.56   567.5 1934.26   571.5 1936.27   575.5 1939.69     600 1950.86
#Mann= 3 ,-1,0
       0      .1       0  333.33    .045       0  435.01      .1       0
#XS Ineff= 2 , 0
          250.31 1886.51
Permanent Ineff=
       F       F
Bank Sta=333.33,435.01
XS Rating Curve= 0 ,0
Exp/Cntr(USF)=0,0
Exp/Cntr=0.3,0.1

Type RM Length L Ch R = 1 ,47484   ,495.4,495.4,495.4
XS GIS Cut Line= 2
2229431.31588691684252.4976893422229923.88509187684595.098883627
#Sta/Elev= 30
       0 1911.89    29.2 1901.47      40 1895.75    55.7 1895.15    70.1 1890.16
   116.1 1881.34   176.3 1874.69   193.6 1875.44   215.4 1873.79     231 1874.51
   259.3  1871.4  272.231866.878   283.6 1863.58   312.9 1862.95   340.2 1864.45
  359.711866.878   377.6 1869.44   389.1 1872.58   393.5 1874.93   407.5 1886.05
   414.5 1887.73   428.5 1887.96   432.2 1889.01   449.5 1901.79   460.9 1907.72
   533.6 1933.11   547.1 1939.47   561.5 1941.06     573 1946.83     600 1955.05
#Mann= 3 ,-1,0
       0      .1       0  272.23    .045       0  359.71      .1       0
Bank Sta=272.23,359.71
XS Rating Curve= 0 ,0
Exp/Cntr(USF)=0,0
Exp/Cntr=0.3,0.1

Type RM Length L Ch R = 1 ,46988   ,414.7,414.7,414.7
XS GIS Cut Line= 2
2229077.67825458684476.0613978692229510.08245632684892.026067423
#Sta/Elev= 30
       0  1973.4       9 1969.57    20.1  1966.8    64.8 1945.85    70.1  1941.6
    76.6  1934.7    90.3 1932.47   111.2 1914.87     127 1913.43   132.7 1911.57
   168.9 1890.05   192.2 1880.21   197.8 1876.19  207.981866.376   214.4 1862.81
   219.9 1861.87   301.6 1861.14   316.6 1862.97  332.091866.378     342 1868.19
   382.4 1870.86   399.7 1875.15   426.9 1875.14   460.8 1877.11   480.7 1880.94
     503 1880.29   508.9 1881.89   559.9 1888.36   586.3 1894.13     600  1898.4
#Mann= 3 ,-1,0
       0      .1       0  207.98    .045       0  332.09      .1       0
Bank Sta=207.98,332.09
XS Rating Curve= 0 ,0
Exp/Cntr(USF)=0,0
Exp/Cntr=0.3,0.1

Type RM Length L Ch R = 1 ,46573   ,510.4,510.4,510.4
XS GIS Cut Line= 2
2228839.23968153684862.2189102682229329.00784081685208.812548627
#Sta/Elev= 30
       0 1940.22    45.2 1915.04    60.2 1913.97    74.6 1905.61   117.6 1888.43
   143.3 1880.45   148.2 1877.14  158.021866.013   162.9 1862.28   167.8 1860.94
   221.7  1862.9   260.9 1860.85   268.3 1862.49  276.711866.014   286.9 1869.91
   302.9 1871.82   329.9 1869.44   334.4 1869.97   352.9 1875.43   388.3 1874.25
   406.7 1876.82   427.5 1877.53   436.1 1880.62   466.7 1888.04   505.9 1899.97
   520.6 1905.36   533.7 1908.51   579.9  1925.7   591.1 1931.15     600 1932.22
#Mann= 3 ,-1,0
       0      .1       0  158.02    .045       0  276.71      .1       0
Bank Sta=158.02,276.71
XS Rating Curve= 0 ,0
Exp/Cntr(USF)=0,0
Exp/Cntr=0.3,0.1

Type RM Length L Ch R = 1 ,46063   ,485.1,485.1,485.1
XS GIS Cut Line= 2
2228528.48195682 685269.24117084 2229034.6841574685591.358124956
#Sta/Elev= 30
       0 1908.18    14.2 1901.48    31.6 1901.09    43.2 1895.52   106.9 1880.03
   146.6 1875.91   160.8 1875.17   184.5  1875.9  216.881865.866   231.5 1860.97
     246 1858.57   288.8  1859.5   331.5 1858.88   338.2 1860.64  348.411865.871
   356.1 1871.27   364.7 1874.33   376.4 1875.45   399.6 1875.25   408.3 1877.07
   424.6 1878.07     450 1883.32   473.8 1891.52   506.9 1908.27   528.9 1917.56
   549.6 1924.21   559.1 1925.52   568.6  1930.8   587.5 1939.12     600 1943.14
#Mann= 3 ,-1,0
       0      .1       0  216.88    .045       0  348.41      .1       0
Bank Sta=216.88,348.41
XS Rating Curve= 0 ,0
Exp/Cntr(USF)=0,0
Exp/Cntr=0.3,0.1

Type RM Length L Ch R = 1 ,45578   ,565.1,565.1,565.1
XS GIS Cut Line= 3
2228291.60534669  685733.83395482228774.31096351685864.797574496
2228925.48867017685853.567382492
#Sta/Elev= 30
       0 1927.05      13  1919.9    29.6 1918.07    48.8 1909.82   100.1 1892.97
   116.6 1886.17   129.1 1883.76   141.5 1876.99   145.7 1873.87   149.8 1869.51
  156.251864.858   166.4 1858.75  208.711864.858   247.7 1870.54   282.4 1868.38
     299 1868.54     328  1874.4   340.4 1875.57     410 1875.39   427.5 1873.53
   435.8 1873.94   444.1 1876.02   473.1 1875.31   485.5    1881   493.8 1882.36
     510 1887.23   542.6 1900.02   614.3 1913.89   634.4 1916.02   651.8 1922.21
#Mann= 3 ,-1,0
       0      .1       0  156.25    .045       0  208.71      .1       0
Bank Sta=156.25,208.71
XS Rating Curve= 0 ,0
Exp/Cntr(USF)=0,0
Exp/Cntr=0.3,0.1

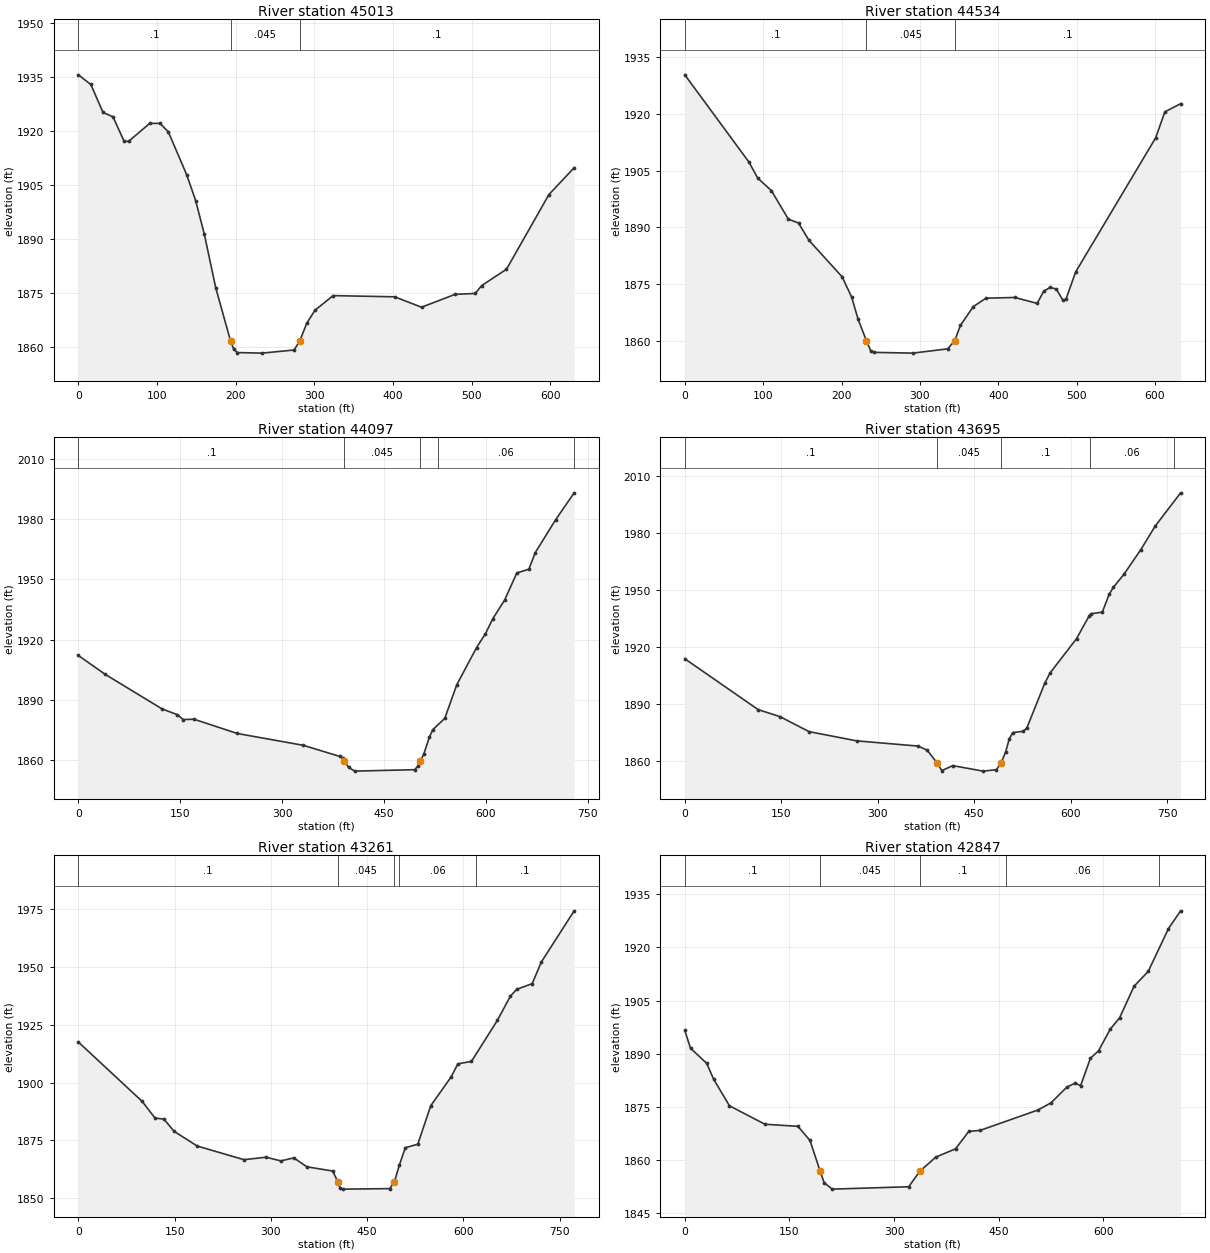
Type RM Length L Ch R = 1 ,45013   ,478.9,478.9,478.9
XS GIS Cut Line= 2
2228530.51271135686429.4288578132228930.77655177685942.665594429
#Sta/Elev= 30
       0 1935.56    15.9 1932.88    31.4  1925.1      44 1923.91    58.2 1917.09
    63.9 1917.09    90.8 1922.09   103.9 1922.06   114.3 1919.75   137.8 1907.78
   149.1 1900.64   160.1 1891.34   174.7 1876.37  193.47 1861.64   197.4 1859.37
   202.3 1858.43   233.4 1858.27   274.2 1859.14  281.421861.638   290.3 1866.55
   300.7 1870.16   323.8 1874.24   402.1 1873.91   436.2 1871.02   478.8 1874.59
   504.4 1874.84   512.7 1877.04   544.2 1881.57   598.1  1902.3   630.2 1909.77
#Mann= 3 ,-1,0
       0      .1       0  193.47    .045       0  281.42      .1       0
Bank Sta=193.47,281.42
XS Rating Curve= 0 ,0
Exp/Cntr(USF)=0,0
Exp/Cntr=0.3,0.1

Type RM Length L Ch R = 1 ,44534   ,436.8,436.8,436.8
XS GIS Cut Line= 3
 2229027.6246349  686635.3877168 2229099.2070963686461.617644506
2229188.63236391686025.927098761
#Sta/Elev= 30
       0 1930.38    81.8 1907.28    93.2 1902.98   110.5 1899.71   132.2 1892.14
   145.1 1891.13   158.4 1886.55   200.6 1876.91   212.9 1871.52   221.1 1865.65
  231.671859.991   237.4 1857.22   241.5 1856.86   290.8 1856.66   335.4 1857.79
  344.481859.993   351.7    1864   368.1 1868.98   384.4 1871.22   421.1  1871.4
   449.7 1869.83   457.9 1873.04   466.1 1874.06   474.2 1873.64   482.4 1870.66
   486.5    1871   498.7 1878.15   600.8 1913.68   612.6 1920.57   632.7 1922.73
#Mann= 3 ,-1,0
       0      .1       0  231.67    .045       0  344.48      .1       0
Bank Sta=231.67,344.48
XS Rating Curve= 0 ,0
Exp/Cntr(USF)=0,0
Exp/Cntr=0.3,0.1

Type RM Length L Ch R = 1 ,44097   ,402.5,402.5,402.5
XS GIS Cut Line= 2
2229363.20742236686804.8077539872229676.16855884 686144.91221422
#Sta/Elev= 30
       0  1912.1    39.6 1902.72   123.5  1885.5   145.7 1882.69   154.5 1880.24
   170.3 1880.41   234.2 1873.31   331.6 1867.41   384.8 1861.93   389.2 1861.06
  391.771859.468     398 1856.51   406.9 1854.59   495.4 1855.31   499.8    1857
  503.431859.469   508.7 1862.95   516.9 1871.32     522 1875.18   539.7 1880.81
   557.4 1897.54   586.6 1916.06   599.7 1922.97   610.5 1930.41   627.7 1939.55
   645.9 1953.17   663.6 1955.01   673.1  1963.3   703.1 1979.67   730.3    1993
#Mann= 5 ,-1,0
       0      .1       0  391.77    .045       0  503.43      .1       0
     530     .06       0     730      .1       0
Bank Sta=391.77,503.43
XS Rating Curve= 0 ,0
Exp/Cntr(USF)=0,0
Exp/Cntr=0.3,0.1

Type RM Length L Ch R = 1 ,43695   ,433.1,433.1,433.1
XS GIS Cut Line= 2
2229555.61295986686977.7961951472230088.39433939686420.449441653
#Sta/Elev= 30
       0 1913.69     114 1886.89   147.9 1883.18   193.2 1875.27   267.1 1870.41
     363 1867.64   377.1 1865.41   392.31858.732   399.7 1854.72   416.7 1857.34
   463.9 1854.44   484.6 1855.21   491.81858.732   498.8 1864.43   504.4 1871.23
   509.9 1874.79   526.5 1875.43   532.1 1877.36   559.7 1900.78   568.1 1906.24
   609.1 1924.29   628.9 1936.38   631.8 1937.45   649.2 1938.25     660 1947.78
   666.5 1951.39   682.7 1958.16   709.2 1971.27   731.3 1983.56     771 2001.18
#Mann= 5 ,-1,0
       0      .1       0   392.3    .045       0   491.8      .1       0
     630     .06       0     760      .1       0
Bank Sta=392.3,491.8
XS Rating Curve= 0 ,0
Exp/Cntr(USF)=0,0
Exp/Cntr=0.3,0.1

Type RM Length L Ch R = 1 ,43261   ,414.3,414.3,414.3
XS GIS Cut Line= 2
2229753.65000275687192.5805180182230394.45617011 686761.35466318
#Sta/Elev= 30
       0 1917.57    99.5 1891.84   119.5  1884.6   133.2  1884.2   149.4 1878.83
   185.2 1872.51   257.9  1866.6   292.5 1867.66   315.5 1866.07   335.7 1867.38
   355.9 1863.52   396.2 1861.68  404.191857.055     408 1854.26   412.9 1853.84
   485.2 1854.06  492.391857.061     500 1864.16   509.3 1871.76   528.8 1873.33
     549 1889.97   580.7 1902.43   591.3 1908.11   612.4 1909.17   652.7 1926.91
   673.2  1937.5   682.9 1940.39     707 1942.85   721.4 1952.29   772.4  1974.4
#Mann= 5 ,-1,0
       0      .1       0  404.19    .045       0  492.39      .1       0
     500     .06       0     620      .1       0
Bank Sta=404.19,492.39
XS Rating Curve= 0 ,0
Exp/Cntr(USF)=0,0
Exp/Cntr=0.3,0.1

Type RM Length L Ch R = 1 ,42847   ,487.7,487.7,487.7
XS GIS Cut Line= 2
2229990.78880794687459.0636609622230593.87832052687082.871795995
#Sta/Elev= 30
       0 1896.56     8.2 1891.57    31.4 1887.29    41.4 1882.81      64 1875.32
   114.8 1870.12   162.1 1869.53   179.5 1865.54  194.15 1856.81   199.8 1853.61
   211.4 1851.81     321 1852.48  336.711856.813   359.9 1860.85   388.2 1863.19
   407.1  1868.1   423.4 1868.38   506.1 1874.12   525.1 1876.17   547.7 1880.59
   559.8 1881.73   567.4 1880.98   581.5 1888.73   593.1 1890.82   609.8 1896.92
   623.3 1900.12     644 1909.04   664.3 1913.21   693.4 1925.32   710.8 1930.32
#Mann= 5 ,-1,0
       0      .1       0  194.15    .045       0  336.71      .1       0
     460     .06       0     680      .1       0
Bank Sta=194.15,336.71
XS Rating Curve= 0 ,0
Exp/Cntr(USF)=0,0
Exp/Cntr=0.3,0.1