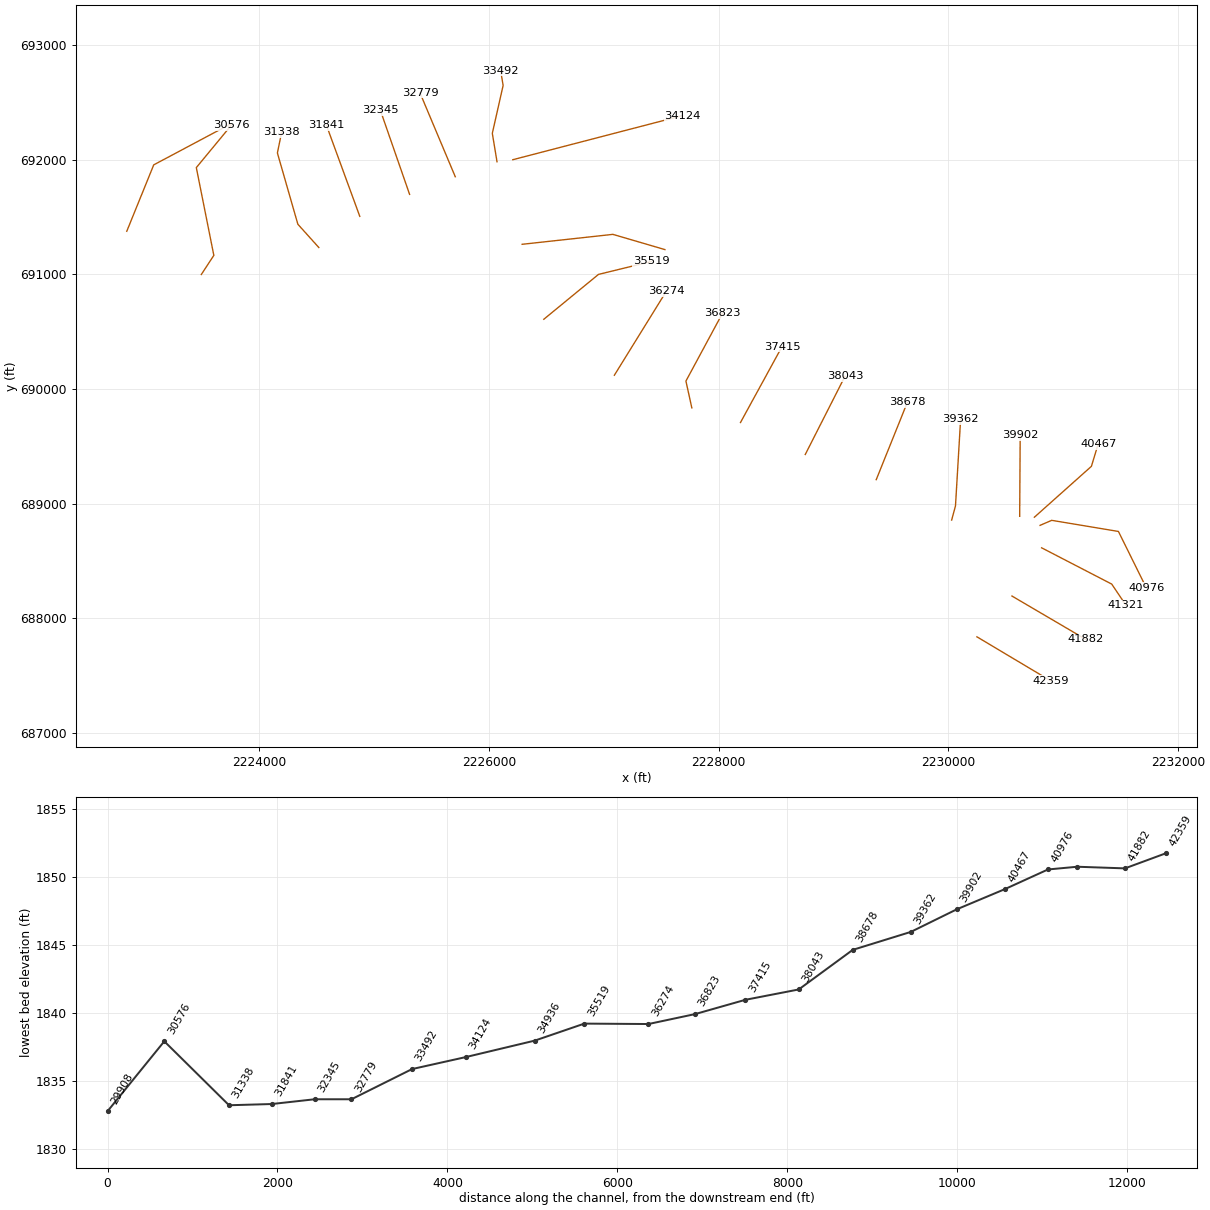
HEC-RAS study MIDFKRIV.prj: MIDFKRIV

--- MIDFKRIV.g01 (geometry) --- (continued)

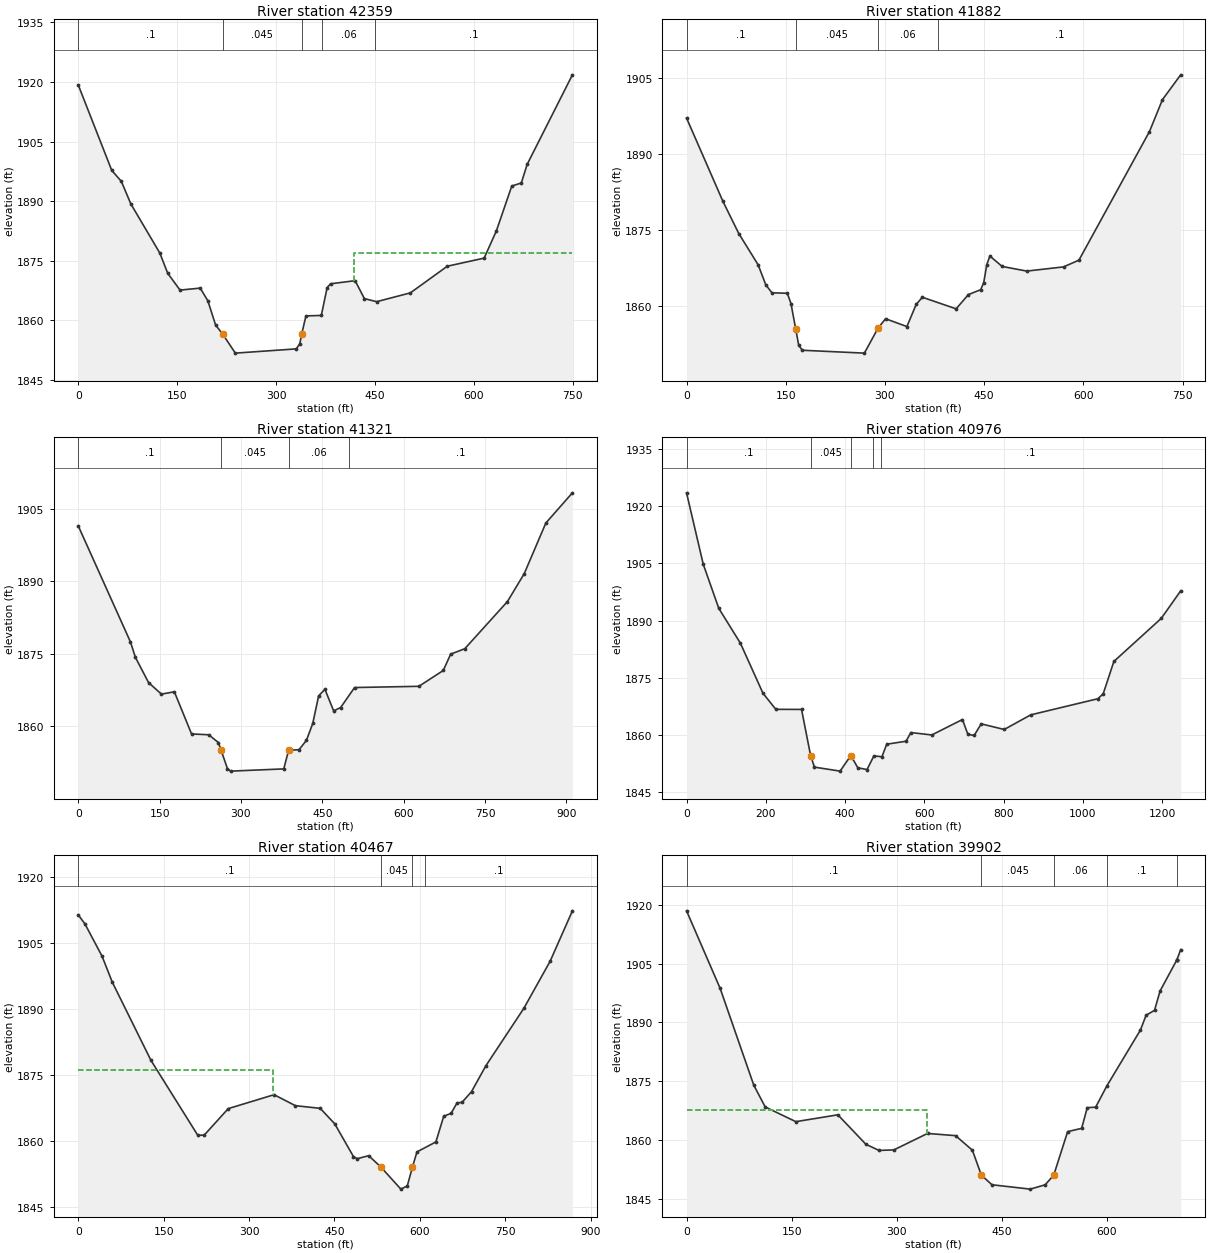
Type RM Length L Ch R = 1 ,42359   ,477.7,477.7,477.7
XS GIS Cut Line= 2
2230247.64253696687838.2841952432230891.13759356 687453.82714321
#Sta/Elev= 30
       0 1919.25    50.8 1897.74    65.4 1894.97    79.8 1889.29   123.7 1876.94
   135.7 1871.84   154.4  1867.6     185  1868.1   196.6  1864.9   208.3 1858.82
  219.341856.458   238.3 1851.73   330.8  1852.8   336.1 1854.13  338.851856.461
   345.4  1861.1   368.7 1861.22   377.5  1868.2   382.7 1869.19     420 1869.97
     434 1865.46   452.6 1864.68   503.8  1866.9   559.8 1873.61   615.7 1875.65
   634.2 1882.48   657.6 1893.79   672.1 1894.58   680.9 1899.23   749.6  1921.8
#Mann= 5 ,-1,0
       0      .1       0  219.34    .045       0  338.85      .1       0
     370     .06       0     450      .1       0
#XS Ineff= 2 , 0
                          418.32         1876.83
Permanent Ineff=
       F       F
Bank Sta=219.34,338.85
XS Rating Curve= 0 ,0
Exp/Cntr(USF)=0,0
Exp/Cntr=0.3,0.1

Type RM Length L Ch R = 1 ,41882   ,560.4,560.4,560.4
XS GIS Cut Line= 2
2230552.75492329  688193.85172532231196.88337735687815.206101039
#Sta/Elev= 30
       0 1897.17      55 1880.68      79  1874.3   108.2 1868.13   119.9 1864.13
   129.2 1862.57   152.4 1862.48   157.9 1860.45  164.961855.485   169.6 1852.19
     175  1851.2   268.9 1850.63   289.4 1855.54   300.9 1857.44   333.2 1855.89
   347.3 1860.29   356.6 1861.69   407.6  1859.4   426.2 1862.22   444.8 1863.19
   449.4 1864.61     454 1868.16   458.7 1869.85   477.2 1867.79   514.4 1866.87
     570  1867.7   593.3 1869.03     700  1894.5   719.6 1900.81   747.2 1905.72
#Mann= 4 ,-1,0
       0      .1       0  164.96    .045       0   289.4     .06       0
     380      .1       0
Bank Sta=164.96,289.4
XS Rating Curve= 0 ,0
Exp/Cntr(USF)=0,0
Exp/Cntr=0.3,0.1

Type RM Length L Ch R = 1 ,41321   ,345.1,345.1,345.1
XS GIS Cut Line= 3
2230810.68815931688614.5421354672231421.15500181688297.987090689
2231545.66969906 688112.49826018
#Sta/Elev= 30
       0 1901.41    96.3 1877.43   105.3 1874.27   129.7 1869.03   153.4 1866.66
   177.2 1867.14   208.9 1858.43   240.5 1858.26   258.5 1856.65     263 1855.19
   275.1 1851.26     281 1850.75   378.9 1851.21   387.8 1855.03   407.2 1855.19
   420.7 1857.11   432.4 1860.61   443.2  1866.3   454.8 1867.65   470.9  1863.2
   483.8 1863.89   509.5 1868.02     628 1868.27     673 1871.54   686.6 1874.91
   712.7 1876.04   791.3 1885.78   822.3 1891.55   862.1    1902   911.1 1908.24
#Mann= 4 ,-1,0
       0      .1       0     263    .045       0   387.8     .06       0
     500      .1       0
Bank Sta=263,387.8
XS Rating Curve= 0 ,0
Exp/Cntr(USF)=0,0
Exp/Cntr=0.3,0.1

Type RM Length L Ch R = 1 ,40976   ,509.2,509.2,509.2
XS GIS Cut Line= 4
2230797.52354856 688810.379547372230898.69219891688853.998950784
2231479.42441693688757.0794522362231721.85487744688266.047638234
#Sta/Elev= 30
       0 1923.45    42.1 1904.76    81.3  1893.2     136 1884.04   192.8 1870.95
   225.2 1866.74   290.1 1866.71  312.971854.634   322.6  1851.6   387.4 1850.55
   414.5 1854.64     432 1851.43   455.3 1850.96   472.6 1854.54   492.9 1854.32
     505  1857.6   553.7 1858.38   565.9 1860.66   618.6 1860.02     696 1864.07
   709.7 1860.19   725.6  1859.9   743.4 1862.93   801.4 1861.46   868.3 1865.29
  1037.9 1869.52  1051.2 1870.84    1078 1879.28  1197.6 1890.57  1246.6 1897.78
#Mann= 5 ,-1,0
       0      .1       0  312.97    .045       0   414.5      .1       0
  470.17     .06       0  490.17      .1       0
Bank Sta=312.97,414.5
XS Rating Curve= 0 ,0
Exp/Cntr(USF)=0,0
Exp/Cntr=0.3,0.1

Type RM Length L Ch R = 1 ,40467   ,564.5,564.5,564.5
XS GIS Cut Line= 3
2230747.69380914688881.3341227282231243.99243665689324.862911344
2231302.86732696689518.668103685
#Sta/Elev= 30
       0 1911.34    11.8 1909.28    41.8 1901.97    59.7  1896.1   127.7 1878.33
   209.9 1861.34   221.2 1861.34   263.5 1867.37     344 1870.53   381.5 1868.04
   425.2 1867.43   450.7 1863.91   483.5 1856.49   490.3 1856.01   510.3 1856.69
  531.791854.097   566.8  1849.1   578.1 1849.83  587.111854.098   595.1 1857.55
   628.3 1859.81   642.1 1865.64   655.1 1866.31   665.6 1868.68   674.3 1868.79
     691 1871.24   716.1 1877.09     783 1890.16     829 1900.81   868.2 1912.26
#Mann= 4 ,-1,0
       0      .1       0  531.79    .045       0  587.11     .06       0
     610      .1       0
#XS Ineff= 2 , 0
             342 1876.18
Permanent Ineff=
       F       F
Bank Sta=531.79,587.11
XS Rating Curve= 0 ,0
Exp/Cntr(USF)=0,0
Exp/Cntr=0.3,0.1

Type RM Length L Ch R = 1 ,39902   ,540.9,540.9,540.9
XS GIS Cut Line= 2
2230619.79811748 688889.196860962230624.17518203689594.618024492
#Sta/Elev= 30
       0  1918.4      48 1898.66      96 1874.05   112.3 1868.52     156 1864.78
     216 1866.52     256 1859.03   274.7 1857.46     296  1857.6     344 1861.78
     384 1861.22     408 1857.53  420.811851.188     436 1848.73   490.7 1847.62
     512 1848.73  524.171851.186     544 1862.24     564 1863.08     572 1868.34
     584 1868.46     600 1873.88     648 1888.11     656 1891.85     668 1893.08
     676 1898.04     700 1905.95     700 1905.97     700 1905.99   705.4 1908.52
#Mann= 5 ,-1,0
       0      .1       0  420.81    .045       0  524.17     .06       0
     600      .1       0     700     .08       0
#XS Ineff= 2 , 0
          342.79 1867.74
Permanent Ineff=
       F       F
Bank Sta=420.81,524.17
XS Rating Curve= 0 ,0
Exp/Cntr(USF)=0,0
Exp/Cntr=0.3,0.1

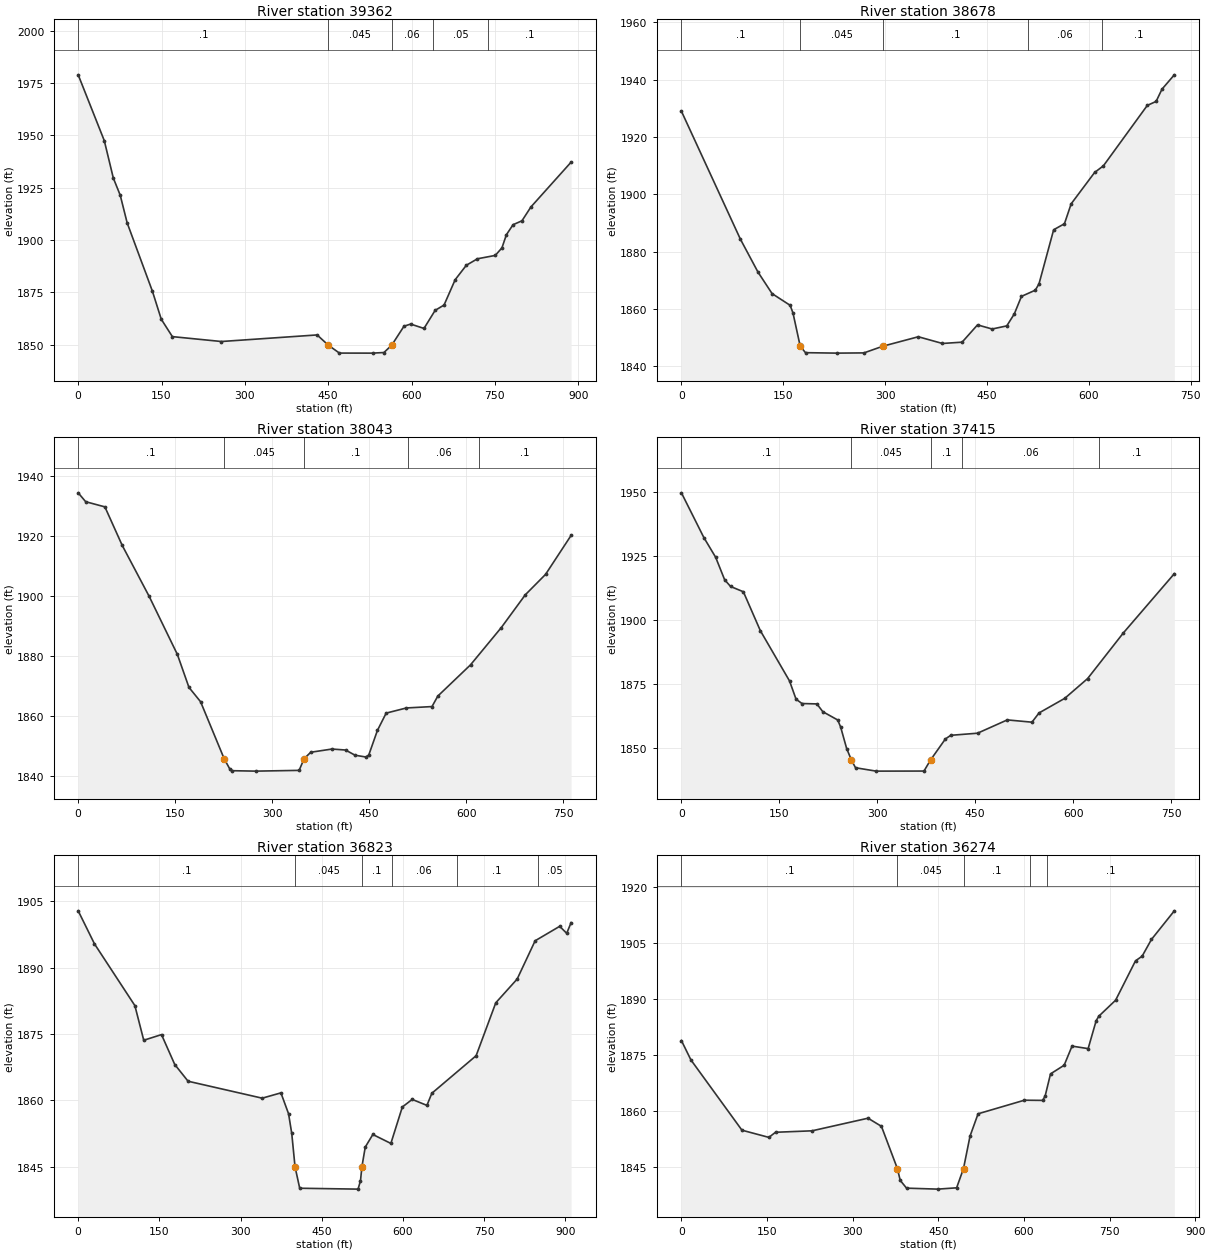
Type RM Length L Ch R = 1 ,39362   ,683.4,683.4,683.4
XS GIS Cut Line= 3
2230027.56515861688856.1479249422230060.94673574  688979.5626736
 2230105.7827388689737.398832584
#Sta/Elev= 30
       0 1978.88      47 1947.42    63.2  1929.6    75.7 1921.34    88.1  1908.2
   133.5 1875.58   149.5 1862.15   169.5 1853.84   257.7 1851.51     430 1854.65
  450.241849.732   470.1 1845.98   529.7 1845.96   550.2 1846.25  564.171849.732
   586.3 1858.81   598.3 1859.84   622.3 1857.75   642.4  1866.4   658.4 1868.92
   678.4 1881.02   698.5 1887.93   718.5 1891.02   750.6 1892.63   762.6 1896.25
   770.6 1902.51   782.6  1907.3   798.6 1909.16   814.7 1915.77     887 1937.16
#Mann= 5 ,-1,0
       0      .1       0  450.24    .045       0  564.17     .06       0
  637.85     .05       0  737.85      .1       0
Bank Sta=450.24,564.17
XS Rating Curve= 0 ,0
Exp/Cntr(USF)=0,0
Exp/Cntr=0.3,0.1

Type RM Length L Ch R = 1 ,38678   ,635.6,635.6,635.6
XS GIS Cut Line= 2
2229371.06745106689208.6317378292229641.68543374689882.046345055
#Sta/Elev= 30
       0 1928.99    86.8 1884.39   112.7 1872.91   133.5 1865.39   160.1 1861.31
   164.3 1858.61  174.911847.041   182.7  1844.8   228.8 1844.64   268.8 1844.72
  296.421847.042   348.8 1850.35   384.3 1848.01   413.3 1848.46     436 1854.49
   457.5 1853.05   479.1 1854.14   490.2 1858.33   500.7 1864.43     521 1866.58
   526.5 1868.77   548.1 1887.66     564 1889.76   573.9 1896.71   608.4 1907.63
   621.4 1909.97     686 1931.02     699 1932.42   707.6 1936.68   725.8 1941.69
#Mann= 5 ,-1,0
       0      .1       0  174.91    .045       0  296.42      .1       0
     510     .06       0     620      .1       0
Bank Sta=174.91,296.42
XS Rating Curve= 0 ,0
Exp/Cntr(USF)=0,0
Exp/Cntr=0.3,0.1

Type RM Length L Ch R = 1 ,38043   ,628,628,628
XS GIS Cut Line= 2
2228753.44326701 689428.375204382229098.14020908690108.309269387
#Sta/Elev= 30
       0 1934.46    11.6  1931.5    41.3 1929.78    68.1 1916.94   109.8 1899.95
   153.4 1880.61   171.3 1869.64   189.3 1864.85  225.721845.883   234.1 1842.59
   238.6 1841.87   274.5 1841.73   341.7 1841.98  349.441845.884   359.7 1848.02
   392.5 1849.09   413.5 1848.76   428.2 1847.03   444.9 1846.44   449.4 1847.09
   462.8  1855.3   476.3 1861.06   507.7 1862.78   547.2 1863.24   556.2 1866.74
   606.8 1877.15   654.4 1889.57   691.5 1900.48   722.8 1907.28   762.3 1920.26
#Mann= 5 ,-1,0
       0      .1       0  225.72    .045       0  349.44      .1       0
     510     .06       0     620      .1       0
Bank Sta=225.72,349.44
XS Rating Curve= 0 ,0
Exp/Cntr(USF)=0,0
Exp/Cntr=0.3,0.1

Type RM Length L Ch R = 1 ,37415   ,591.9,591.9,591.9
XS GIS Cut Line= 2
2228189.49456042689707.0914218412228551.49582201690369.796165049
#Sta/Elev= 30
       0 1949.74    34.3 1932.28    52.5 1924.52    66.2 1915.75    75.3 1913.14
    94.9 1911.07   120.9 1895.86   165.6 1876.22   175.6 1869.08   184.7 1867.39
   207.5 1867.24   216.6  1864.2   239.4 1860.96   243.9 1858.22   253.1 1849.81
  260.421845.311   266.7 1842.29   298.3 1840.97   371.6    1841  381.581845.312
   404.4 1853.55   412.6 1854.97   453.6 1855.79   499.2 1860.99     537  1860.1
   547.9 1863.72   587.2 1869.41   622.2 1877.13   676.9 1894.95   755.1 1918.14
#Mann= 5 ,-1,0
       0      .1       0  260.42    .045       0  381.58      .1       0
     430     .06       0     640      .1       0
Bank Sta=260.42,381.58
XS Rating Curve= 0 ,0
Exp/Cntr(USF)=0,0
Exp/Cntr=0.3,0.1

Type RM Length L Ch R = 1 ,36823   ,548.9,548.9,548.9
XS GIS Cut Line= 3
2227765.80508195689834.9075003082227714.47466562690068.435582395
2228032.65594952690659.662955689
#Sta/Elev= 30
       0 1902.83    30.1 1895.36   104.7 1881.41   121.1 1873.57   153.9 1874.85
   178.4 1868.09     203 1864.31   339.9 1860.48   374.5 1861.68   388.6 1856.96
   394.5 1852.51  400.581844.962   409.2 1840.12     517 1839.92   521.5 1841.82
  524.08 1844.96   530.3 1849.43   544.3 1852.27   577.6 1850.25   598.8 1858.49
     617  1860.2   644.2 1858.85   653.3 1861.59   735.1 1870.08   771.4 1882.04
   810.9 1887.41   844.1 1896.06   889.5 1899.33   902.4 1897.74   910.5 1900.16
#Mann= 6 ,-1,0
       0      .1       0  400.58    .045       0  524.08      .1       0
   579.1     .06       0   699.1      .1       0   849.1     .05       0
Bank Sta=400.58,524.08
XS Rating Curve= 0 ,0
Exp/Cntr(USF)=0,0
Exp/Cntr=0.3,0.1

Type RM Length L Ch R = 1 ,36274   ,754.5,754.5,754.5
XS GIS Cut Line= 2
2227091.44936125690119.0399389252227545.26441222690853.689258902
#Sta/Elev= 30
       0 1878.98    16.6 1873.81     106 1854.98   153.2 1853.05   164.8 1854.42
   228.8 1854.81   326.9 1858.19   350.4 1856.01   378.31844.704   383.3 1841.54
   394.4 1839.45   449.2 1839.19   482.1 1839.54  494.161844.707   505.6 1853.39
   519.7 1859.37   600.8 1863.01   632.8 1862.96   637.2 1864.14   646.6 1870.06
   670.5 1872.38   684.3  1877.5   712.5 1876.83   726.6 1884.32   731.3 1885.53
   760.6 1889.79   795.5 1900.35   807.1 1901.59   823.4 1906.07   863.5 1913.74
#Mann= 5 ,-1,0
       0      .1       0   378.3    .045       0  494.16      .1       0
     610     .06       0     640      .1       0
Bank Sta=378.3,494.16
XS Rating Curve= 0 ,0
Exp/Cntr(USF)=0,0
Exp/Cntr=0.3,0.1

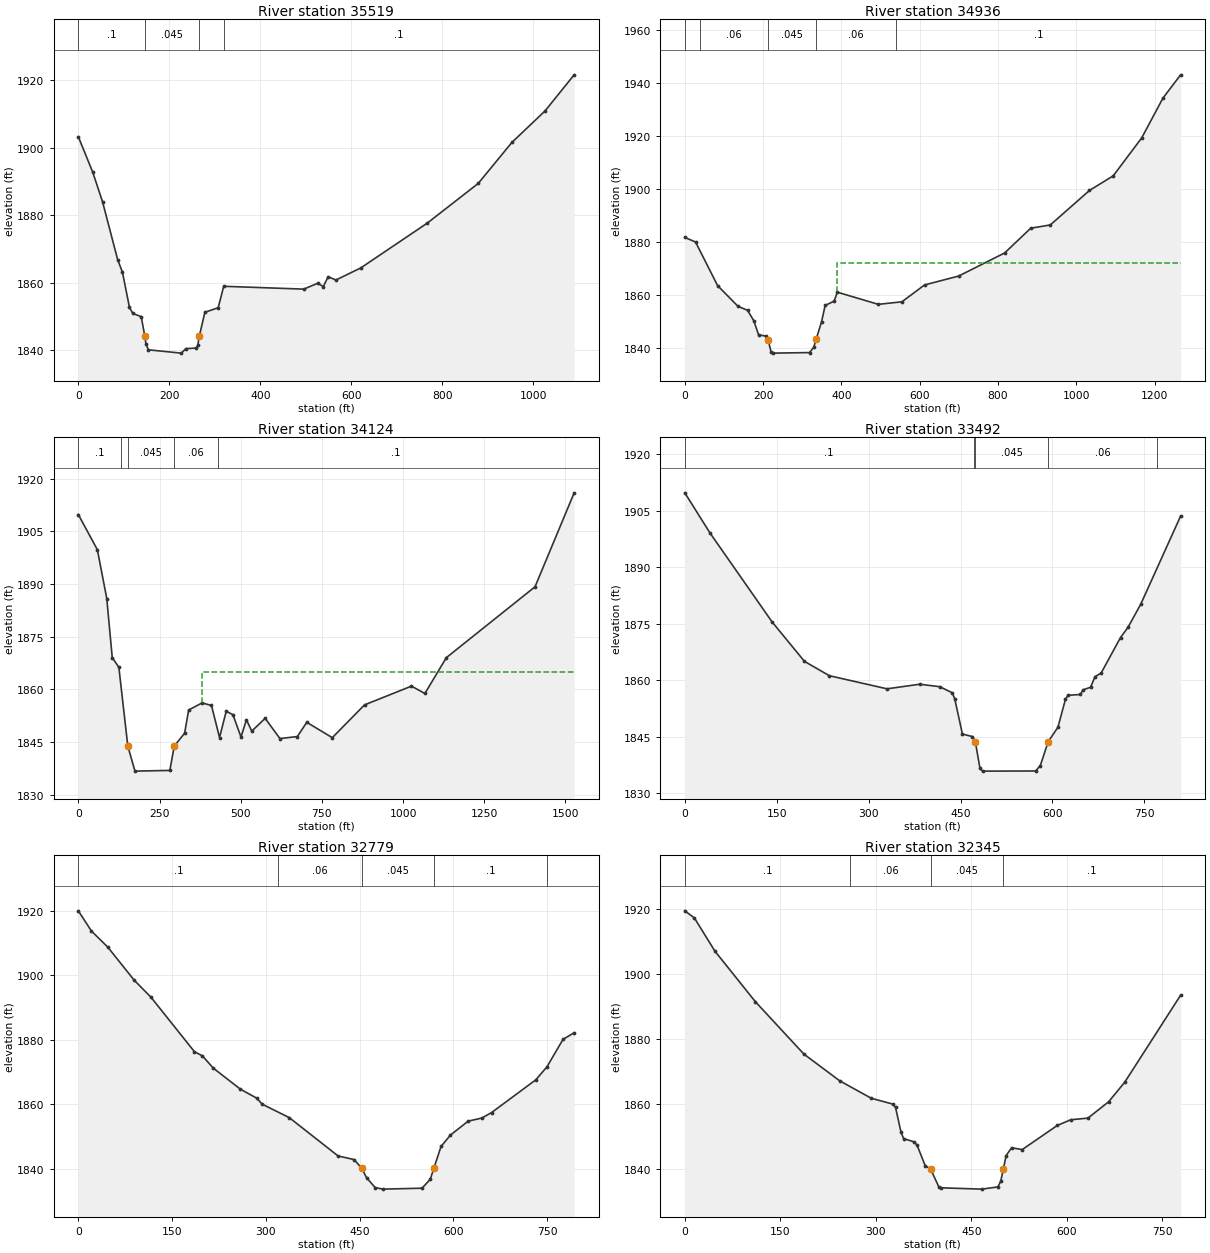
Type RM Length L Ch R = 1 ,35519   ,583.7,583.7,583.7
XS GIS Cut Line= 3
2226477.42604847 690607.401067412226953.24459605690998.391904501
2227413.19377082691111.154007785
#Sta/Elev= 30
       0 1903.26    31.6 1892.78    53.2 1884.01    86.4 1866.89      97 1863.14
   112.3 1852.79   119.7 1850.95   138.2 1850.01  146.05 1844.25   148.5 1842.02
   153.8  1840.2   226.2 1839.22   236.3 1840.54     259 1840.72   262.4 1841.52
  265.86 1844.25     278  1851.3   307.3 1852.66   319.4    1859   495.4 1858.16
   525.7 1859.88   538.3 1858.92   548.9 1861.84   565.9 1860.85   620.6 1864.44
   766.1 1877.64   878.6 1889.44   952.5 1901.56  1025.3 1910.88  1089.4 1921.58
#Mann= 4 ,-1,0
       0      .1       0  146.05    .045       0  265.86     .07       0
     320      .1       0
Bank Sta=146.05,265.86
XS Rating Curve= 0 ,0
Exp/Cntr(USF)=0,0
Exp/Cntr=0.3,0.1

Type RM Length L Ch R = 1 ,34936   ,811.6,811.6,811.6
XS GIS Cut Line= 3
2226288.86060166691261.0307891732227078.80831886691347.616008583
2227531.52824931691214.899885803
#Sta/Elev= 30
       0 1881.65    27.5 1879.91    83.8 1863.45   136.1 1855.61   160.3 1854.14
   176.4 1850.16   188.4 1844.87   208.6 1844.37   212.6 1843.09   220.6 1838.28
   224.7 1837.97   318.6 1838.18   329.3 1840.16  335.471843.169   349.4 1849.85
   358.5 1855.97   381.6 1857.61   389.6 1860.97   494.3 1856.39   554.6 1857.34
   612.4 1863.71   699.5 1867.06   817.1 1875.79   883.6 1885.12   933.7 1886.36
  1033.7 1899.38  1094.3 1904.89  1167.1 1919.21  1221.3 1934.22  1266.5 1943.02
#Mann= 5 ,-1,0
       0      .1       0      40     .06       0   212.6    .045       0
  335.47     .06       0     540      .1       0
#XS Ineff= 2 , 0
                          389.37         1872.06
Permanent Ineff=
       F       F
Bank Sta=212.6,335.47
XS Rating Curve= 0 ,0
Exp/Cntr(USF)=0,0
Exp/Cntr=0.3,0.1

Type RM Length L Ch R = 1 ,34124   ,631.8,631.8,631.8
XS GIS Cut Line= 2
2226207.45046147691998.4961916712227684.97284433692383.445400493
#Sta/Elev= 30
       0 1909.75    58.6 1899.75    87.6 1885.85   104.4 1869.07   124.8 1866.29
   152.41843.866   174.4 1836.76   281.8 1836.96  295.331843.865   327.3 1847.56
   339.7 1854.14     381 1856.17     410 1855.43   434.8 1846.32   455.4 1853.79
   476.1 1852.82   500.9 1846.46   517.6 1851.38     534 1848.14   575.3 1851.78
   620.8 1846.02   674.5  1846.6   703.4 1850.65     782 1846.28   881.2  1855.6
  1025.8 1860.94  1067.2 1858.85  1133.3 1869.05  1406.3  1889.2  1526.8 1915.93
#Mann= 5 ,-1,0
       0      .1       0     130     .06       0   152.4    .045       0
  295.33     .06       0     430      .1       0
#XS Ineff= 2 , 0
                          380.78         1864.85
Permanent Ineff=
       F       F
Bank Sta=152.4,295.33
XS Rating Curve= 0 ,0
Exp/Cntr(USF)=0,0
Exp/Cntr=0.3,0.1

Type RM Length L Ch R = 1 ,33492   ,713.4,713.4,713.4
XS GIS Cut Line= 4
 2226070.1481958691980.4648128692226029.17407345692228.524001464
2226123.34686556692646.415766461 2226101.7656007692773.941422446
#Sta/Elev= 30
       0 1909.73    41.3 1899.03   142.6 1875.44   195.3    1865   235.9  1861.2
     330 1857.72   383.3 1858.94   416.1 1858.28   436.6 1856.66   440.7 1854.93
     453 1845.72   469.4 1845.05  474.091843.691   481.7  1836.6   485.8 1835.88
   572.4 1835.92   580.1 1837.34     5931843.695   608.8  1847.5   621.1  1854.9
   625.2    1856   645.7 1856.22   649.8 1857.45   662.1 1858.13   669.4 1860.93
   679.4 1861.91     711 1871.33   723.2 1874.03   743.9 1880.13   809.1 1903.57
#Mann= 5 ,-1,0
       0      .1       0  471.42     .07       0  474.09    .045       0
     593     .06       0  769.79      .1       0
Bank Sta=474.09,593
XS Rating Curve= 0 ,0
Exp/Cntr(USF)=0,0
Exp/Cntr=0.3,0.1

Type RM Length L Ch R = 1 ,32779   ,433.4,433.4,433.4
XS GIS Cut Line= 2
2225706.76209965691849.9393946772225399.57085526692581.539198582
#Sta/Elev= 30
       0    1920    20.9 1913.74    47.2 1908.73    89.3  1898.5   116.3 1893.19
   185.7 1876.32   198.7 1874.98   216.1 1871.18   259.5 1864.65   285.5 1861.88
   294.2 1860.02   337.6 1855.84   415.7 1843.95   441.4 1842.83   453.6  1840.1
   461.3  1837.2     475 1834.15   487.3 1833.66   550.1 1833.95   563.2 1836.71
  569.151840.237   580.5 1846.91   595.6 1850.44   623.9 1854.76   645.6  1855.7
   661.4 1857.42   732.3  1867.6     750 1871.61   775.7 1880.13   793.5 1882.17
#Mann= 5 ,-1,0
       0      .1       0     320     .06       0   453.6    .045       0
  569.15      .1       0     750     .06       0
Bank Sta=453.6,569.15
XS Rating Curve= 0 ,0
Exp/Cntr(USF)=0,0
Exp/Cntr=0.3,0.1

Type RM Length L Ch R = 1 ,32345   ,504.4,504.4,504.4
XS GIS Cut Line= 2
2225309.08972194691696.4761488292225053.77779171 692432.14842801
#Sta/Elev= 30
       0 1919.46      15 1917.28    47.3 1907.03   110.8 1891.45     187  1875.3
   243.3 1867.05   292.9 1861.67   326.8 1859.87     331 1858.85   339.5 1851.24
   343.7 1849.23   360.6 1848.21   364.9 1847.15   377.6 1840.86     386 1839.89
   398.7 1834.46     403 1834.06   466.4 1833.66   491.6 1834.33   496.1 1836.05
   500.4 1839.92   504.6 1843.97   513.1  1846.4     530 1845.86     585 1853.29
   606.2 1855.05   633.1 1855.55   665.5 1860.57   690.9 1866.61   778.7 1893.45
#Mann= 4 ,-1,0
       0      .1       0     260     .06       0     386    .045       0
   500.4      .1       0
Bank Sta=386,500.4
XS Rating Curve= 0 ,0
Exp/Cntr(USF)=0,0
Exp/Cntr=0.3,0.1

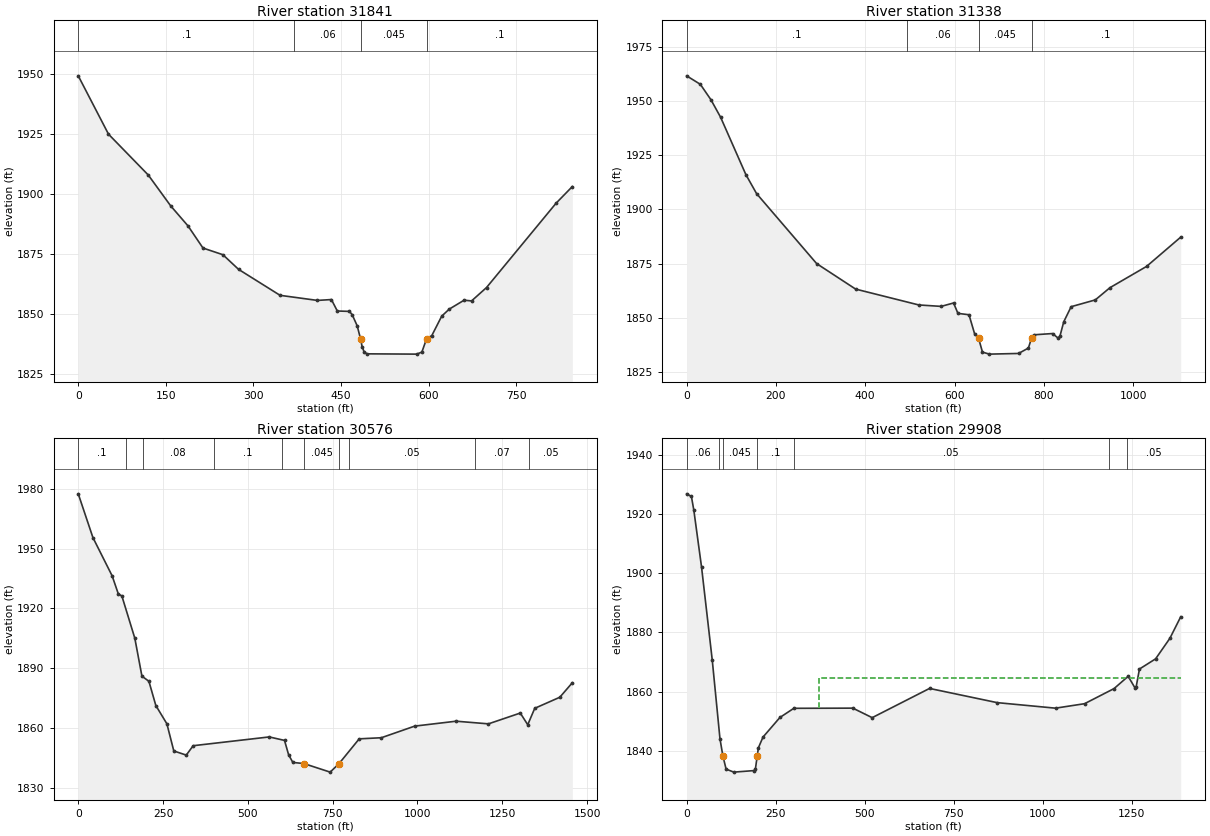
Type RM Length L Ch R = 1 ,31841   ,503.2,503.2,503.2
XS GIS Cut Line= 2
2224875.55737008691504.5706621032224585.19126107692299.153595548
#Sta/Elev= 30
       0 1949.32    51.8    1925   119.9 1907.97   158.2 1895.14     188 1886.74
   213.6 1877.53   247.7 1874.75   274.5 1868.65   345.6 1857.82   409.5  1855.7
   433.5 1856.06   443.6 1851.29   464.4 1851.12   469.1 1849.74   477.6 1845.13
   483.4 1839.67   486.1  1836.4   489.7 1834.12   494.7 1833.43   579.8 1833.31
   588.4 1834.18   596.41839.662   605.4 1841.04   622.4 1849.15   635.2 1852.06
   660.7 1855.79   673.5 1855.49   699.1 1861.07   818.3 1896.25     846 1903.16
#Mann= 4 ,-1,0
       0      .1       0     370     .06       0   483.4    .045       0
   596.4      .1       0
Bank Sta=483.4,596.4
XS Rating Curve= 0 ,0
Exp/Cntr(USF)=0,0
Exp/Cntr=0.3,0.1

Type RM Length L Ch R = 1 ,31338   ,761.9,761.9,761.9
XS GIS Cut Line= 4
2224519.12098514691232.7052649022224336.48599968691435.960354381
2224158.40708067692057.2722123972224195.82316923 692240.52084286
#Sta/Elev= 30
       0 1961.64    30.7 1957.72    54.4 1950.61    76.1 1942.52   132.7 1916.05
   156.6  1907.3   291.2 1874.99   378.5 1863.23     520 1855.91     570 1855.25
   597.9 1856.82   607.6 1852.03   632.4 1851.39   644.9 1842.65   653.7 1840.66
   662.6 1834.14   678.1 1833.22   743.4 1833.53   765.5 1836.03   772.5 1840.66
     778 1842.14   819.6 1842.72   832.1 1840.59   836.3 1841.66   844.6 1848.12
   861.2 1855.11   915.3 1858.24   948.1 1863.88  1030.1 1873.69  1106.6  1887.2
#Mann= 4 ,-1,0
       0      .1       0  493.25     .06       0   653.7    .045       0
   772.5      .1       0
Bank Sta=653.7,772.5
XS Rating Curve= 0 ,0
Exp/Cntr(USF)=0,0
Exp/Cntr=0.3,0.1

Type RM Length L Ch R = 1 ,30576   ,668.1,668.1,668.1
XS GIS Cut Line= 4
2223495.95165029690997.5980265162223605.08434569691164.521015617
2223452.48954365691929.6749515262223755.78595837692297.515920726
#Sta/Elev= 30
       0 1977.49    43.2 1955.57    99.9 1936.37   118.3 1927.21   128.5 1926.31
   166.8 1905.05   187.7 1886.06   208.3 1883.47   228.7 1871.33   261.3 1862.15
   281.7 1848.53   318.4 1846.46   338.8 1851.17   563.1 1855.57     608 1853.83
   620.2 1846.58   632.6 1842.78   665.1 1842.22   742.6 1837.92   768.7 1842.18
   828.2 1854.61   893.5 1855.17   991.7 1860.99  1113.8 1863.46  1209.2 1862.13
    1303 1867.55    1325 1861.68  1345.6 1869.92  1419.5 1875.47  1456.4 1882.74
#Mann= 10 ,-1,0
       0      .1       0     140     .06       0     190     .08       0
  399.43      .1       0  599.43     .08       0   665.1    .045       0
   768.7      .1       0  799.43     .05       0 1169.65     .07       0
 1329.65     .05       0
Bank Sta=665.1,768.7
XS Rating Curve= 0 ,0
Exp/Cntr(USF)=0,0
Exp/Cntr=0.3,0.1

Type RM Length L Ch R = 1 ,29908   ,739.7,739.7,739.7
XS GIS Cut Line= 3
2222847.14983254691374.4463501112223081.90216729691953.654134703
 2223754.3703708692312.052905947
#Sta/Elev= 30
       0 1926.85    13.4 1925.95    20.2  1921.3    41.8 1902.15      72 1870.55
    93.6 1844.03  101.741838.269   110.8 1833.79   132.4 1832.78   190.2 1833.31
   192.9 1833.74  198.231838.271   201.5 1841.02   214.4 1844.63   261.9 1851.26
   300.9 1854.35   466.6 1854.41   520.9 1851.19   681.9 1861.07   871.7 1856.27
  1035.5  1854.4  1117.1 1855.91  1199.9 1861.02  1239.5 1865.17  1259.1 1861.15
  1262.1 1861.72  1271.2 1867.63  1316.5 1871.07  1356.6 1878.01    1387 1885.29
#Mann= 7 ,-1,0
       0     .06       0      90      .1       0  101.74    .045       0
  198.23      .1       0     300     .05       0 1184.97     .07       0
 1234.97     .05       0
#XS Ineff= 2 , 0
                          372.75         1864.47
Permanent Ineff=
       F       F
Bank Sta=101.74,198.23
XS Rating Curve= 0 ,0
Exp/Cntr(USF)=0,0
Exp/Cntr=0.3,0.1