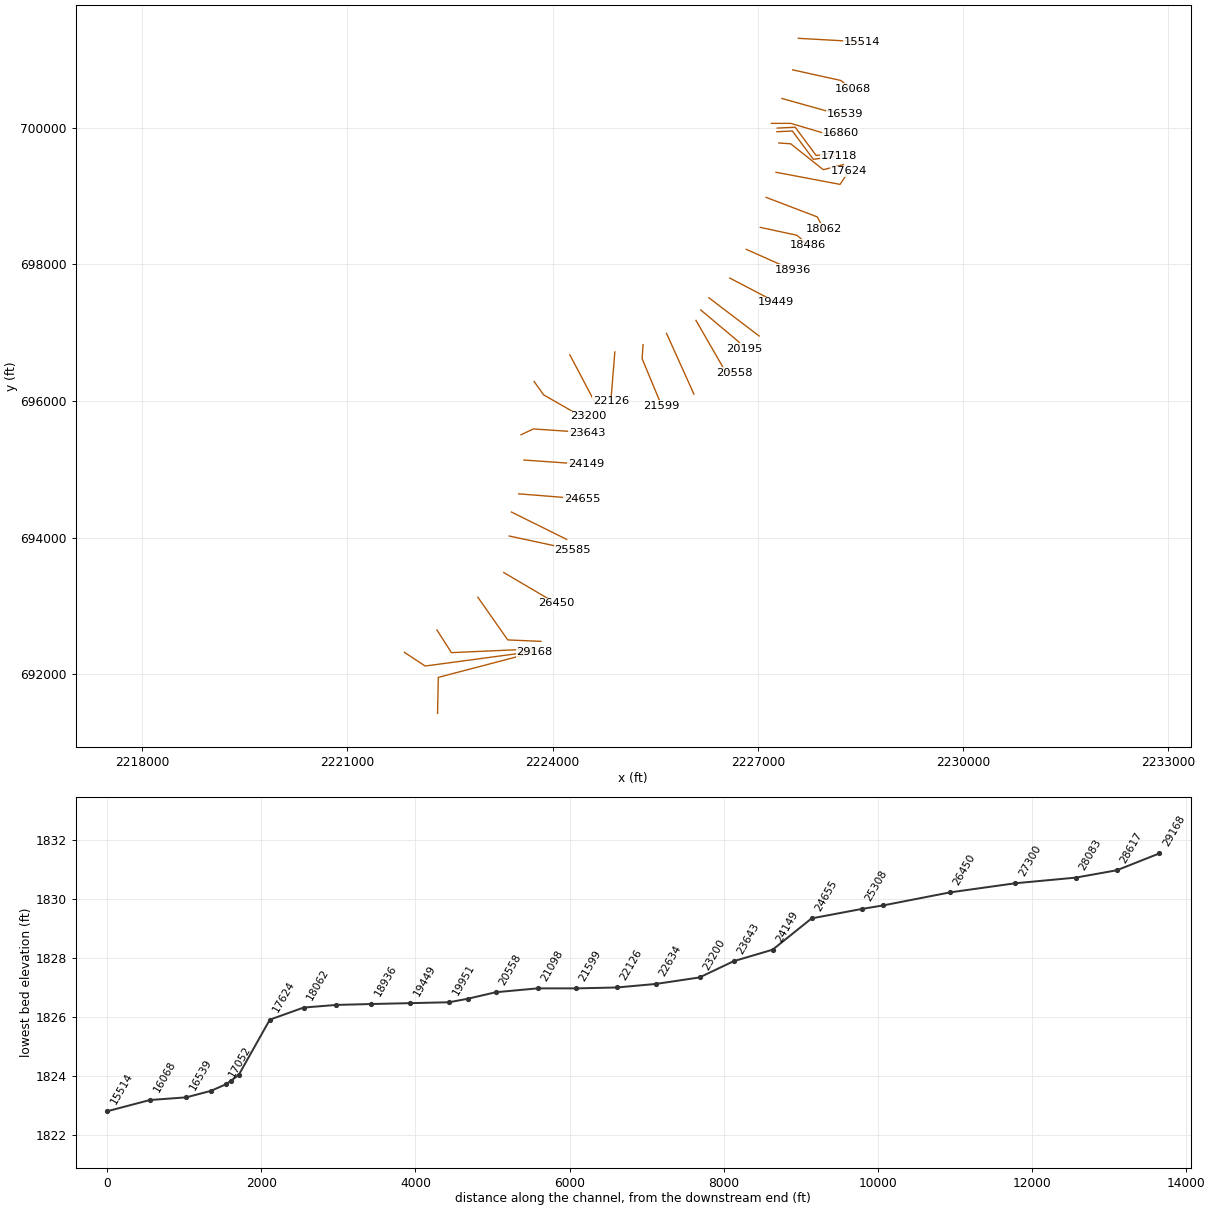
HEC-RAS study MIDFKRIV.prj: MIDFKRIV

--- MIDFKRIV.g01 (geometry) --- (continued)

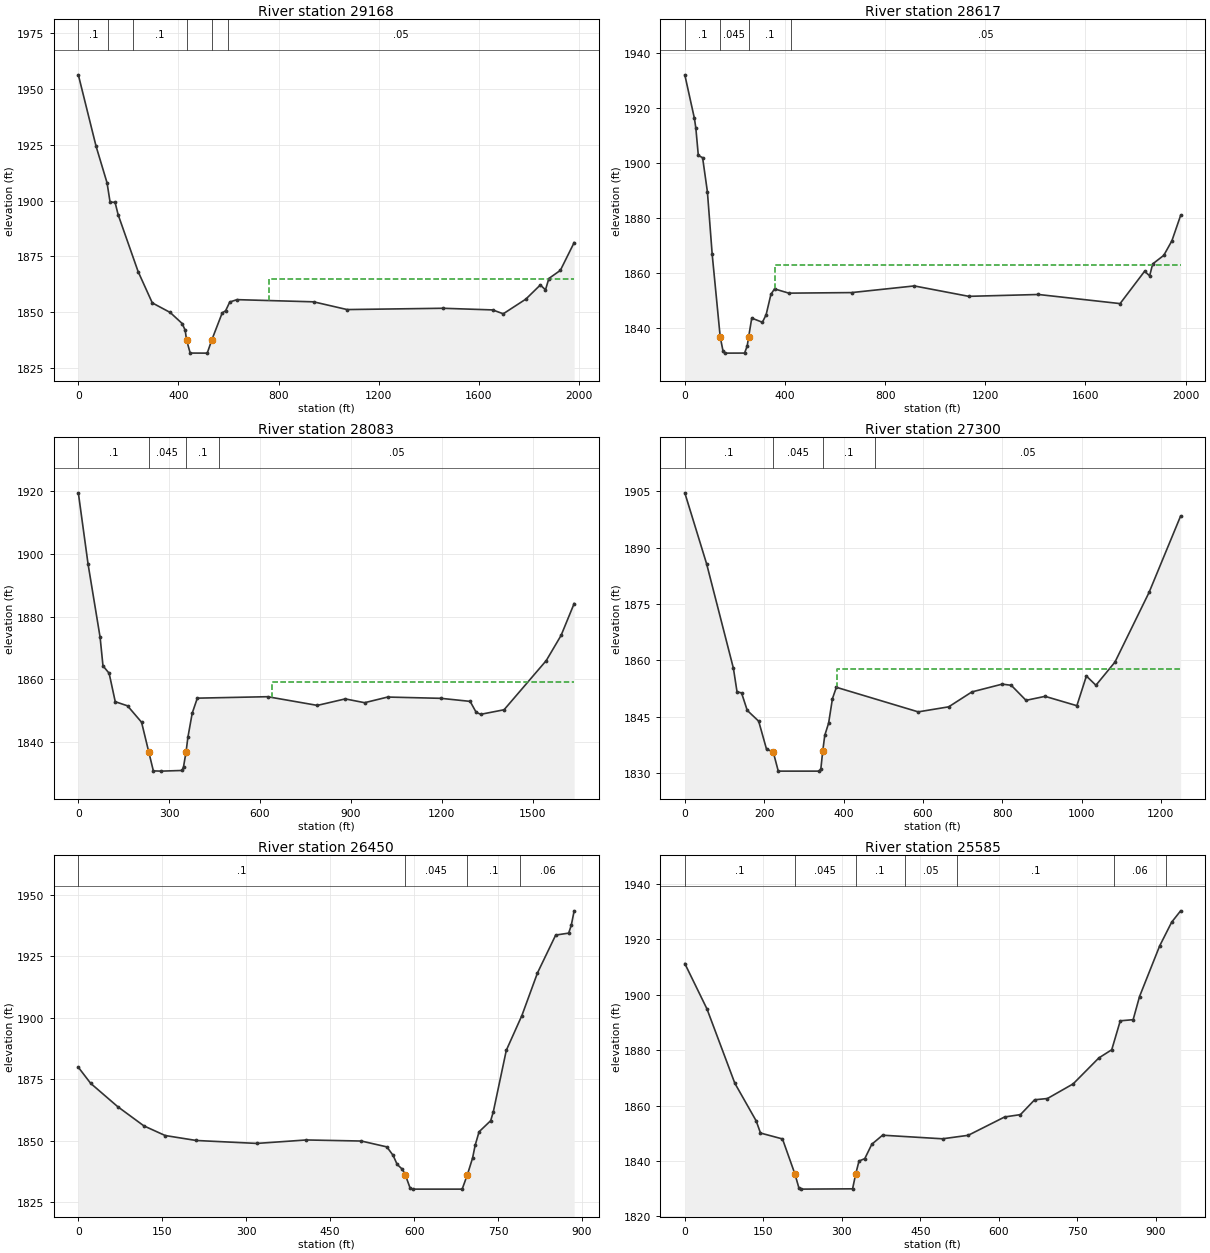
Type RM Length L Ch R = 1 ,29168   ,551.3,551.3,551.3
XS GIS Cut Line= 3
2222317.13164172691430.3870034612222328.48342563691957.031929642
2223734.94913055692325.788416989
#Sta/Elev= 30
       0 1956.37    70.8 1924.35   114.8 1907.89   126.8 1899.27   146.8 1899.17
   158.8 1893.71   238.8 1868.13   295.5 1854.07   366.9 1849.78   414.9 1844.81
   426.9 1841.77  432.361837.405   446.9 1831.57     515 1831.54  532.991837.409
   574.7 1849.55   588.5 1850.57     605 1854.47     634 1855.53     940 1854.55
  1073.8 1851.08  1456.9 1851.66  1655.4 1850.92  1697.5 1849.18  1787.7 1855.76
  1845.6 1862.11  1866.3 1859.92  1879.7 1865.01  1925.6 1868.66  1980.8 1881.13
#Mann= 6 ,-1,0
       0      .1       0     120     .06       0     220      .1       0
  432.36    .045       0  532.99      .1       0  596.77     .05       0
#XS Ineff= 2 , 0
                          763.14         1864.67
Permanent Ineff=
       F       F
Bank Sta=432.36,532.99
XS Rating Curve= 0 ,0
Exp/Cntr(USF)=0,0
Exp/Cntr=0.3,0.1

Type RM Length L Ch R = 1 ,28617   ,533.6,533.6,533.6
XS GIS Cut Line= 3
2221832.72706839692322.8437539852222136.50921441692123.199441189
2223738.77446783692338.366475247
#Sta/Elev= 30
       0 1932.11    38.4 1916.28    44.1 1912.74      54 1902.81    71.1    1902
    90.3 1889.59   109.4 1866.86   141.4 1836.86   152.5 1831.79   159.8 1830.97
   238.7 1830.99   249.2 1833.54  254.841836.799   267.4  1843.7   309.9 1842.18
   324.8 1844.93     344 1852.36   358.3 1854.31   415.6 1852.77   665.9 1852.97
   916.5 1855.39    1134 1851.61  1412.5 1852.28  1738.4 1848.97  1836.3 1860.72
  1856.5 1859.05  1868.6 1863.39    1913 1866.51  1945.3 1871.79  1980.2 1881.01
#Mann= 4 ,-1,0
       0      .1       0   141.4    .045       0  254.84      .1       0
  423.51     .05       0
#XS Ineff= 2 , 0
                          359.44         1862.96
Permanent Ineff=
       F       F
Bank Sta=141.4,254.84
XS Rating Curve= 0 ,0
Exp/Cntr(USF)=0,0
Exp/Cntr=0.3,0.1

Type RM Length L Ch R = 1 ,28083   ,783.1,783.1,783.1
XS GIS Cut Line= 3
2222308.28242617692649.7319632512222520.31689104692318.899603035
 2223763.3391532692374.056978048
#Sta/Elev= 30
       0 1919.42    32.2 1896.67    71.9 1873.38    81.4 1864.27   101.7 1861.91
   121.9 1852.85   162.5 1851.53   208.8  1846.3  232.231836.959   247.7  1830.8
   274.1 1830.72   342.7 1830.93   347.5 1832.18  355.861836.958   361.7 1841.45
     376 1849.18   392.9 1853.98     625 1854.44   789.2 1851.67   881.3 1853.74
   945.3 1852.53  1021.4 1854.33  1197.6 1853.92  1293.7 1852.95  1313.7 1849.45
  1328.9 1848.83  1405.8 1850.28  1545.1 1865.96    1594 1873.97  1637.2 1884.14
#Mann= 4 ,-1,0
       0      .1       0  232.23    .045       0  355.86      .1       0
  462.95     .05       0
#XS Ineff= 2 , 0
                          640.02          1859.2
Permanent Ineff=
       F       F
Bank Sta=232.23,355.86
XS Rating Curve= 0 ,0
Exp/Cntr(USF)=0,0
Exp/Cntr=0.3,0.1

Type RM Length L Ch R = 1 ,27300   ,849.6,849.6,849.6
XS GIS Cut Line= 3
 2222905.9900221693130.2265643772223343.19265774692504.949432625
2223829.48468336692483.918180626
#Sta/Elev= 30
       0 1904.59      55 1885.69   122.5 1857.91   131.6 1851.67   143.1 1851.33
   157.4 1846.69   186.2 1843.82   206.2 1836.29   222.6 1835.75   235.6 1830.53
   338.4 1830.53   342.9 1831.13  347.631835.839   352.8 1840.05   362.5 1843.32
   372.2 1849.85     382 1852.84   588.3  1846.3   665.1 1847.64   723.6 1851.61
     800 1853.68   822.8 1853.37     860 1849.37   908.1 1850.43   988.2 1847.94
  1012.2 1855.84  1036.2 1853.38  1084.2 1859.55  1170.2  1878.1  1249.7 1898.42
#Mann= 4 ,-1,0
       0      .1       0   222.6    .045       0  347.63      .1       0
     480     .05       0
#XS Ineff= 2 , 0
                          384.62         1857.64
Permanent Ineff=
       F       F
Bank Sta=222.6,347.63
XS Rating Curve= 0 ,0
Exp/Cntr(USF)=0,0
Exp/Cntr=0.3,0.1

Type RM Length L Ch R = 1 ,26450   ,865.3,865.3,865.3
XS GIS Cut Line= 2
2223285.19291221693490.5080106782224048.61152636693041.084244031
#Sta/Elev= 30
       0 1879.84      22  1873.3    70.3 1863.81   117.1 1855.98   155.1 1852.05
   210.6 1850.03   319.1 1848.83   407.3 1850.24   505.7  1849.8   551.2 1847.42
   562.4 1843.97   569.7 1840.26     579  1838.3  584.261836.013     593 1830.52
   597.6 1830.22   685.8 1830.22  694.99 1836.01   704.4 1842.87     709 1848.06
     716 1853.57   736.8  1858.1   741.5 1861.77   764.7 1886.77   792.5  1900.9
   820.4 1918.28   852.9 1933.67   876.1 1934.46   880.7 1937.62   885.9 1943.54
#Mann= 4 ,-1,0
       0      .1       0  584.26    .045       0  694.99      .1       0
     790     .06       0
Bank Sta=584.26,694.99
XS Rating Curve= 0 ,0
Exp/Cntr(USF)=0,0
Exp/Cntr=0.3,0.1

Type RM Length L Ch R = 1 ,25585   ,277.4,277.4,277.4
XS GIS Cut Line= 2
2223362.83099682694025.4354663892224288.89497444693826.348990964
#Sta/Elev= 30
       0 1911.32    42.3 1894.93    95.6 1868.04   136.4 1854.43   144.6 1850.05
   186.6 1847.92  210.051835.423   218.2 1830.08   222.3 1829.78   320.5 1829.89
  326.721835.428   332.8 1839.93   343.8  1840.8   357.3 1846.01   377.8 1849.27
   492.3 1847.97   541.4 1849.23     611 1855.86   641.2 1856.71   668.3 1862.07
   692.8 1862.53   741.9 1867.82     791  1877.2   815.6 1880.15   831.9 1890.61
   856.5 1891.02   868.7 1899.39   907.2  1917.7   930.1 1926.27   947.2 1930.36
#Mann= 7 ,-1,0
       0      .1       0  210.05    .045       0  326.72      .1       0
     420     .05       0     520      .1       0     820     .06       0
     920      .1       0
Bank Sta=210.05,326.72
XS Rating Curve= 0 ,0
Exp/Cntr(USF)=0,0
Exp/Cntr=0.3,0.1

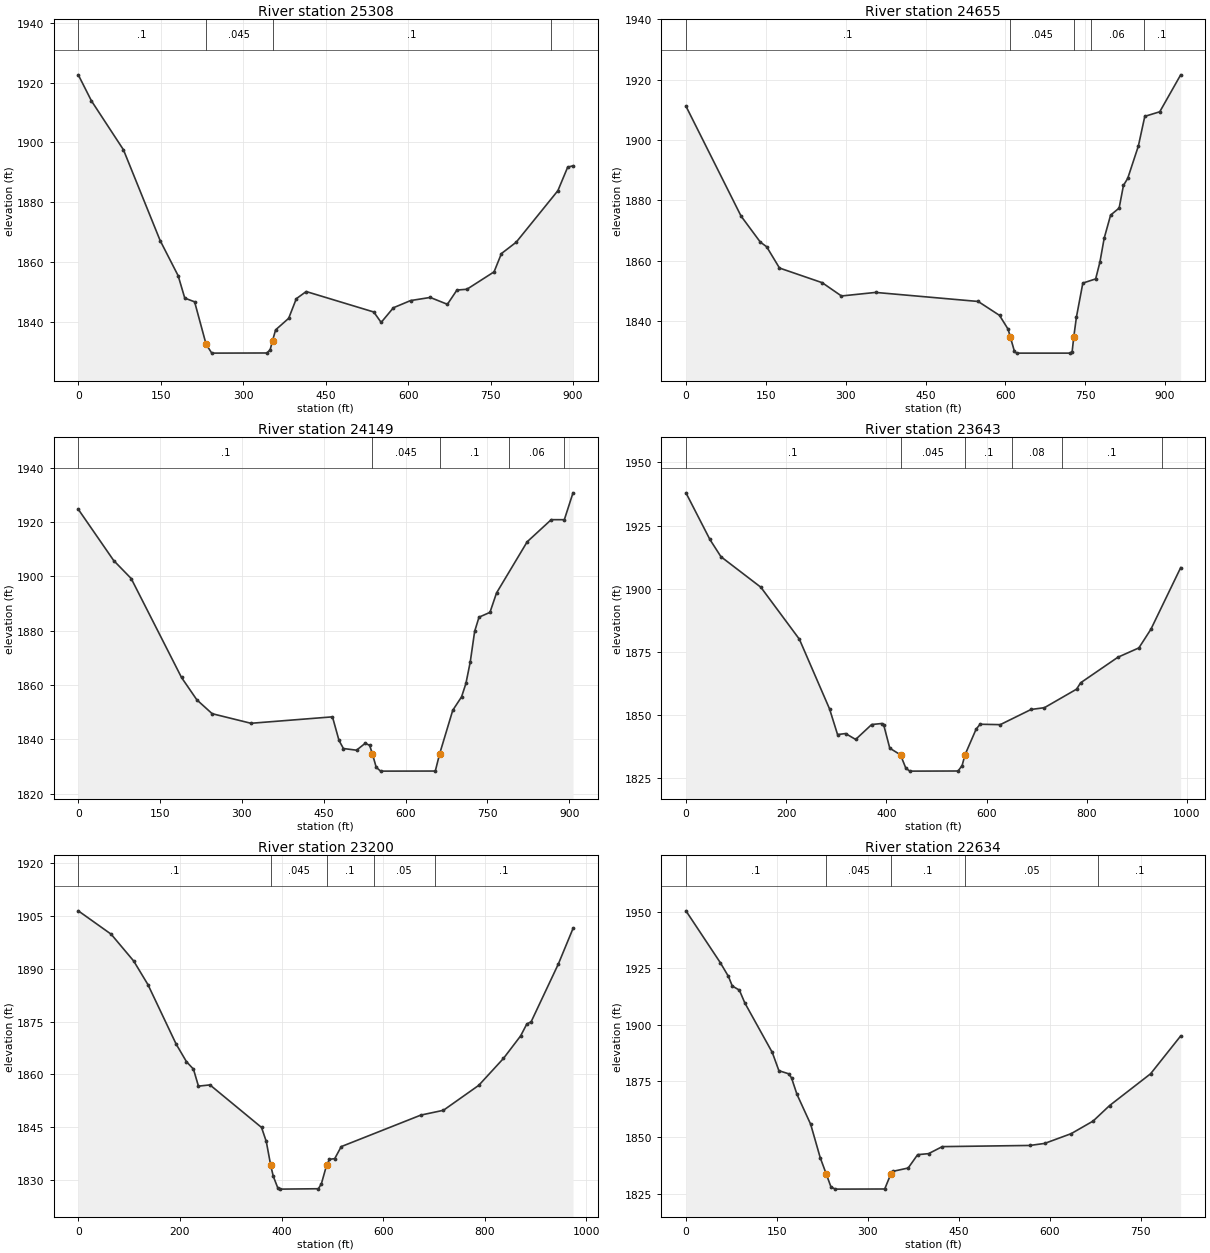
Type RM Length L Ch R = 1 ,25308   ,652.6,652.6,652.6
XS GIS Cut Line= 2
2223398.63855341694375.2140728892224204.84756504693975.413702363
#Sta/Elev= 30
       0 1922.57      24 1913.86    82.1 1897.57   148.9 1867.25   181.7 1855.49
   193.7 1848.03   211.6 1846.79   232.5 1832.62   242.8 1829.66   342.9 1829.71
   348.9 1830.73   353.4 1833.83   358.9 1837.42   382.7 1841.28   396.6 1847.83
   414.6 1850.22   537.5 1843.39   550.9 1839.91   573.2 1844.81   604.5 1847.21
   640.2 1848.25   671.4 1845.96   688.8 1850.72   706.9 1850.98   756.3 1856.79
   769.7  1862.9   796.5 1866.68   872.4  1883.9   890.2 1891.74   899.9  1892.2
#Mann= 4 ,-1,0
       0      .1       0   232.5    .045       0   353.4      .1       0
     860     .06       0
Bank Sta=232.5,353.4
XS Rating Curve= 0 ,0
Exp/Cntr(USF)=0,0
Exp/Cntr=0.3,0.1

Type RM Length L Ch R = 1 ,24655   ,506,506,506
XS GIS Cut Line= 2
2223505.00994551694641.8707480582224431.41500596694568.179445277
#Sta/Elev= 30
       0 1911.24   103.5 1874.79   139.6 1866.18   151.6 1864.61   175.7 1857.56
     256 1852.69   292.1 1848.29   356.3 1849.47   548.9 1846.47     589 1841.86
   605.1 1837.28  609.181834.781   617.1 1829.88   621.1 1829.34   721.4 1829.34
   725.4 1829.75  728.541834.778   733.5 1841.31   745.5 1852.56   769.6 1853.95
   777.6 1859.53   785.6 1867.43   797.7 1875.11   813.7 1877.44   821.8 1884.95
   829.8 1887.28   849.8    1898   861.9 1907.85     890 1909.37   929.3 1921.62
#Mann= 5 ,-1,0
       0      .1       0  609.18    .045       0  728.54      .1       0
     760     .06       0     860      .1       0
Bank Sta=609.18,728.54
XS Rating Curve= 0 ,0
Exp/Cntr(USF)=0,0
Exp/Cntr=0.3,0.1

Type RM Length L Ch R = 1 ,24149   ,506.1,506.1,506.1
XS GIS Cut Line= 2
2223579.39326685695136.2635087932224484.03337386695073.242504728
#Sta/Elev= 30
       0 1924.67    64.9  1905.8      97 1899.17   189.2 1862.76   217.3 1854.53
   245.4 1849.42   316.5 1845.89   465.9 1848.26   477.9 1839.57     486  1836.6
     510 1835.99   526.1 1838.55   534.1 1837.74  539.231834.527   546.1 1829.69
   554.1 1828.28   654.4 1828.31  662.171834.528   686.4 1850.69   702.5 1855.61
   710.5 1860.54   718.5 1868.53   726.5 1879.71   734.5 1884.95   754.6 1886.72
   766.6 1893.86   822.8  1912.7   866.9 1920.84   890.9 1920.83   906.8 1930.72
#Mann= 5 ,-1,0
       0      .1       0  539.23    .045       0  662.17      .1       0
     790     .06       0     890      .1       0
Bank Sta=539.23,662.17
XS Rating Curve= 0 ,0
Exp/Cntr(USF)=0,0
Exp/Cntr=0.3,0.1

Type RM Length L Ch R = 1 ,23643   ,442.9,442.9,442.9
XS GIS Cut Line= 3
 2223536.9925379695505.7523419822223718.15320897695591.292560311
2224503.39204698695538.401734383
#Sta/Elev= 30
       0 1937.94    47.8  1919.5    69.9 1912.67   149.5 1900.61   226.4 1880.05
   286.6  1852.5   302.6 1842.35   318.6 1842.75   338.7 1840.42   370.7 1846.32
   390.8 1846.72   394.8 1846.08   406.8 1836.97  428.251834.323   438.9 1829.03
   446.9 1827.89   543.1 1827.94   551.2  1830.1   556.91834.321   579.2 1844.52
   587.1 1846.43   627.3 1846.27   688.8 1852.27   715.5 1852.98   779.7 1860.31
   787.7 1862.82   862.2 1872.94     904 1876.62     928 1884.01   987.4 1908.36
#Mann= 6 ,-1,0
       0      .1       0  428.25    .045       0   556.9      .1       0
  650.34     .08       0  750.34      .1       0  950.34     .06       0
Bank Sta=428.25,556.9
XS Rating Curve= 0 ,0
Exp/Cntr(USF)=0,0
Exp/Cntr=0.3,0.1

Type RM Length L Ch R = 1 ,23200   ,566.2,566.2,566.2
XS GIS Cut Line= 4
 2223728.7248893696285.8803833712223868.52719896696089.406402163
2224332.18033478695823.1191282172224524.12298885695775.164117856
#Sta/Elev= 30
       0 1906.49    64.7 1899.84   109.1 1892.21     137 1885.53   192.5 1868.62
   212.9 1863.59   226.7 1861.46   236.5 1856.63   259.2 1856.98   360.7 1844.88
     370 1840.89  378.751834.097   383.7 1831.03     393 1827.57   397.6 1827.34
   472.5 1827.45   478.4 1828.83  488.641834.098   494.4 1835.82   504.7 1836.01
   517.5 1839.43   674.3  1848.4   718.6 1849.76   788.2 1856.86   836.8 1864.51
   870.6 1870.92   882.8 1874.31   891.3 1874.94   944.9 1891.39   973.7 1901.47
#Mann= 5 ,-1,0
       0      .1       0  378.75    .045       0  488.64      .1       0
  581.14     .05       0  701.14      .1       0
Bank Sta=378.75,488.64
XS Rating Curve= 0 ,0
Exp/Cntr(USF)=0,0
Exp/Cntr=0.3,0.1

Type RM Length L Ch R = 1 ,22634   ,507.9,507.9,507.9
XS GIS Cut Line= 2
 2224250.9953978696675.1566325152224631.45659488695953.375291843
#Sta/Elev= 30
       0 1950.34    56.5 1927.46    70.1 1921.29    76.4 1917.06    88.1 1915.23
    97.1 1909.56   142.4 1887.63   153.3 1879.56   169.5 1878.18   174.1 1876.38
   183.1 1869.09   205.7 1855.83   221.4 1841.08   231.4 1833.81   239.2 1828.06
   246.4 1827.12   327.8 1827.18   337.91833.813   341.4    1835   366.5 1836.47
   382.1 1842.38   400.1 1842.83   422.8 1845.94   567.4 1846.46   591.6 1847.36
   635.3 1851.68   671.5 1857.26   698.6 1864.11   766.3  1878.2   815.9 1894.94
#Mann= 5 ,-1,0
       0      .1       0   231.4    .045       0   337.9      .1       0
     460     .05       0     680      .1       0
Bank Sta=231.4,337.9
XS Rating Curve= 0 ,0
Exp/Cntr(USF)=0,0
Exp/Cntr=0.3,0.1

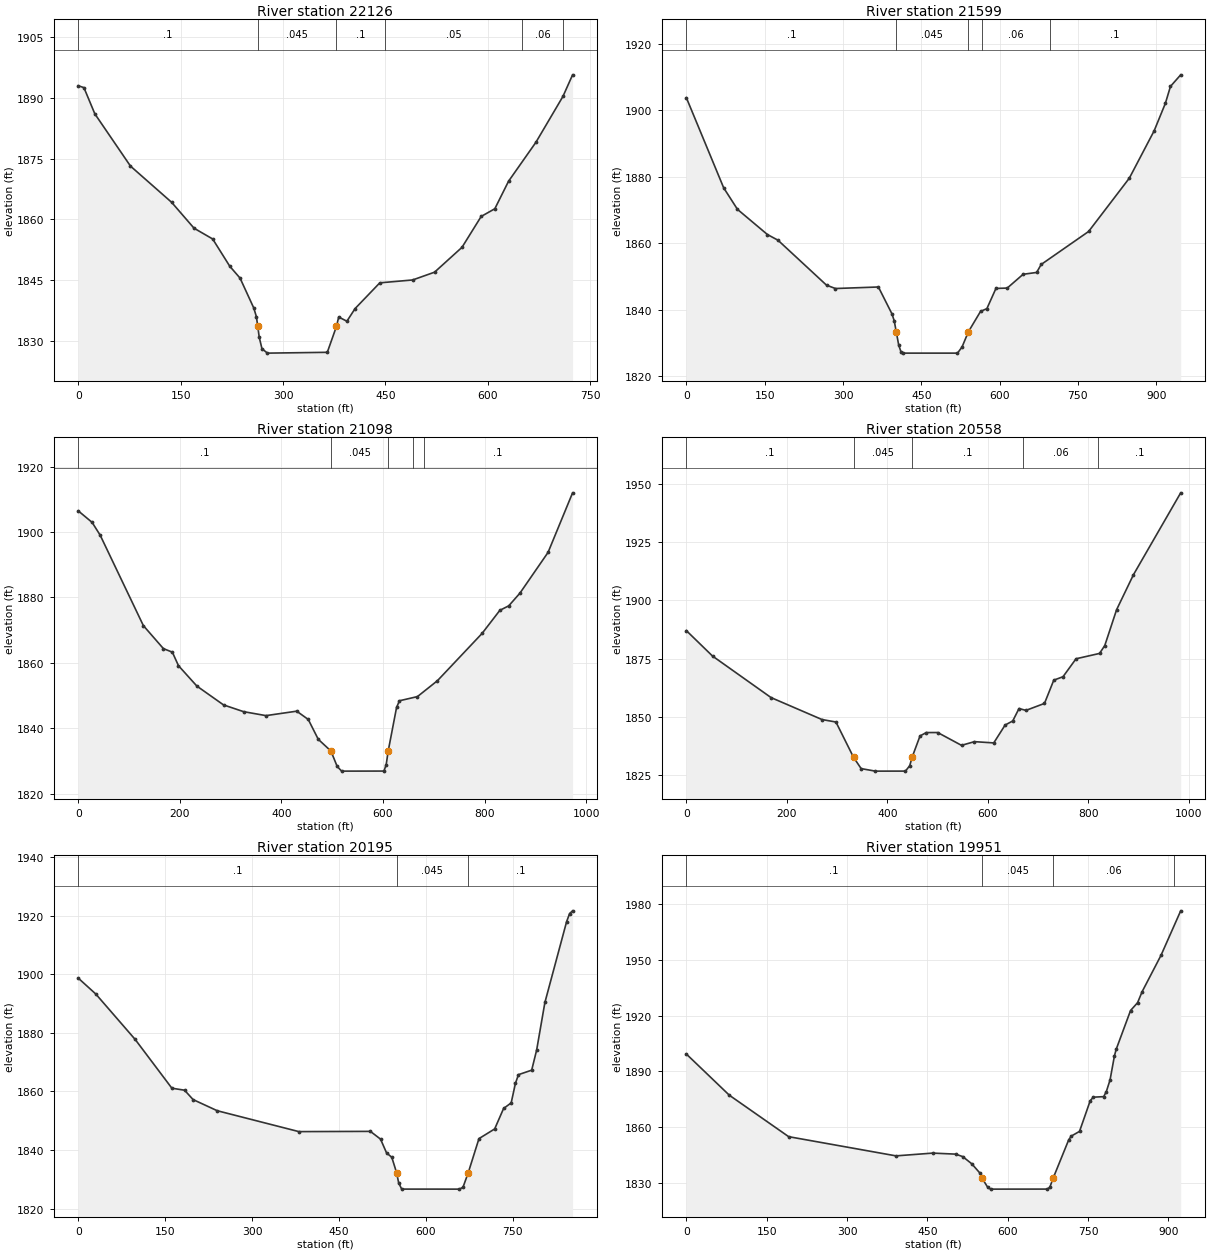
Type RM Length L Ch R = 1 ,22126   ,527.6,527.6,527.6
XS GIS Cut Line= 2
2224909.07120866696717.4085508442224850.42249991695995.717431786
#Sta/Elev= 30
       0 1892.97     8.3  1892.5    24.3 1886.03    76.5 1873.14   136.7 1864.22
   169.6 1857.82   196.9 1855.16     222 1848.42     237 1845.51   257.1 1838.13
   260.9 1836.01  262.971833.572   265.1  1830.9   269.1 1828.09   277.1    1827
   364.8  1827.2  378.181833.577   381.5 1835.91   393.5 1834.87   405.5 1837.99
   441.7 1844.34   489.8 1845.05   521.9 1846.97   562.1  1853.1   590.2 1860.72
   610.2 1862.62   630.3 1869.41   670.4 1879.02     710 1890.34   724.1 1895.66
#Mann= 6 ,-1,0
       0      .1       0  262.97    .045       0  378.18      .1       0
     450     .05       0     650     .06       0     710      .1       0
Bank Sta=262.97,378.18
XS Rating Curve= 0 ,0
Exp/Cntr(USF)=0,0
Exp/Cntr=0.3,0.1

Type RM Length L Ch R = 1 ,21599   ,500.2,500.2,500.2
XS GIS Cut Line= 3
2225320.97309492696824.207470484  2225308.044874696618.848158598
2225591.68925696695934.223324535
#Sta/Elev= 30
       0 1903.74    71.5 1876.64    97.9 1870.18   155.3 1862.61   175.4 1860.92
   268.4  1847.4   285.5 1846.39   367.8 1846.85   393.8 1838.76   398.1 1836.69
  401.99 1833.38   406.7 1829.39   411.1 1827.34   415.3 1826.97   519.3 1826.97
     528 1828.81  540.121833.382   563.4  1839.5   575.6 1840.35   592.9 1846.41
   614.6 1846.53     645 1850.67   670.9 1851.22   679.5 1853.61   770.4 1863.53
   848.4 1879.56     896 1893.81   917.4 1902.03   927.2 1907.14   946.8 1910.62
#Mann= 5 ,-1,0
       0      .1       0  401.99    .045       0  540.12      .1       0
  565.77     .06       0  695.77      .1       0
Bank Sta=401.99,540.12
XS Rating Curve= 0 ,0
Exp/Cntr(USF)=0,0
Exp/Cntr=0.3,0.1

Type RM Length L Ch R = 1 ,21098   ,540.2,540.2,540.2
XS GIS Cut Line= 2
2225664.04313321 696990.051350982226064.02596058696102.608245154
#Sta/Elev= 30
       0 1906.45    27.3 1902.93    43.1 1899.04   128.2 1871.41   167.7 1864.38
   185.3  1863.3   197.3 1859.18   233.6 1852.94   286.1 1847.19   325.6 1845.13
   369.7 1843.92   430.2 1845.28   452.9 1842.75   472.6 1836.69  497.491833.114
   509.9 1828.39   518.7 1826.97     602 1826.99   606.4 1828.99  610.331833.116
   626.8 1846.42   632.5 1848.46   667.9 1849.73   707.3 1854.59   795.1 1869.01
   830.2 1876.08   847.7 1877.45   869.7 1881.32   925.1 1893.77   973.4 1911.96
#Mann= 5 ,-1,0
       0      .1       0  497.49    .045       0  610.33      .1       0
     660     .07       0     680      .1       0
Bank Sta=497.49,610.33
XS Rating Curve= 0 ,0
Exp/Cntr(USF)=0,0
Exp/Cntr=0.3,0.1

Type RM Length L Ch R = 1 ,20558   ,363.4,363.4,363.4
XS GIS Cut Line= 3
2226095.10681935697179.3082981682226511.03679395696455.943002772
2226653.75965994696410.584280792
#Sta/Elev= 30
       0 1887.05    52.1 1876.15   168.6 1858.36   270.1 1848.94   297.8 1847.89
  332.891832.734     348 1827.92   376.2 1826.84   436.2 1826.85   444.7 1829.17
  449.371832.735   465.2 1841.92   477.7 1843.37   500.4 1843.38   547.8 1837.89
   573.6 1839.47     612 1838.93   634.6 1846.59   649.8 1848.34   662.3 1853.67
   676.1 1852.87     713 1855.86   731.5 1865.83   749.9  1867.3   775.8 1874.99
   822.6 1877.28     833 1880.64   856.6 1896.03   890.2 1911.04   984.2 1946.11
#Mann= 5 ,-1,0
       0      .1       0  332.89    .045       0  449.37      .1       0
     670     .06       0     820      .1       0
Bank Sta=332.89,449.37
XS Rating Curve= 0 ,0
Exp/Cntr(USF)=0,0
Exp/Cntr=0.3,0.1

Type RM Length L Ch R = 1 ,20195   ,243.2,243.2,243.2
XS GIS Cut Line= 3
2226164.30452741697331.8036755682226710.27984332696874.147896051
2226798.59937972696764.417562951
#Sta/Elev= 30
       0 1898.67    30.2 1893.26    98.3 1877.72   161.6 1861.08   183.5  1860.4
   198.2  1857.2   239.9 1853.39   380.8 1846.26   504.3 1846.34   521.8 1843.69
   532.2 1838.98   541.2  1837.5  549.54 1832.21   553.1 1828.74   558.3 1826.63
   657.9 1826.62   664.1 1827.25   673.1 1832.17   691.7 1843.87   718.8 1847.17
   734.2 1854.16   747.3 1856.07   754.7 1862.79   759.9 1865.71   782.7 1867.24
   791.3 1874.15   805.5 1890.36     843 1917.96   848.2 1920.73   853.3 1921.65
#Mann= 3 ,0,0
       0      .1       0  549.54    .045       0   673.1      .1       0
Bank Sta=549.54,673.1
XS Rating Curve= 0 ,0
Exp/Cntr(USF)=0,0
Exp/Cntr=0.3,0.1

Type RM Length L Ch R = 1 ,19951   ,502.8,502.8,502.8
XS GIS Cut Line= 2
2226284.12181712697509.5739243162227018.67217574696950.788235178
#Sta/Elev= 30
       0 1899.25    80.2 1877.08     191 1854.75   391.4 1844.41   459.9  1845.9
   502.7 1845.35     516 1844.01   532.8 1840.15   547.9 1835.19  552.021832.407
   562.6 1827.49     568  1826.5     674 1826.52   678.6 1827.53  684.771832.409
   713.9 1853.11   718.8 1855.09     734  1857.6   753.9 1874.05   759.6 1876.02
   779.1 1876.31   784.1 1879.07     791  1885.3   799.2 1898.28   802.4 1901.75
   829.3  1922.7   842.4 1926.91   850.9 1932.85     886 1952.33   922.9 1976.38
#Mann= 4 ,-1,0
       0      .1       0  552.02    .045       0  684.77     .06       0
     910      .1       0
Bank Sta=552.02,684.77
XS Rating Curve= 0 ,0
Exp/Cntr(USF)=0,0
Exp/Cntr=0.3,0.1

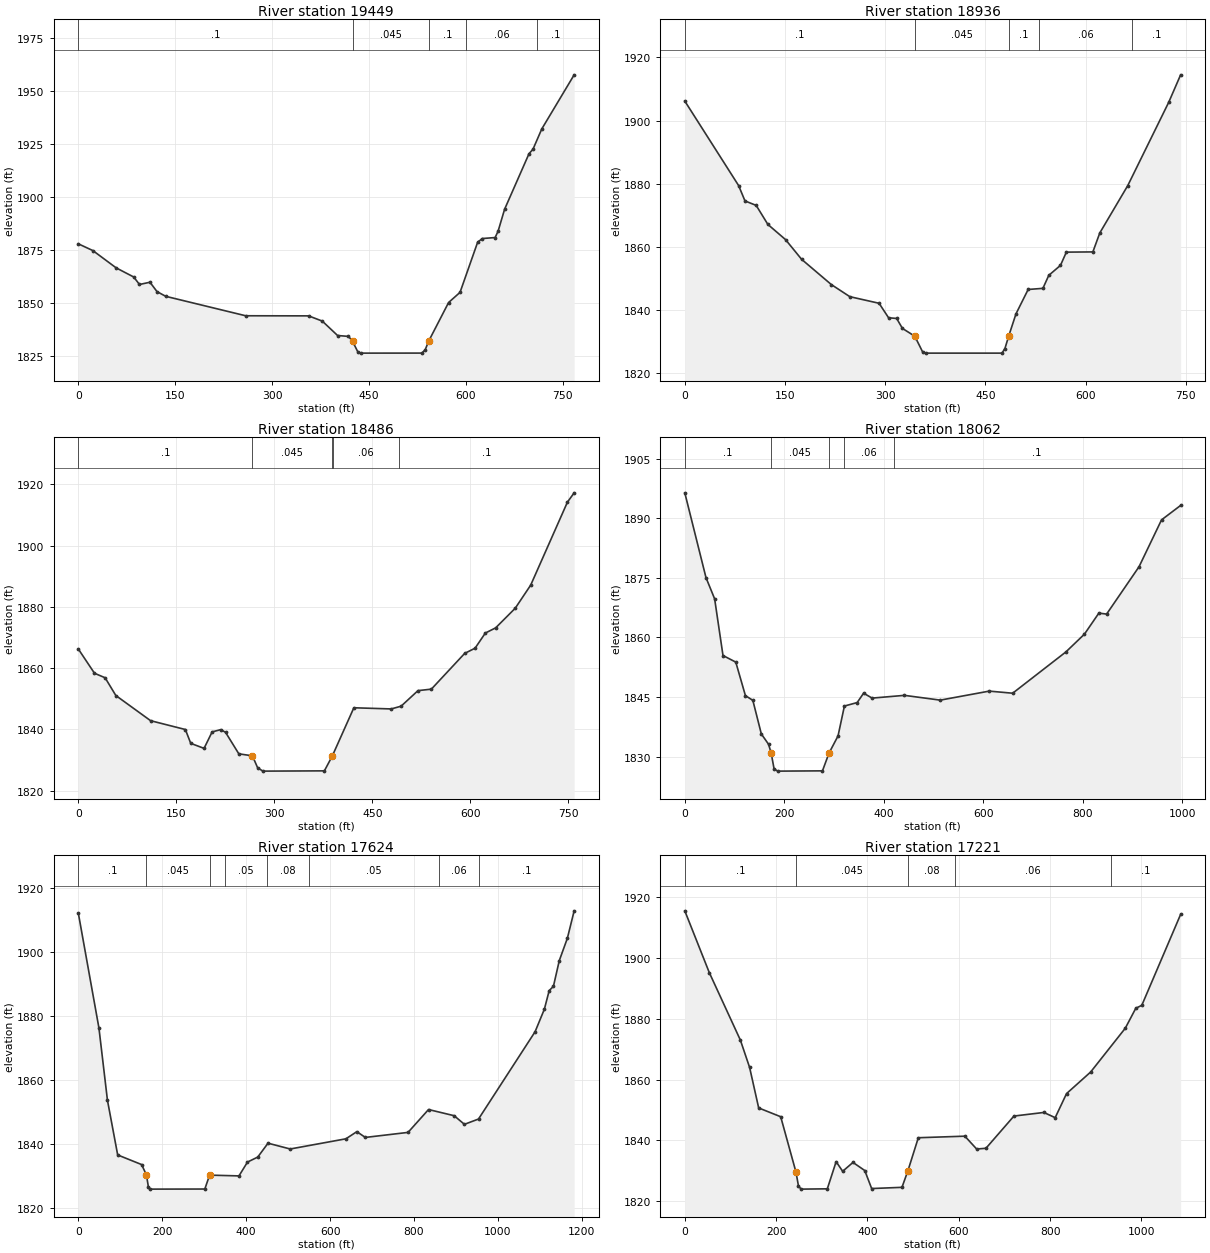
Type RM Length L Ch R = 1 ,19449   ,512.5,512.5,512.5
XS GIS Cut Line= 2
2226588.27042826 697798.980648632227268.63828025697443.272673487
#Sta/Elev= 30
       0 1878.01    22.5 1874.83    58.6 1866.67    85.7 1862.38    94.7 1858.84
   110.9  1859.9   121.8 1855.49   135.3 1853.26   259.1 1844.09   356.5 1844.04
   377.7 1841.58   401.4 1834.78   418.3 1834.36  424.511832.098   433.2 1826.79
   437.7 1826.47   531.8 1826.49     537 1828.01  542.411832.097   573.3 1850.34
     591 1855.13   618.3  1878.8   625.5 1880.51   645.3 1880.97   649.9 1883.94
     660 1894.32   697.8 1920.51     704 1922.65   717.6 1932.21   767.7 1957.71
#Mann= 5 ,-1,0
       0      .1       0  424.51    .045       0  542.41      .1       0
     600     .06       0     710      .1       0
Bank Sta=424.51,542.41
XS Rating Curve= 0 ,0
Exp/Cntr(USF)=0,0
Exp/Cntr=0.3,0.1

Type RM Length L Ch R = 1 ,18936   ,449.8,449.8,449.8
XS GIS Cut Line= 2
2226830.60143365698218.6890746242227508.37555322697915.836469329
#Sta/Elev= 30
       0 1906.18    80.6 1879.44    90.1 1874.59   106.9 1873.17   124.4 1867.15
   150.8 1862.36   174.9 1856.12   219.4 1848.13   247.1  1844.3   290.9 1842.21
   305.1 1837.63   317.2 1837.41   325.9 1834.25  344.381831.792   356.5 1826.65
     361 1826.44   474.9 1826.44   479.3 1827.88  484.931831.794   495.9 1838.87
   514.1 1846.58   536.2 1846.93     545 1851.05   562.5  1854.2   571.3 1858.39
     611 1858.46   621.4 1864.47   663.3 1879.46   724.6  1905.8   742.4 1914.48
#Mann= 5 ,-1,0
       0      .1       0  344.38    .045       0  484.93      .1       0
     530     .06       0     670      .1       0
Bank Sta=344.38,484.93
XS Rating Curve= 0 ,0
Exp/Cntr(USF)=0,0
Exp/Cntr=0.3,0.1

Type RM Length L Ch R = 1 ,18486   ,423.9,423.9,423.9
XS GIS Cut Line= 3
2227036.06300225698539.8139298912227569.92030682698424.902434246
2227731.33243249698286.473826132
#Sta/Elev= 30
       0 1866.27    24.7 1858.36      41 1856.88    57.4 1851.09   110.6 1842.87
   163.8 1839.99     172 1835.48   192.4 1833.84   204.7 1839.21   217.8 1839.95
   225.2  1839.1   245.6 1832.05  266.391831.413   274.3 1827.53   282.4 1826.41
   376.5  1826.5  388.751831.411   421.6 1847.09   478.8 1846.71   493.9 1847.61
   519.7 1852.68   540.2 1853.17   591.2 1864.84   607.1 1866.54   622.8 1871.48
   638.6 1873.18   668.5 1879.57   692.2 1887.13   748.4 1914.21   758.7 1917.25
#Mann= 5 ,-1,0
       0      .1       0  266.39    .045       0  388.75      .1       0
     390     .06       0     490      .1       0
Bank Sta=266.39,388.75
XS Rating Curve= 0 ,0
Exp/Cntr(USF)=0,0
Exp/Cntr=0.3,0.1

Type RM Length L Ch R = 1 ,18062   ,438.6,438.6,438.6
XS GIS Cut Line= 3
2227120.38975485698978.7948724962227869.10189108698692.756103921
2227957.90196696698518.743571699
#Sta/Elev= 30
       0 1896.37    42.6 1875.03      60 1869.68    76.8 1855.42   102.5 1853.76
   121.9 1845.32   136.8 1844.14   153.9 1835.67   168.4 1833.08  173.66 1830.86
   179.6 1826.83     187 1826.32   276.8 1826.39  289.981830.859   308.1 1835.18
   320.9  1842.7   346.6 1843.58   359.5 1845.94   376.6  1844.7   441.6 1845.39
   513.6 1844.19   612.1 1846.46   659.2 1845.93   766.4 1856.34   803.5  1860.8
   832.5 1866.09   848.1 1865.85   913.3 1877.77   958.5 1889.56   996.9  1893.2
#Mann= 5 ,-1,0
       0      .1       0  173.66    .045       0  289.98      .1       0
     320     .06       0     420      .1       0
Bank Sta=173.66,289.98
XS Rating Curve= 0 ,0
Exp/Cntr(USF)=0,0
Exp/Cntr=0.3,0.1

Type RM Length L Ch R = 1 ,17624   ,403.1,403.1,403.1
XS GIS Cut Line= 3
2227263.96096972 699346.152556252228201.17778564699168.940405566
2228327.53158799699358.655359367
#Sta/Elev= 30
       0 1912.05    49.1 1876.22    69.4 1853.65    93.8 1836.58   150.8 1833.58
   162.31830.337   167.1 1826.52   171.2 1825.91   301.5 1825.94  312.851830.278
   382.9 1830.04   403.2 1834.36   427.7 1835.92   452.1 1840.25     505 1838.44
   637.8 1841.62   663.8 1843.85   684.1 1842.05   785.9 1843.62   834.7 1850.76
   895.8 1848.83   920.2 1846.14   953.8 1847.79  1088.7 1875.05  1110.8 1882.08
  1122.3 1887.89  1132.4 1889.22  1146.3 1897.23  1165.6 1904.22  1181.8 1912.79
#Mann= 8 ,-1,0
       0      .1       0   162.3    .045       0  312.85      .1       0
     350     .05       0     450     .08       0     550     .05       0
     860     .06       0  953.82      .1       0
Bank Sta=162.3,312.85
XS Rating Curve= 0 ,0
Exp/Cntr(USF)=0,0
Exp/Cntr=0.3,0.1

Type RM Length L Ch R = 1 ,17221   ,102.4,102.4,102.4
XS GIS Cut Line= 4
2227306.67692772699774.0221537732227478.89106145699763.122525056
2227956.29479924699383.8154457162228250.58477459 699457.93292099
#Sta/Elev= 30
       0 1915.33    53.6 1895.08   121.7 1872.93   141.9 1863.97   161.8 1850.67
     210 1847.79  243.53 1829.59   248.9 1825.09   254.6 1824.04   312.1 1824.14
   331.4 1833.05   345.7 1829.89   368.3  1832.8   394.1 1830.14   409.2 1824.23
   475.6 1824.63  488.721830.126   511.4  1840.9   613.3 1841.41   639.1  1837.2
   659.5 1837.44   720.8 1848.01   786.3 1849.19   811.1 1847.48     836 1855.38
   888.8 1862.46   964.6 1876.82   987.6 1883.36  1000.8 1884.34  1085.8 1914.16
#Mann= 5 ,-1,0
       0      .1       0  243.53    .045       0  488.72     .08       0
  592.56     .06       0   932.3      .1       0
Bank Sta=243.53,488.72
XS Rating Curve= 0 ,0
Exp/Cntr(USF)=0,0
Exp/Cntr=0.3,0.1

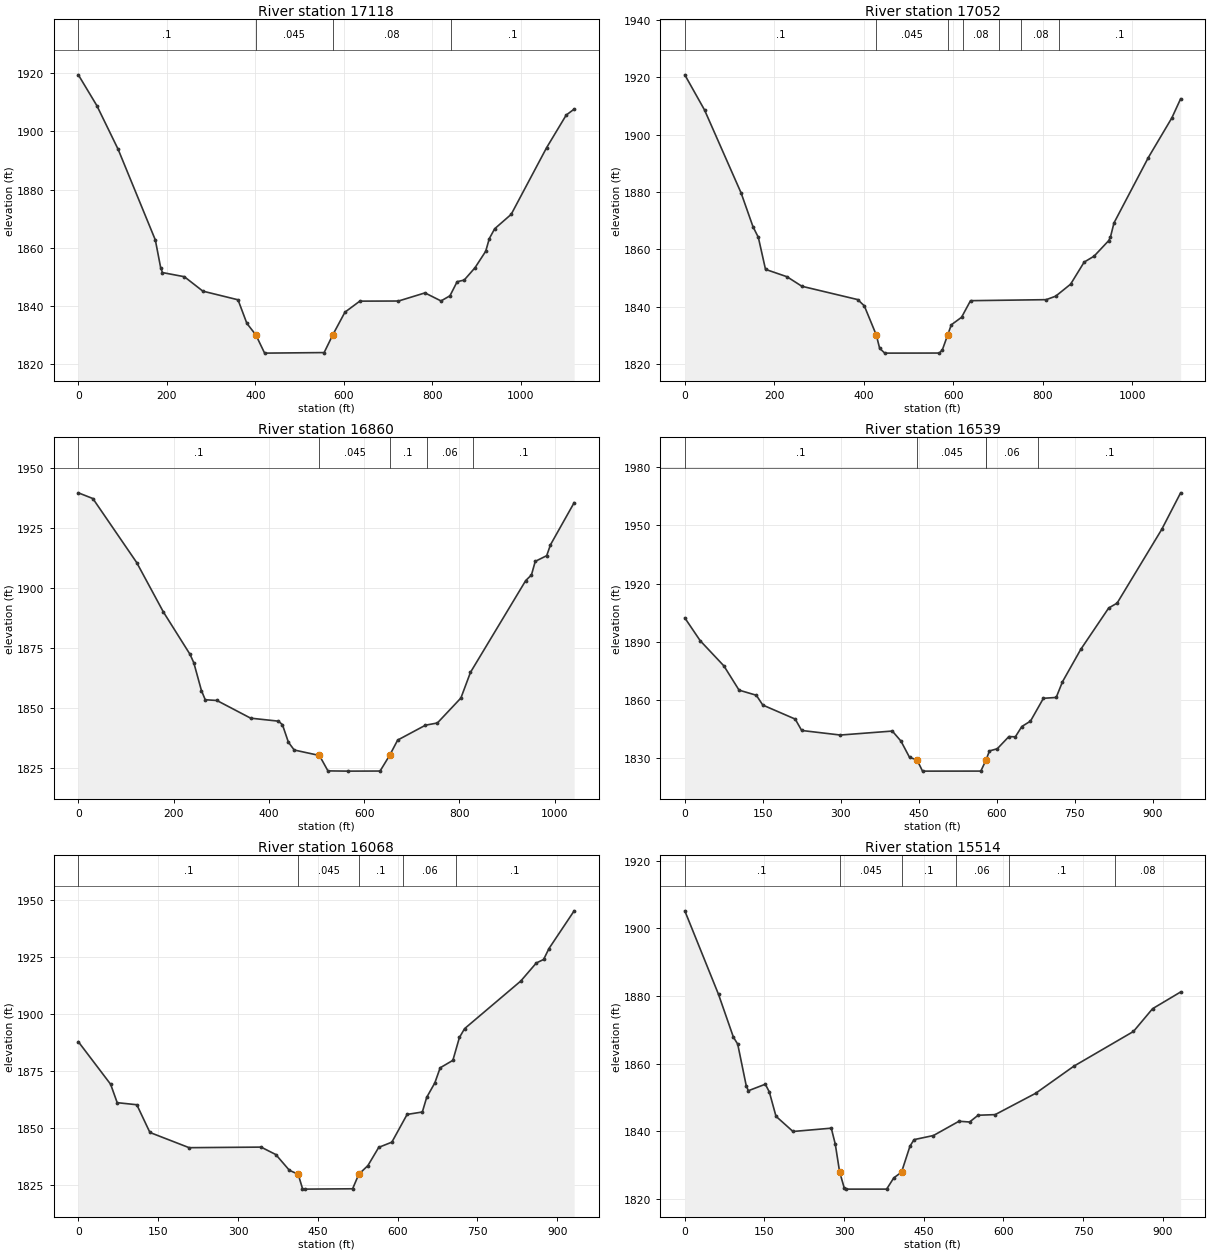
Type RM Length L Ch R = 1 ,17118   ,66.4,66.4,66.4
XS GIS Cut Line= 4
2227278.31418637699939.3871243052227504.28460533699949.550836218
2227811.03536289699535.3327606262228186.00696704699588.094258893
#Sta/Elev= 30
       0 1919.44    41.8 1908.87      90 1893.83     174  1862.7     186 1853.23
   190.1 1851.51   239.5 1850.09   281.4 1845.13   360.8 1842.16   380.8 1834.06
  401.021830.114   420.9 1823.84   555.4 1824.03   574.91830.113   602.4 1837.91
     636  1841.7   723.4 1841.74   783.2 1844.53   819.5 1841.77   839.7 1843.54
   855.9 1848.38   871.8 1848.93   896.3 1853.18   920.5 1858.85   928.6  1863.2
   940.7 1866.56     978 1871.51  1057.9 1894.37  1102.3 1905.61  1120.3 1907.66
#Mann= 4 ,-1,0
       0      .1       0  401.02    .045       0   574.9     .08       0
  841.63      .1       0
Bank Sta=401.02,574.9
XS Rating Curve= 0 ,0
Exp/Cntr(USF)=0,0
Exp/Cntr=0.3,0.1

Type RM Length L Ch R = 1 ,17052   ,191.9,191.9,191.9
XS GIS Cut Line= 4
2227284.10178854699992.748860163 2227545.4130447700005.366266038
2227852.16380226699591.1481904462228179.63682781699636.958677211
#Sta/Elev= 30
       0 1920.92    44.1 1908.64   125.9 1879.62   152.3 1867.89   164.3 1864.15
   180.3 1852.98   228.3  1850.4   261.6 1847.07   386.3 1842.42     401 1840.24
   427.71830.093   435.3 1825.42   446.7 1823.72   568.7 1823.75   575.4 1824.87
  587.341830.092   595.4 1833.61   618.3 1836.24   638.3 1842.04   807.2 1842.39
   828.5  1843.6   861.9  1847.8   892.2 1855.51   914.4 1857.59   946.7 1862.96
   950.7 1864.11   958.8 1869.19  1035.6 1892.04  1088.1 1905.88  1107.7 1912.55
#Mann= 7 ,-1,0
       0      .1       0   427.7    .045       0  587.34     .07       0
  621.62     .08       0  701.62     .07       0  751.62     .08       0
  837.05      .1       0
Bank Sta=427.7,587.34
XS Rating Curve= 0 ,0
Exp/Cntr(USF)=0,0
Exp/Cntr=0.3,0.1

Type RM Length L Ch R = 1 ,16860   ,320.5,320.5,320.5
XS GIS Cut Line= 4
2227197.68064056700061.7723518932227478.89106145700061.772351893
2227965.01450221699917.8972528332228217.88588844699924.437030063
#Sta/Elev= 30
       0 1939.58    30.5  1937.2   122.5 1910.51   178.5 1889.91   234.5 1872.22
   242.5 1868.68   258.5 1857.09   266.5 1853.27   290.9 1852.97   361.8 1845.59
   420.2 1844.34   428.6 1842.85   441.1 1835.55   453.3 1832.31  506.231830.027
   524.1  1823.6   566.6  1823.5   633.6 1823.54   653.51830.027   670.5 1836.45
   728.9 1842.66   753.9 1843.58   803.3    1854   823.4 1864.71   939.4 1902.99
   951.4 1905.31   959.4 1910.99   983.4 1913.36   991.4 1917.92  1041.1 1935.48
#Mann= 5 ,-1,0
       0      .1       0  506.23    .045       0   653.5      .1       0
  731.21     .06       0  828.18      .1       0
Bank Sta=506.23,653.5
XS Rating Curve= 0 ,0
Exp/Cntr(USF)=0,0
Exp/Cntr=0.3,0.1

Type RM Length L Ch R = 1 ,16539   ,472,472,472
XS GIS Cut Line= 3
2227351.60581403700425.3453872822228029.14844976  700236.0876317
2228277.15913943700201.036875489
#Sta/Elev= 30
       0 1902.31    29.7 1890.51    75.3 1877.52   104.4 1865.04   137.6 1862.41
   150.1 1857.34   212.4 1850.12   224.9 1844.24   299.3 1841.89   399.3 1843.94
   415.9 1838.77   432.5 1830.34   446.7 1829.12   457.4 1823.28   569.6  1823.3
  579.361828.887   586.2  1833.7   601.2 1834.81   623.6 1841.11     636 1840.97
   648.5 1846.29   665.1 1849.06     690 1860.83   714.6 1861.27   726.7 1869.37
   761.8 1886.04   815.6 1907.39   831.8 1909.91   917.6 1947.91     954 1966.78
#Mann= 5 ,-1,0
       0      .1       0   446.7    .045       0  579.36      .1       0
     580     .06       0     680      .1       0
Bank Sta=446.7,579.36
XS Rating Curve= 0 ,0
Exp/Cntr(USF)=0,0
Exp/Cntr=0.3,0.1

Type RM Length L Ch R = 1 ,16068   ,553.5,553.5,553.5
XS GIS Cut Line= 3
2227508.85702725 700844.113219762228209.00976429700689.910658518
 2228382.4450543700563.309789389
#Sta/Elev= 30
       0 1887.74    60.7  1869.1      73 1861.05   109.9 1860.14   134.5    1848
   208.2 1841.34   343.4 1841.59   371.1 1838.33   396.6 1831.43   413.11829.702
   421.2 1823.46   425.3 1823.19   515.4 1823.34  527.011829.704   544.1 1833.49
   564.5 1841.48   589.1 1843.75   617.8  1855.9   646.4 1856.96   654.6 1863.37
   669.9 1869.71   679.9 1876.31   703.8 1879.58   716.1 1889.59   725.8 1893.46
   831.4 1914.31   860.6 1922.22   874.3 1923.75   884.3 1928.51   931.7 1945.05
#Mann= 5 ,-1,0
       0      .1       0   413.1    .045       0  527.01      .1       0
     610     .06       0     710      .1       0
Bank Sta=413.1,527.01
XS Rating Curve= 0 ,0
Exp/Cntr(USF)=0,0
Exp/Cntr=0.3,0.1

Type RM Length L Ch R = 1 ,15514   ,456.7,456.7,456.7
XS GIS Cut Line= 2
2227592.77385006701305.3884343172228524.83259019701253.859489415
#Sta/Elev= 30
       0 1905.22    63.5 1880.47    91.5 1867.81    99.6 1865.76   115.6 1853.48
   119.6 1851.94   151.6 1853.88   159.1  1851.6   171.7 1844.38   203.7 1839.88
   275.8 1840.86   283.3 1836.14   291.41827.989   299.9 1823.29   303.9 1822.81
     380 1822.81   393.5 1826.15     408 1827.82     424 1835.56   431.7 1837.47
   468.1 1838.68   516.2 1842.91   536.2 1842.69   552.2 1844.69   584.3 1844.87
   660.7  1851.2   732.5 1859.22   844.7  1869.5   880.7 1876.24   933.5 1881.19
#Mann= 6 ,-1,0
       0      .1       0   291.4    .045       0     408      .1       0
     510     .06       0     610      .1       0     810     .08       0
Bank Sta=291.4,408
XS Rating Curve= 0 ,0
Exp/Cntr(USF)=0,0
Exp/Cntr=0.3,0.1