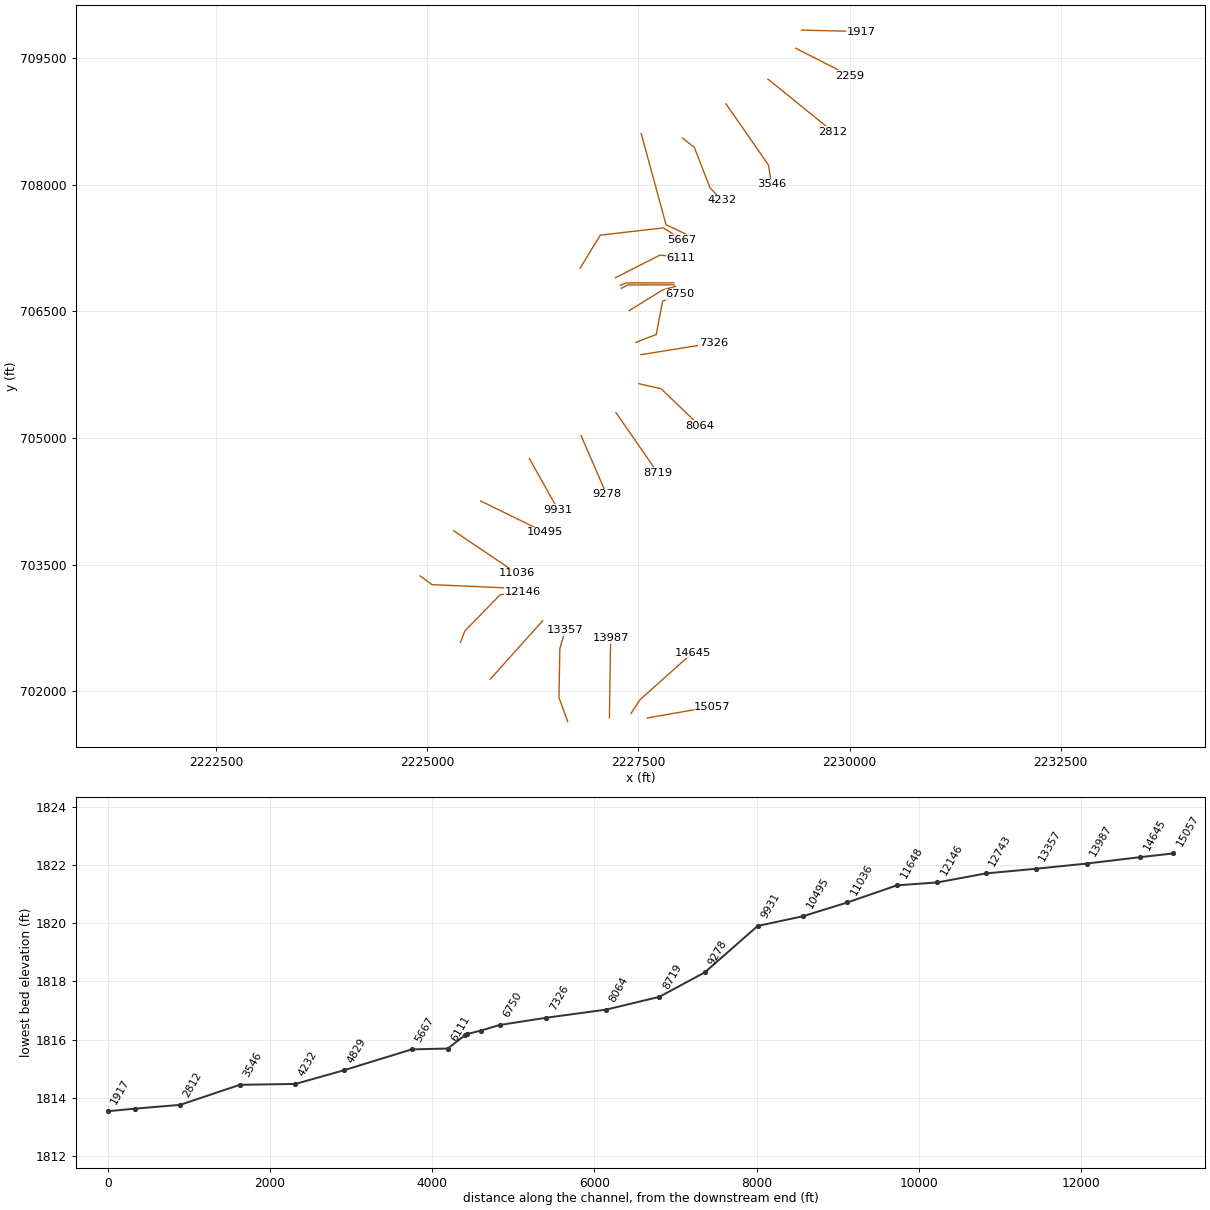
HEC-RAS study MIDFKRIV.prj: MIDFKRIV

--- MIDFKRIV.g01 (geometry) --- (continued)

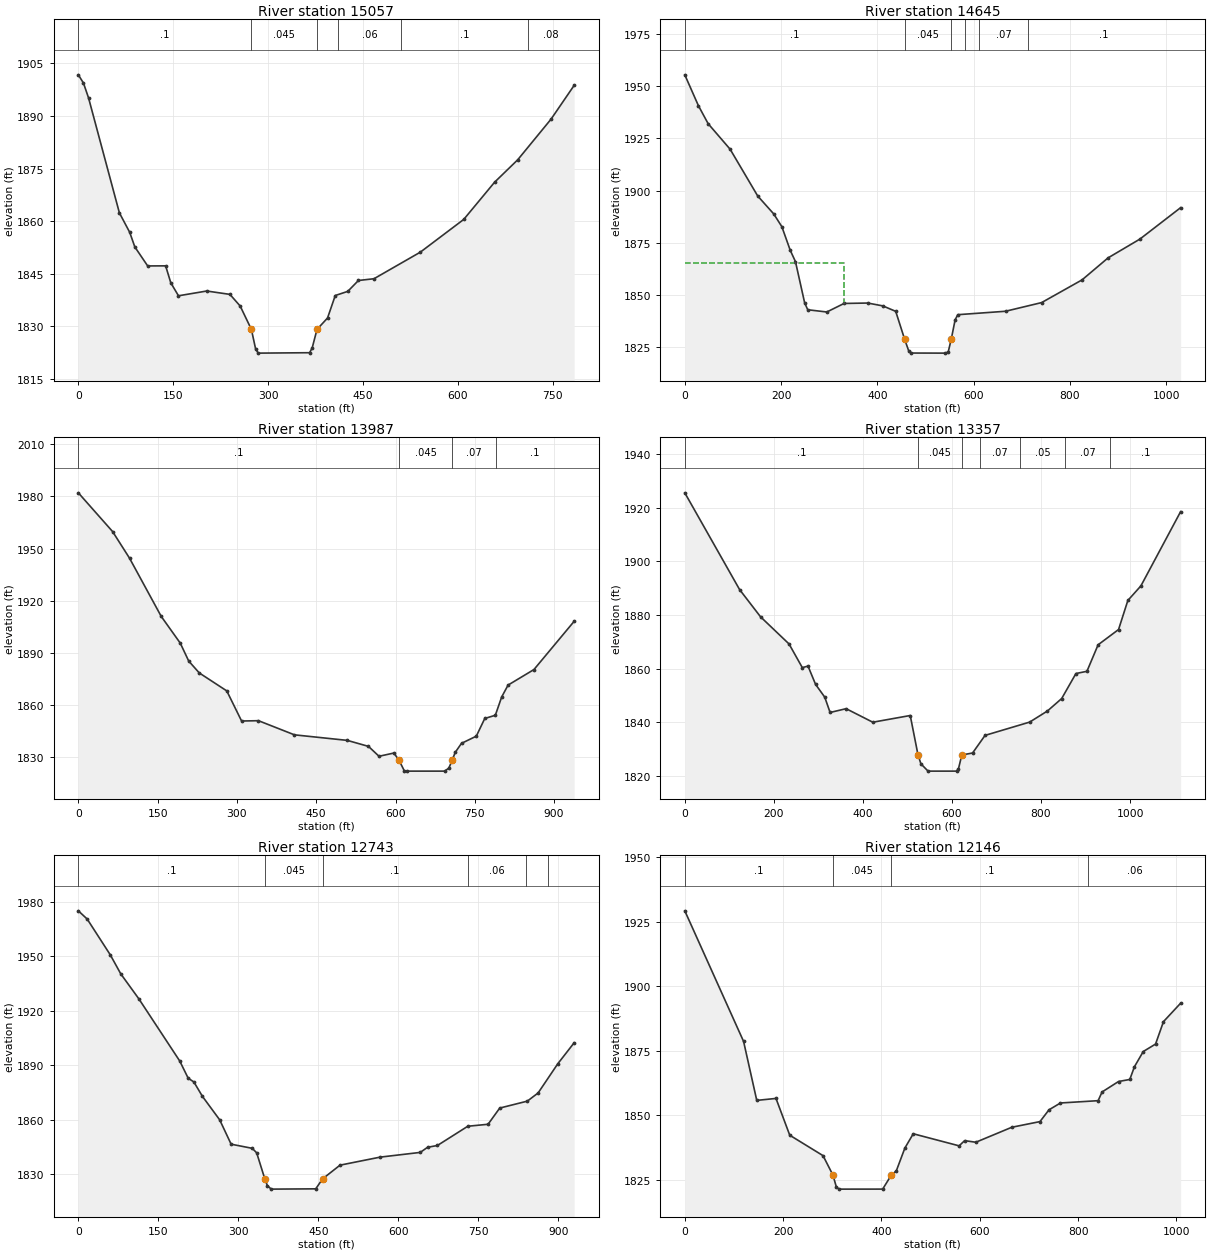
Type RM Length L Ch R = 1 ,15057   ,412.5,412.5,412.5
XS GIS Cut Line= 2
2227604.23171155701683.7316768332228376.01470915701819.816328096
#Sta/Elev= 30
       0 1901.72     8.1 1899.38    16.2 1895.11    64.9 1862.38    81.2 1856.84
    89.3 1852.67   109.6 1847.26     138 1847.28   146.2 1842.42   158.3 1838.75
     203 1840.11   239.6 1839.15   255.8 1835.83  273.53 1829.17   280.2 1823.62
   284.3 1822.41   365.5 1822.53   369.6 1823.87  377.261829.171   393.9 1832.42
   406.1 1838.83   425.9 1840.01   442.7 1843.11   467.3 1843.61   540.6 1851.19
   609.2 1860.52   657.9 1871.11   694.5 1877.51   747.3 1889.12   783.7 1898.72
#Mann= 6 ,-1,0
       0      .1       0  273.53    .045       0  377.26      .1       0
     410     .06       0     510      .1       0     710     .08       0
Bank Sta=273.53,377.26
XS Rating Curve= 0 ,0
Exp/Cntr(USF)=0,0
Exp/Cntr=0.3,0.1

Type RM Length L Ch R = 1 ,14645   ,658,658,658
XS GIS Cut Line= 3
 2227412.1576653701738.1157932082227516.66285203 701899.16816138
2228141.35523116 702457.57783679
#Sta/Elev= 30
       0 1955.36    28.3 1940.59    48.5 1931.99    94.2 1919.77   151.5  1897.4
   184.8 1888.83   201.6 1882.74     219 1871.46   229.9 1866.02     249 1846.28
   255.4 1843.02     295 1841.95   330.8 1846.03     380 1846.23   411.3 1844.87
   438.1 1842.26   456.61828.917     465 1823.43   470.3 1822.32   541.5 1822.28
   547.2 1822.87  553.431828.912   561.5 1838.19     567 1840.66   666.2  1842.3
   741.2 1846.45   825.2 1857.31   879.2 1867.83   945.3 1876.81  1029.9 1891.84
#Mann= 6 ,-1,0
       0      .1       0   456.6    .045       0  553.43      .1       0
  581.99     .06       0  611.99     .07       0  711.99      .1       0
#XS Ineff= 2 , 0
          329.68 1865.55
Permanent Ineff=
       F       F
Bank Sta=456.6,553.43
XS Rating Curve= 0 ,0
Exp/Cntr(USF)=0,0
Exp/Cntr=0.3,0.1

Type RM Length L Ch R = 1 ,13987   ,629.5,629.5,629.5
XS GIS Cut Line= 2
2227155.57617492701688.4298626272227170.37960025 702626.18073991
#Sta/Elev= 30
       0 1982.11    64.8 1959.84    96.8 1944.55   156.8 1911.04   192.8 1895.68
   208.8 1885.37   228.8 1878.52   280.8  1868.2   308.8 1850.88   340.8 1851.06
   408.8 1842.93   508.8 1839.74   548.8 1836.29   568.8  1830.6   596.8 1832.46
  606.32 1828.49   616.8 1822.12   620.8 1822.06   692.8 1822.06   700.8 1823.79
   707.51828.494   712.8  1832.8   724.8 1838.04   752.8 1842.16   768.8 1852.34
   788.8 1854.19   800.8 1864.71   812.9 1871.54   861.9 1880.49   937.9 1908.23
#Mann= 4 ,-1,0
       0      .1       0  606.32    .045       0   707.5     .07       0
     790      .1       0
Bank Sta=606.32,707.5
XS Rating Curve= 0 ,0
Exp/Cntr(USF)=0,0
Exp/Cntr=0.3,0.1

Type RM Length L Ch R = 1 ,13357   ,614.5,614.5,614.5
XS GIS Cut Line= 4
2226662.08718632701641.3328939142226558.02866582701925.796888775
2226568.99343592702508.4960999992226634.66120765702726.644471852
#Sta/Elev= 30
       0  1925.5     123 1889.49   170.2 1879.32   234.1 1869.23   263.9 1860.42
   276.7 1860.99   293.7 1854.18   314.3 1849.42   326.3 1843.72   362.3 1845.13
   422.2 1840.09   506.3 1842.59   523.71827.938   530.3 1824.59   546.3 1821.88
   610.3 1821.88   614.3 1822.55  622.131827.892   646.3 1828.63   674.3 1835.19
   774.4 1840.13   814.4 1844.27   846.4 1848.91   878.4 1858.22   903.1 1859.05
   928.2 1868.92   974.1  1874.6     995 1885.43  1024.3 1890.85  1113.5  1918.5
#Mann= 7 ,-1,0
       0      .1       0   523.7    .045       0  622.13      .1       0
   662.9     .07       0   752.9     .05       0   852.9     .07       0
   955.7      .1       0
Bank Sta=523.7,622.13
XS Rating Curve= 0 ,0
Exp/Cntr(USF)=0,0
Exp/Cntr=0.3,0.1

Type RM Length L Ch R = 1 ,12743   ,597.3,597.3,597.3
XS GIS Cut Line= 2
2225745.12284916702143.8235649952226365.25394419702836.113867624
#Sta/Elev= 30
       0 1975.05    16.6 1970.52    59.8 1950.84    79.6  1940.3   113.6 1926.49
   190.1  1892.3   205.9 1882.84   216.6 1880.75   232.7 1872.79     265 1859.88
   286.4 1846.48     326  1844.2   334.3 1841.72  349.541827.363   354.4 1823.63
   361.6 1821.72     445 1821.88   457.81827.364   490.5 1834.92   565.7 1839.35
   640.9 1841.95   654.6 1844.77   673.1 1845.77     730 1856.36     768 1857.45
   789.9 1866.38   841.6  1870.2   861.9 1874.72   898.6 1890.74   929.4 1902.37
#Mann= 6 ,-1,0
       0      .1       0  349.54    .045       0   457.8      .1       0
     730     .06       0     840     .07       0     880      .1       0
Bank Sta=349.54,457.8
XS Rating Curve= 0 ,0
Exp/Cntr(USF)=0,0
Exp/Cntr=0.3,0.1

Type RM Length L Ch R = 1 ,12146   ,497.8,497.8,497.8
XS GIS Cut Line= 4
2225392.17218533702581.460914694 2225442.7549067 702713.69394051
2225860.98256637703142.8863702822226126.82863319703175.104434687
#Sta/Elev= 30
       0 1929.14   119.6 1878.58   146.4 1855.76   185.5 1856.52   213.5 1842.28
   281.2 1834.37  301.271826.871   308.4 1822.18     314 1821.41   402.5 1821.42
  420.211826.874   430.2 1828.45   447.7 1837.32   464.7 1842.84     558 1838.17
   569.3 1840.18     592 1839.56   665.2 1845.36   722.5 1847.55   740.8 1852.11
   764.2 1854.76   840.8 1855.65   848.8 1859.02   882.3 1863.07   905.2 1863.86
   914.7 1868.81   932.6 1874.68   957.6 1877.56   973.7 1886.24  1008.6 1893.38
#Mann= 4 ,-1,0
       0      .1       0  301.27    .045       0  420.21      .1       0
  820.84     .06       0
Bank Sta=301.27,420.21
XS Rating Curve= 0 ,0
Exp/Cntr(USF)=0,0
Exp/Cntr=0.3,0.1

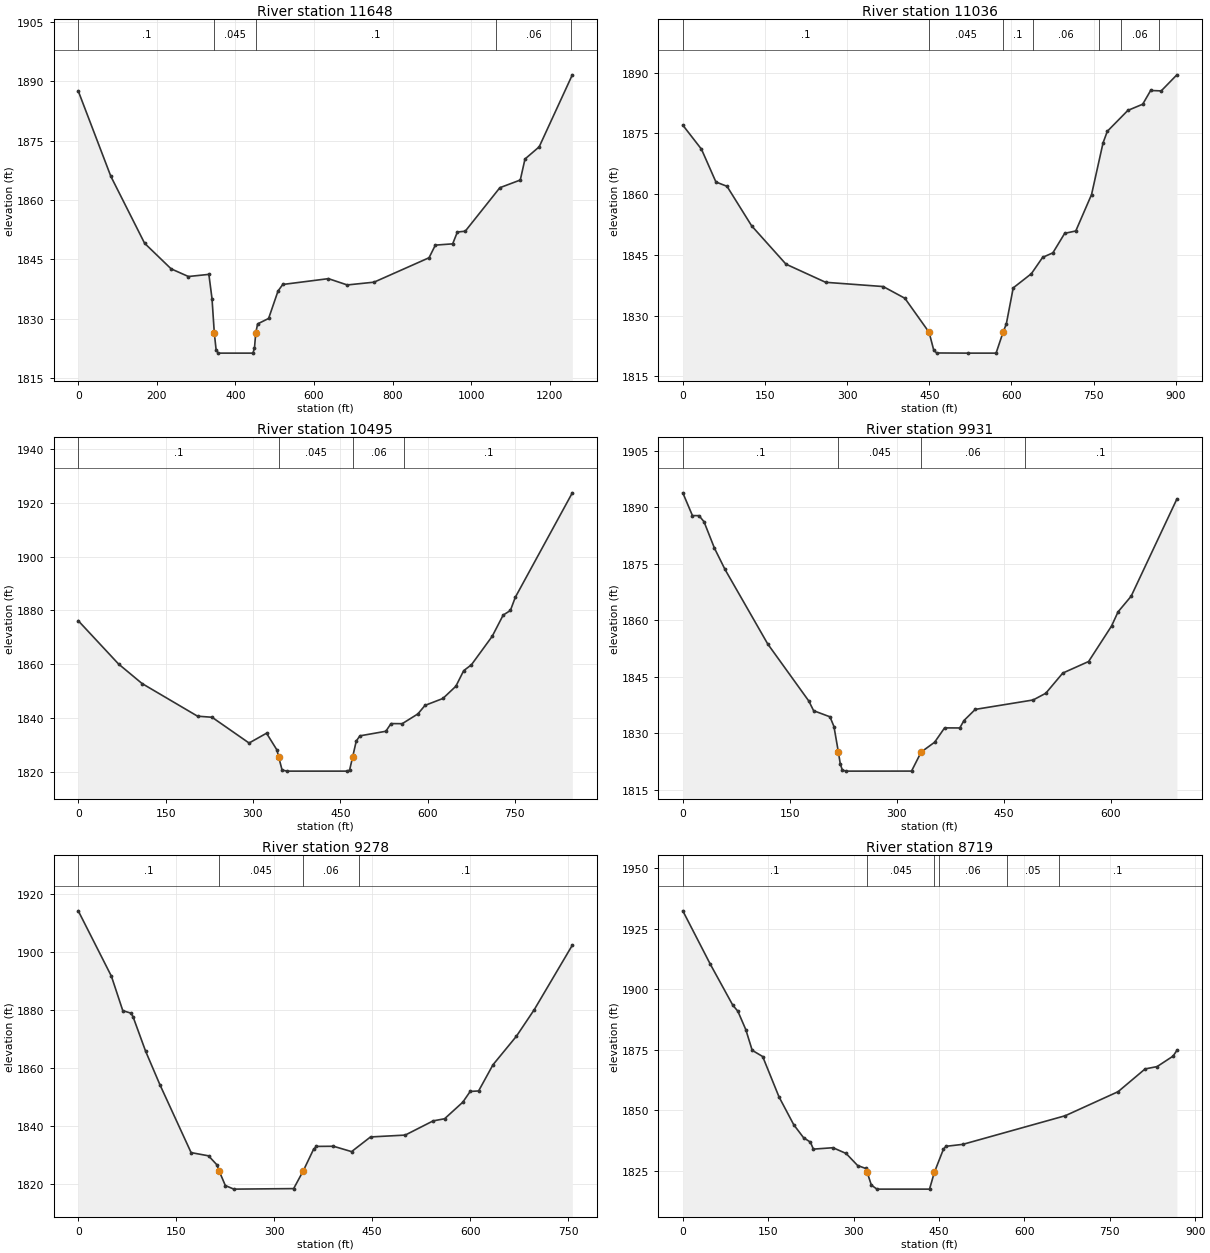
Type RM Length L Ch R = 1 ,11648   ,611.3,611.3,611.3
XS GIS Cut Line= 3
2224913.87561894703366.9833568652225054.28876589703263.498841422
 2226136.5289732703215.940984476
#Sta/Elev= 30
       0 1887.52      83 1865.96   168.9 1849.06   236.4  1842.6   280.4 1840.66
   332.5  1841.2   340.5 1835.08  346.361826.368     351  1822.1   356.5 1821.31
   444.6 1821.31   448.6 1822.56  451.771826.364   456.6 1828.69   484.6 1830.07
   508.6 1837.01   520.6 1838.65   636.8 1840.12   684.7 1838.53   752.9 1839.23
     893  1845.4     909 1848.59   953.1 1848.91   965.1  1851.9   985.1  1852.1
  1073.2 1863.09  1125.2 1865.03  1137.2 1870.34  1173.3 1873.41  1257.7  1891.6
#Mann= 5 ,-1,0
       0      .1       0  346.36    .045       0  451.77      .1       0
 1064.43     .06       0 1254.43      .1       0
Bank Sta=346.36,451.77
XS Rating Curve= 0 ,0
Exp/Cntr(USF)=0,0
Exp/Cntr=0.3,0.1

Type RM Length L Ch R = 1 ,11036   ,541.5,541.5,541.5
XS GIS Cut Line= 2
2225311.91851826703900.8960196662226059.91482397703396.642478396
#Sta/Elev= 30
       0 1877.05    34.1  1871.1    60.5    1863    80.7 1861.94   125.7 1852.17
   188.4  1842.7   260.8 1838.22   365.9 1837.17   405.5 1834.27   449.7 1825.86
   458.1 1821.49   463.4 1820.76   521.3 1820.72     572 1820.72   584.71825.859
   590.7 1827.94   603.3 1836.84   636.4 1840.34     657 1844.38   675.7  1845.5
   697.3 1850.32   717.5  1850.9   746.3  1859.9   767.3 1872.67   775.1 1875.53
   812.6 1880.69   839.7 1882.22   854.2 1885.61   873.5 1885.51   902.1 1889.48
#Mann= 7 ,-1,0
       0      .1       0   449.7    .045       0   584.7      .1       0
     640     .06       0     760      .1       0     800     .06       0
     870      .1       0
Bank Sta=449.7,584.7
XS Rating Curve= 0 ,0
Exp/Cntr(USF)=0,0
Exp/Cntr=0.3,0.1

Type RM Length L Ch R = 1 ,10495   ,564.3,564.3,564.3
XS GIS Cut Line= 2
2225629.79043582704255.3630018912226391.72803082703881.841884419
#Sta/Elev= 30
       0 1876.18    69.2 1860.09   109.6 1852.82   204.9 1840.68   229.8 1840.28
   293.4  1830.7   323.4 1834.35   341.2 1828.13  344.281825.483   350.1 1820.66
   358.7 1820.25   461.5 1820.25     466 1820.59  471.231825.485   477.5 1831.44
   483.8 1833.37   528.3 1835.07   537.2 1837.93   556.4 1837.89   583.3 1841.52
   595.6  1844.7   626.3 1847.26   648.6 1851.82     662  1857.6   675.3  1859.8
     711 1870.39   729.8 1878.27   742.2 1879.98   750.7 1884.91   848.6 1923.73
#Mann= 4 ,-1,0
       0      .1       0  344.28    .045       0  471.23     .06       0
     560      .1       0
Bank Sta=344.28,471.23
XS Rating Curve= 0 ,0
Exp/Cntr(USF)=0,0
Exp/Cntr=0.3,0.1

Type RM Length L Ch R = 1 ,9931    ,652.2,652.2,652.2
XS GIS Cut Line= 2
2226207.56408941 704756.988985532226546.43390963704153.326991251
#Sta/Elev= 30
       0 1893.79    13.5 1887.75    22.7 1887.73    29.7 1886.13    44.4 1879.08
    59.1 1873.47     119 1853.67   176.6 1838.51   183.3 1835.95   206.2 1834.33
   211.8 1831.75  217.981824.989   220.7 1821.79   223.6 1820.17   229.1 1819.91
   320.5 1819.92  334.021824.983   352.9 1827.59   366.8 1831.39   388.1 1831.37
     394 1833.35   409.8  1836.3   490.9  1838.8   508.6 1840.58   532.4 1845.94
   568.6 1849.01   600.7 1858.41   609.9  1862.2   628.2 1866.34   692.3 1892.15
#Mann= 4 ,-1,0
       0      .1       0  217.98    .045       0  334.02     .06       0
     480      .1       0
Bank Sta=217.98,334.02
XS Rating Curve= 0 ,0
Exp/Cntr(USF)=0,0
Exp/Cntr=0.3,0.1

Type RM Length L Ch R = 1 ,9278    ,559.6,559.6,559.6
XS GIS Cut Line= 2
2226820.32660308705027.7586374592227121.26436116704333.739631578
#Sta/Elev= 30
       0 1914.26    50.8  1891.7    68.2 1879.84    80.9 1878.97      84 1877.68
   103.1 1865.89   124.9 1854.38   172.8  1830.9   199.5 1829.79   212.1 1826.74
  215.641824.618   225.2 1819.55   238.2 1818.31   329.8 1818.49  344.53 1824.62
   360.3 1832.05   364.7 1833.04   390.8 1833.09   418.5 1831.24   447.5  1836.3
   500.6 1836.94   543.4 1841.84   560.9 1842.57   588.8 1848.29   600.1 1851.99
     613 1852.16     635 1861.18   670.9 1871.03   698.3 1880.22   756.5 1902.42
#Mann= 4 ,-1,0
       0      .1       0  215.64    .045       0  344.53     .06       0
     430      .1       0
Bank Sta=215.64,344.53
XS Rating Curve= 0 ,0
Exp/Cntr(USF)=0,0
Exp/Cntr=0.3,0.1

Type RM Length L Ch R = 1 ,8719    ,654.6,654.6,654.6
XS GIS Cut Line= 2
2227233.02621835705301.2759634042227727.98141747704588.380390338
#Sta/Elev= 30
       0  1932.4    48.3 1910.36    87.8 1893.44    96.7 1890.95   110.7 1883.32
   121.9  1874.8   140.3 1872.23     169 1855.57   194.9 1844.06   212.1 1838.72
   224.1 1836.88   229.4 1833.99   263.9 1834.57   286.9 1832.19   307.1 1827.22
   321.5 1825.99  323.891824.414   331.2 1819.15     341 1817.47   433.4 1817.47
  441.91 1824.41   457.9 1834.01   462.2 1835.15   491.9 1835.96   671.8 1847.78
   764.6 1857.71   812.1 1867.11   833.1 1868.07   861.2  1872.4   867.9 1874.75
#Mann= 6 ,-1,0
       0      .1       0  323.89    .045       0  441.91      .1       0
     450     .06       0     570     .05       0     660      .1       0
Bank Sta=323.89,441.91
XS Rating Curve= 0 ,0
Exp/Cntr(USF)=0,0
Exp/Cntr=0.3,0.1

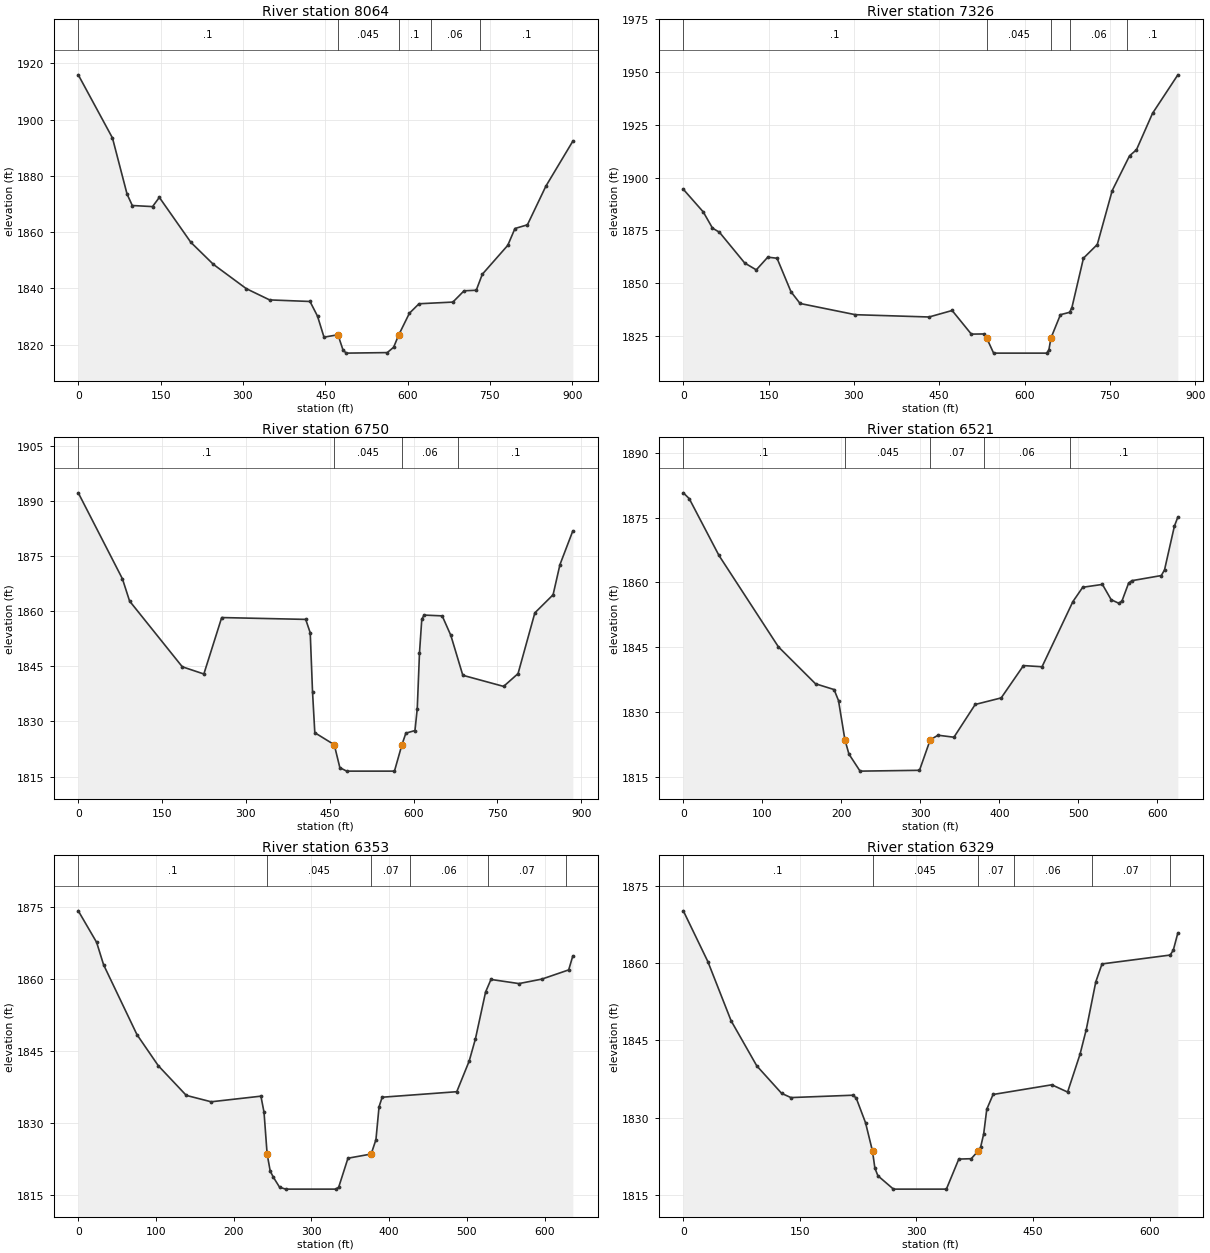
Type RM Length L Ch R = 1 ,8064    ,738.2,738.2,738.2
XS GIS Cut Line= 3
2227504.31625065705643.9973596212227769.17528331705582.771252475
 2228223.1167656705147.156600214
#Sta/Elev= 30
       0 1915.91    62.3 1893.48    88.9 1873.53    98.4 1869.48   135.3 1869.09
   147.7 1872.37   205.1  1856.4   246.2 1848.56   306.2 1839.93   348.6 1835.94
   422.2 1835.38   435.9 1830.16   447.7 1822.71   473.1 1823.55   482.1 1818.29
   487.9 1817.03     563 1817.22   574.6 1819.13  583.791823.484   603.3 1831.21
   620.8 1834.57   682.5 1835.17   702.9 1839.18   725.1 1839.37   736.1 1845.05
   782.5 1855.33   795.6 1861.31   818.3 1862.62   851.9 1876.34     901 1892.33
#Mann= 5 ,-1,0
       0      .1       0   473.1    .045       0  583.79      .1       0
  641.84     .06       0  731.84      .1       0
Bank Sta=473.1,583.79
XS Rating Curve= 0 ,0
Exp/Cntr(USF)=0,0
Exp/Cntr=0.3,0.1

Type RM Length L Ch R = 1 ,7326    ,576,576,576
XS GIS Cut Line= 2
2227529.51673675705987.3712693012228388.05823587706125.527372607
#Sta/Elev= 30
       0 1894.47    35.1 1883.71    51.3 1876.04    63.5 1874.08     108 1859.48
   128.3 1856.24   148.5 1862.27   164.8 1861.75   189.3 1845.87   205.3  1840.3
   302.5 1834.98   432.1 1833.89   472.7 1836.97   506.4 1825.77   529.4 1825.85
  533.52 1823.86   545.6 1816.75   638.8 1816.75   642.8 1818.23  646.351823.859
   663.1 1834.98   679.3 1836.11   683.3 1838.38   703.6 1861.79   727.9 1868.26
   754.2 1893.88   784.6 1910.33   796.8 1913.21   825.1 1930.51   869.6 1948.75
#Mann= 5 ,-1,0
       0      .1       0  533.52    .045       0  646.35     .05       0
     680     .06       0     780      .1       0
Bank Sta=533.52,646.35
XS Rating Curve= 0 ,0
Exp/Cntr(USF)=0,0
Exp/Cntr=0.3,0.1

Type RM Length L Ch R = 1 ,6750    ,228.6,228.6,228.6
XS GIS Cut Line= 4
2227470.47758148706133.4017709252227709.96552475706225.620059696
2227786.09235718706621.7615395842227995.40923181706703.668058182
#Sta/Elev= 30
       0 1892.14      79 1868.77    91.8 1862.73   186.1 1844.86   224.7  1842.9
   256.6 1858.24   406.9 1857.74     415  1854.1   419.1 1838.12   423.2 1826.94
  457.981823.684     468 1817.45   480.2  1816.5   565.7  1816.5   579.11823.682
   586.1 1826.82   602.4 1827.53   606.5  1833.5   610.5 1848.65   614.6 1857.78
   618.7 1858.91   651.1  1858.7   666.6 1853.38     688 1842.55     761 1839.53
   786.8    1843   816.9 1859.52   849.5 1864.43   861.8 1872.63   884.8 1881.78
#Mann= 4 ,-1,0
       0      .1       0  457.98    .045       0   579.1     .06       0
  680.02      .1       0
Bank Sta=457.98,579.1
XS Rating Curve= 0 ,0
Exp/Cntr(USF)=0,0
Exp/Cntr=0.3,0.1

Type RM Length L Ch R = 1 ,6521    ,168.7,168.7,168.7
XS GIS Cut Line= 3
2227389.78135139706509.3030759152227788.97773471706755.631125634
2227940.47761793706796.198425492
#Sta/Elev= 30
       0 1880.73     7.5 1879.38    45.1 1866.24   120.3 1845.09   167.3 1836.53
   190.8 1835.19   196.4 1832.64  204.511823.574   209.6 1820.26   223.7 1816.31
   298.9  1816.5  312.511823.577   322.4 1824.62   342.5 1824.16   369.4 1831.74
   402.3 1833.26   430.5 1840.74     454 1840.47   493.1 1855.57   505.5 1858.87
   530.4 1859.53   541.5 1855.99   551.1 1855.17   555.2 1855.71   563.5  1859.8
   567.5 1860.39   604.9 1861.58     609 1862.88   621.5 1873.01   625.9 1875.14
#Mann= 5 ,-1,0
       0      .1       0  204.51    .045       0  312.51     .07       0
     380     .06       0  489.08      .1       0
Bank Sta=204.51,312.51
XS Rating Curve= 0 ,0
Exp/Cntr(USF)=0,0
Exp/Cntr=0.3,0.1

Type RM Length L Ch R = 1 ,6353    ,24,24,24
XS GIS Cut Line= 3
2227295.38655467706771.7903940632227372.20208916706812.697990411
2227921.46260217706814.702826004
#Sta/Elev= 30
       0 1874.18    23.6 1867.62    32.6 1862.93    75.5 1848.39     103  1841.9
     139 1835.72     171 1834.39     235 1835.56     239 1832.22  242.981823.514
     247 1819.93     251 1818.68     259 1816.59   266.8 1816.19     331 1816.19
     335 1816.56     347 1822.63  376.861823.506     383  1826.5     387 1833.35
     391 1835.34     487 1836.49     503 1842.89     511  1847.5   524.1 1857.28
     531 1859.88     567 1859.02   596.4 1859.95     631 1861.87   636.3 1864.78
#Mann= 6 ,-1,0
       0      .1       0  242.98    .045       0  376.86     .07       0
  427.03     .06       0  527.03     .07       0  627.03      .1       0
Bank Sta=242.98,376.86
XS Rating Curve= 0 ,0
Exp/Cntr(USF)=0,0
Exp/Cntr=0.3,0.1

Type RM Length L Ch R = 1 ,6329    ,217.6,217.6,217.6
XS GIS Cut Line= 3
2227286.61357989706810.1945136992227357.36788517706836.972142384
2227918.08388338706837.598459657
#Sta/Elev= 30
       0 1870.15    31.6 1860.29    61.5 1848.82    94.5 1840.08   126.5 1834.74
   138.5 1833.92   218.5 1834.38   222.5 1833.82   234.5 1829.03  243.471823.507
   246.5 1820.24   250.4 1818.75   270.4 1816.16   338.5 1816.16   354.5 1821.99
   370.5 1822.06  379.091823.507   382.5 1824.25   386.5 1826.85   390.5 1831.66
   398.6 1834.52   474.2  1836.4   494.5 1834.99   510.5 1842.33   518.5  1847.1
   530.8 1856.38   538.8 1859.85   626.5 1861.57   630.5 1862.51   636.4 1865.87
#Mann= 6 ,-1,0
       0      .1       0  243.47    .045       0  379.09     .07       0
  425.65     .06       0  525.65     .07       0  625.65      .1       0
Bank Sta=243.47,379.09
XS Rating Curve= 0 ,0
Exp/Cntr(USF)=0,0
Exp/Cntr=0.3,0.1

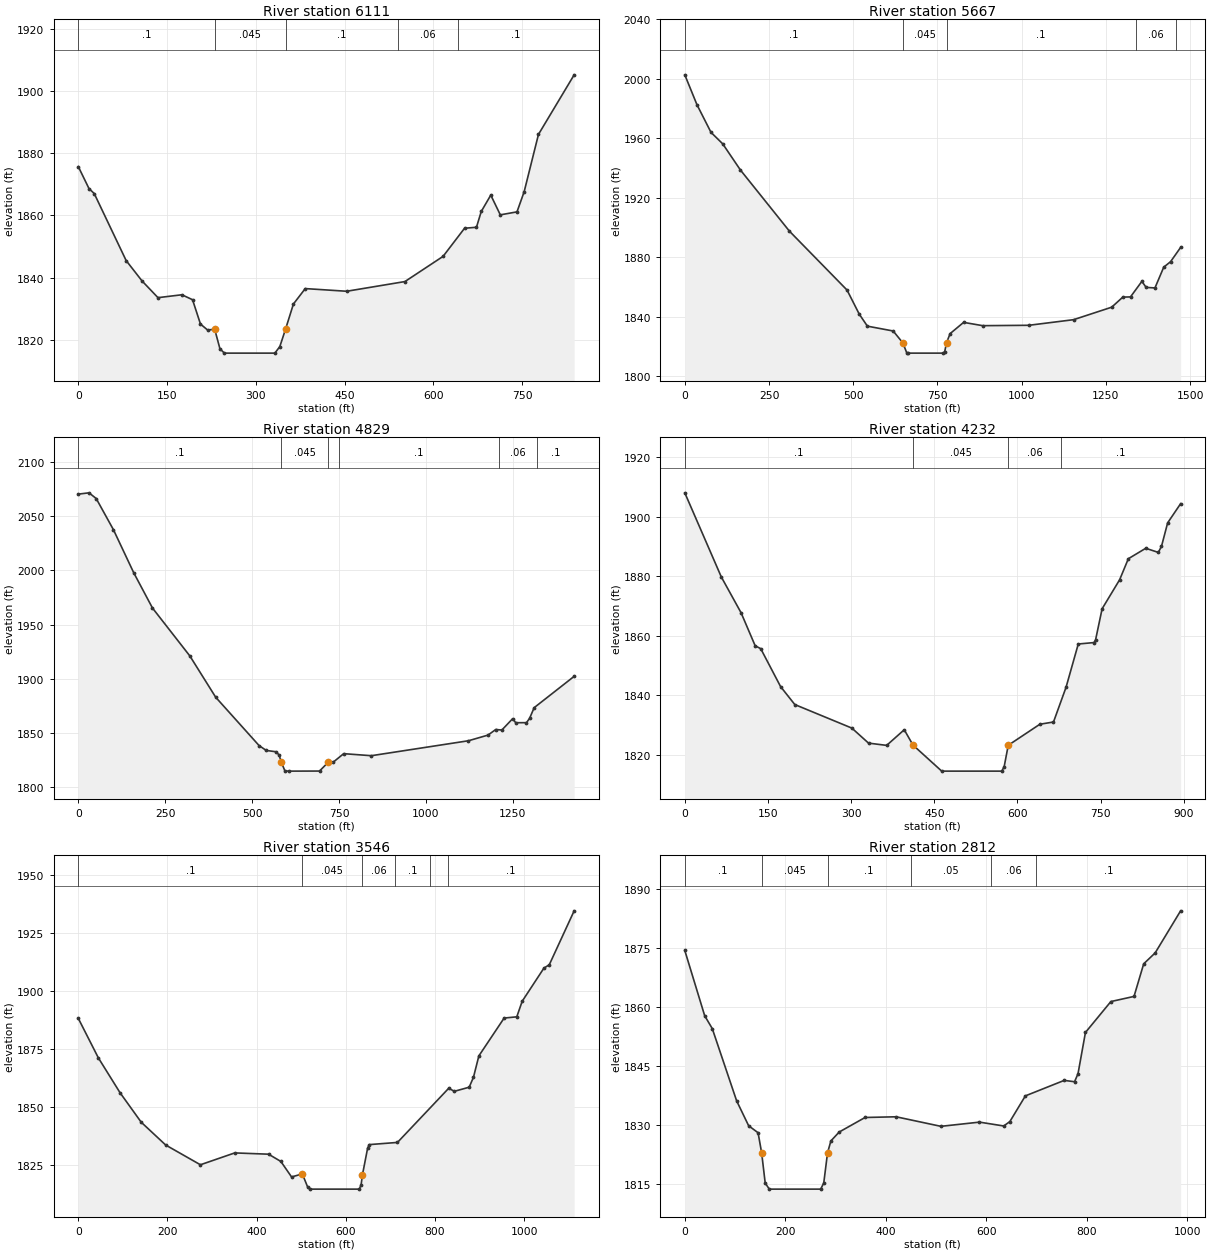
Type RM Length L Ch R = 1 ,6111    ,444.6,444.6,444.6
XS GIS Cut Line= 3
2227228.16026491706899.3842911312227755.14358696707167.279923241
2227999.97998929707136.927569177
#Sta/Elev= 30
       0 1875.69      18 1868.65    26.9 1867.04    80.8 1845.48   107.7 1838.91
   134.6 1833.54     175 1834.47     193 1832.88   206.4 1825.05   218.5 1823.12
   230.4 1823.39   239.3  1817.1   246.8 1815.69   332.1 1815.69   340.5  1817.8
  350.251823.448   363.5 1831.51   383.5 1836.46   453.5  1835.6   551.9 1838.72
   616.4 1846.83   652.7 1855.88   672.8 1856.19   680.9 1861.27     697 1866.54
   713.1 1860.19   741.3 1861.15   753.4 1867.63   777.6 1886.08   837.9 1905.25
#Mann= 5 ,-1,0
       0      .1       0   230.4    .045       0  350.25      .1       0
     540     .06       0  641.17      .1       0
Bank Sta=230.4,350.25
XS Rating Curve= 0 ,0
Exp/Cntr(USF)=0,0
Exp/Cntr=0.3,0.1

Type RM Length L Ch R = 1 ,5667    ,837.9,837.9,837.9
XS GIS Cut Line= 4
2226809.26130083707013.1341176062227047.81326075707403.107989768
 2227794.6193489 707488.983295122228017.68483886707349.694063129
#Sta/Elev= 30
       0 2002.66    36.2 1982.53    77.8    1964   112.6 1956.28   165.1 1938.71
   310.5 1897.64   481.7 1858.02   517.9 1841.84   542.1 1833.78   618.6 1830.53
   647.1  1822.6   658.8 1815.92   662.9 1815.66   767.5 1815.66   771.6 1816.68
   777.1 1822.75   787.7 1828.79   827.7 1836.32   884.3 1834.11  1021.2 1834.36
  1154.1 1838.13  1267.3 1846.53  1300.3  1853.3  1323.1 1853.44  1356.9 1863.89
  1369.5 1859.82  1395.7 1859.47  1421.8 1873.43  1442.1 1877.11  1471.9  1886.7
#Mann= 5 ,-1,0
       0      .1       0   647.1    .045       0   777.1      .1       0
 1338.88     .06       0 1458.88      .1       0
Bank Sta=647.1,777.1
XS Rating Curve= 0 ,0
Exp/Cntr(USF)=0,0
Exp/Cntr=0.3,0.1

Type RM Length L Ch R = 1 ,4829    ,596.9,596.9,596.9
XS GIS Cut Line= 3
2227532.43174357708606.7701440612227826.66257997707526.381485332
2228104.21190632707395.273850386
#Sta/Elev= 30
       0 2070.11    30.7  2071.3    51.4 2066.06   101.1 2037.27   159.2  1997.8
   213.4 1965.16   320.9 1921.03   395.3 1882.99   519.9 1838.54   540.6    1834
   569.6 1832.75   577.9 1829.61   583.71823.484   594.5 1815.08   606.9 1814.94
     694 1815.01   718.71822.991   734.2  1823.4   763.5 1831.02   843.2 1829.15
  1122.6 1842.92  1178.9 1848.15    1201 1853.26  1218.7 1852.81  1249.7 1863.25
  1258.5 1859.54  1289.5 1859.58  1298.4 1863.52  1311.6 1873.39  1426.7 1902.25
#Mann= 6 ,-1,0
       0      .1       0   583.7    .045       0   718.7    .025       0
     750      .1       0 1209.74     .06       0 1319.74      .1       0
Bank Sta=583.7,718.7
XS Rating Curve= 0 ,0
Exp/Cntr(USF)=0,0
Exp/Cntr=0.3,0.1

Type RM Length L Ch R = 1 ,4232    ,685.4,685.4,685.4
XS GIS Cut Line= 4
2228020.48656663708553.9740648562228161.21376655708443.013060136
2228346.86066778707965.3590538562228483.99825229707816.201835387
#Sta/Elev= 30
       0 1907.97    65.9 1879.69   101.5 1867.68   126.9  1856.6     137  1855.6
   172.8 1842.86   198.4 1836.84   301.3 1828.93   331.4 1823.88   364.1 1823.12
   395.8 1828.37   411.6 1823.22   463.4 1814.47   571.7 1814.47     576 1815.94
  583.391823.156   640.5 1830.23     665 1830.97   687.6 1842.61   709.7 1857.18
     738 1857.66   740.9 1858.57   752.7 1869.02   784.3 1878.77     800 1885.83
   831.4 1889.34   854.1 1887.95   859.8    1890   870.9 1897.88   894.3 1904.33
#Mann= 4 ,-1,0
       0      .1       0   411.6    .045       0  583.39     .06       0
  679.21      .1       0
Bank Sta=411.6,583.39
XS Rating Curve= 0 ,0
Exp/Cntr(USF)=0,0
Exp/Cntr=0.3,0.1

Type RM Length L Ch R = 1 ,3546    ,734.3,734.3,734.3
XS GIS Cut Line= 3
 2228536.7378181708958.1712969782229039.24788312708234.481718454
2229076.43007041708006.184829004
#Sta/Elev= 30
       0 1888.01      45 1870.99    93.7 1855.96   141.1 1843.28     196 1833.45
   273.9 1824.94   350.9 1830.05   426.8  1829.5   454.4 1826.37   478.4 1819.69
   502.61820.996   514.8  1815.2   520.5 1814.44   630.2 1814.44   634.3 1816.18
   637.51820.685   648.9 1831.97   652.7 1833.63     716 1834.57   830.9  1857.9
   843.7 1856.61   876.9 1858.37   886.5 1862.65   898.6 1871.87   955.3 1888.18
   983.7 1888.71   995.8 1895.42  1044.5 1909.69  1056.6 1911.16  1112.4  1934.4
#Mann= 6 ,-1,0
       0      .1       0   502.6    .045       0   637.5     .06       0
     710      .1       0     790     .06       0     830      .1       0
Bank Sta=502.6,637.5
XS Rating Curve= 0 ,0
Exp/Cntr(USF)=0,0
Exp/Cntr=0.3,0.1

Type RM Length L Ch R = 1 ,2812    ,552.7,552.7,552.7
XS GIS Cut Line= 2
2229033.43444173709251.6232492852229800.19010032708629.887207014
#Sta/Elev= 30
       0 1874.48    39.6 1857.87    54.7  1854.6   103.2 1836.22   127.1 1829.88
   145.9  1828.1     1531822.991   160.1 1815.28   168.3 1813.75   270.6 1813.75
   276.7 1815.33   284.21822.991   290.9 1826.02   307.4 1828.28   358.9 1831.98
   420.7 1832.16   509.9 1829.73   586.7  1830.8     635 1829.82   647.2 1830.94
   678.1 1837.48   755.4 1841.42     776 1841.08   782.9 1843.12   797.7 1853.62
   848.3 1861.48   894.4 1862.79   913.7 1871.09   936.5 1873.86   987.2 1884.57
#Mann= 6 ,-1,0
       0      .1       0     153    .045       0   284.2      .1       0
     450     .05       0     610     .06       0     700      .1       0
Bank Sta=153,284.2
XS Rating Curve= 0 ,0
Exp/Cntr(USF)=0,0
Exp/Cntr=0.3,0.1

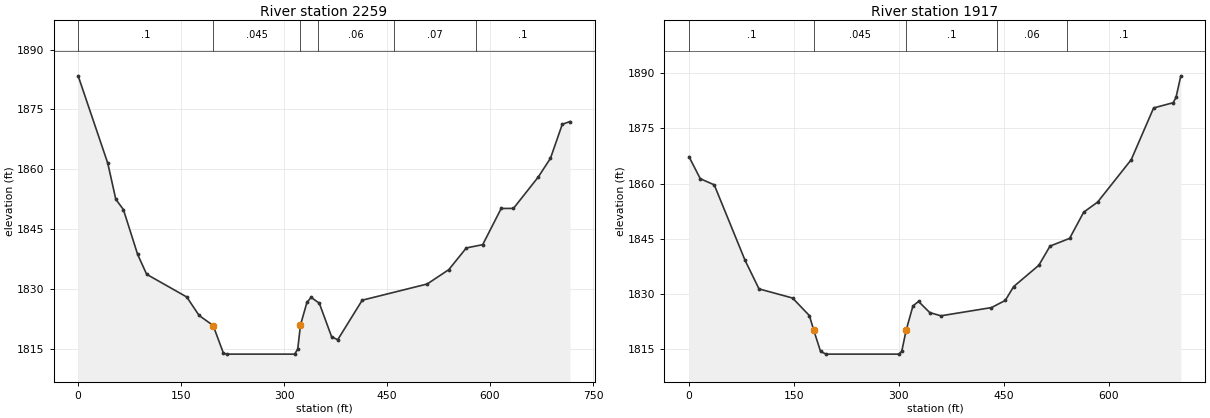
Type RM Length L Ch R = 1 ,2259    ,341.8,341.8,341.8
XS GIS Cut Line= 2
2229363.21995019709616.8028852072230001.47138203709291.410967066
#Sta/Elev= 30
       0  1883.4    43.2 1861.47    54.9 1852.43    65.9 1849.88    86.7 1838.61
    99.8 1833.64   158.2 1827.95   176.2 1823.32   196.7 1820.78   211.6 1813.87
   216.6 1813.62   315.4 1813.62   319.9  1814.9  323.871820.927   333.3 1826.61
   339.4 1827.85   351.3 1826.38   369.2 1817.99   378.1 1817.22   413.8 1827.14
   508.4  1831.2   539.9  1834.8   565.4 1840.24   589.3 1841.07   616.2 1850.14
   634.1 1850.16   670.1    1858     688 1862.73   705.2 1871.24   716.4 1871.94
#Mann= 6 ,-1,0
       0      .1       0   196.7    .045       0  323.87      .1       0
     350     .06       0     460     .07       0     580      .1       0
Bank Sta=196.7,323.87
XS Rating Curve= 0 ,0
Exp/Cntr(USF)=0,0
Exp/Cntr=0.3,0.1

Type RM Length L Ch R = 1 ,1917    ,286.1,286.1,286.1
XS GIS Cut Line= 2
2229432.07992111  709831.65055682230135.07958869709815.060594143
#Sta/Elev= 30
       0 1867.32    16.1 1861.32    36.1 1859.64    80.1 1839.11   100.1  1831.3
   148.1 1828.81   172.1 1824.03   178.4 1820.02   188.1 1814.26   196.1 1813.53
   300.2 1813.53   304.2 1814.31  310.49 1820.05   320.2 1826.66   328.2 1827.89
   344.2 1824.85   360.2 1823.97   432.5 1826.21   452.2 1828.16   464.2 1831.93
   500.2 1837.74   516.2 1842.96   544.2 1845.06   564.3 1852.19   584.3 1854.96
   632.3  1866.5   664.3 1880.59   692.3 1882.02   696.3 1883.45   703.2 1889.34
#Mann= 5 ,-1,0
       0      .1       0   178.4    .045       0  310.49      .1       0
     440     .06       0     540      .1       0
Bank Sta=178.4,310.49
XS Rating Curve= 0 ,0
Exp/Cntr(USF)=0,0
Exp/Cntr=0.3,0.1