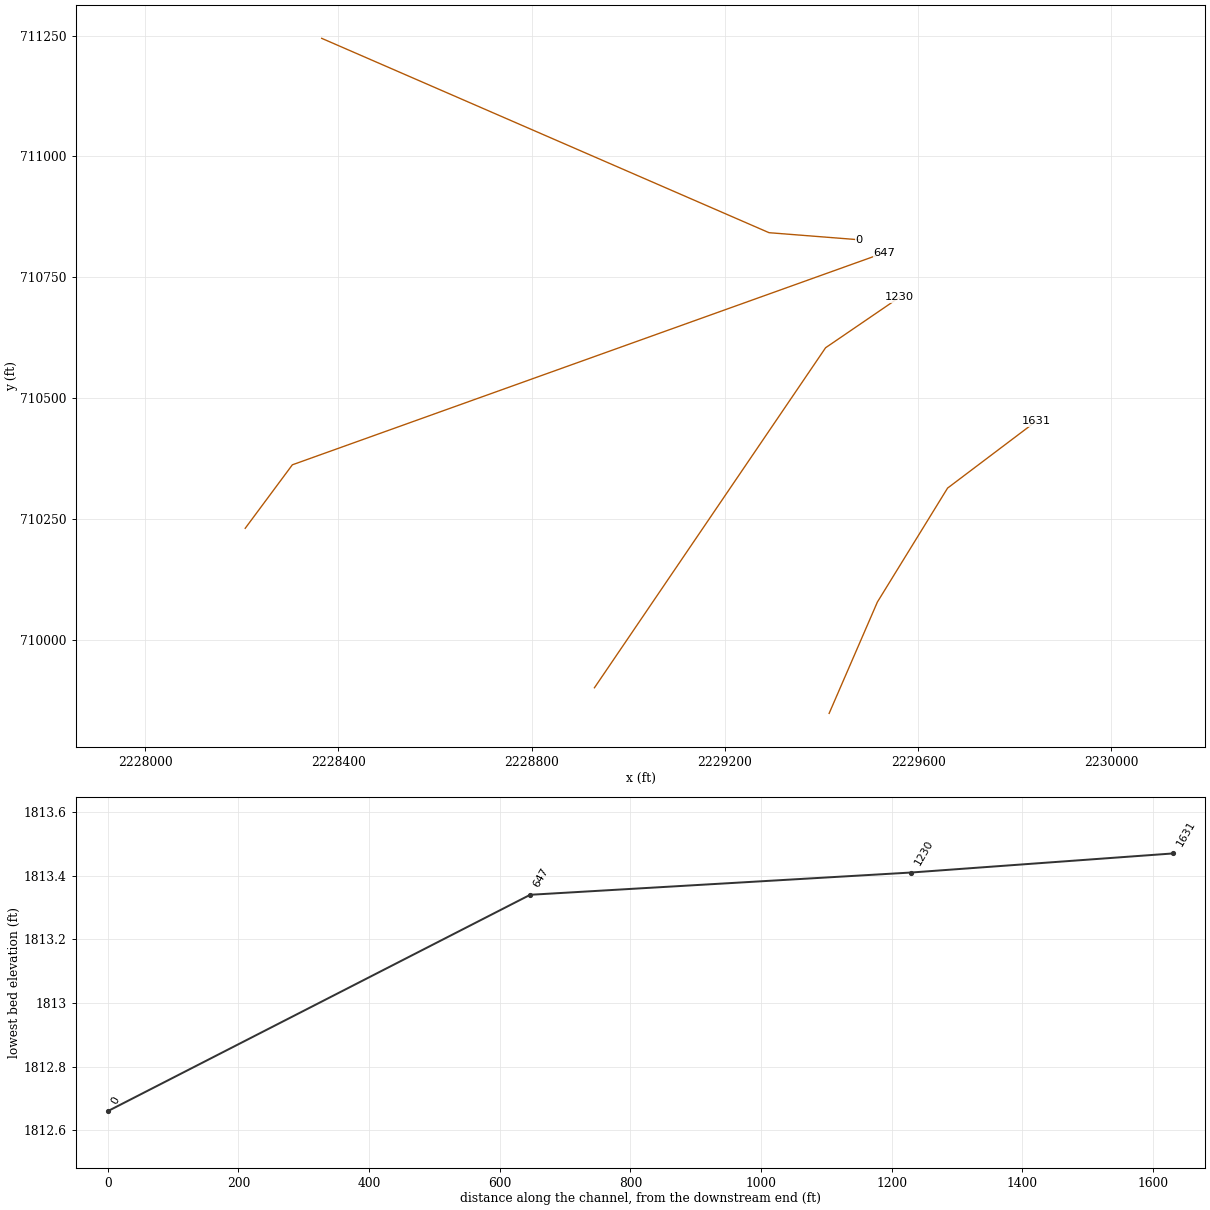
HEC-RAS study MIDFKRIV.prj: MIDFKRIV

--- MIDFKRIV.g01 (geometry) --- (continued)

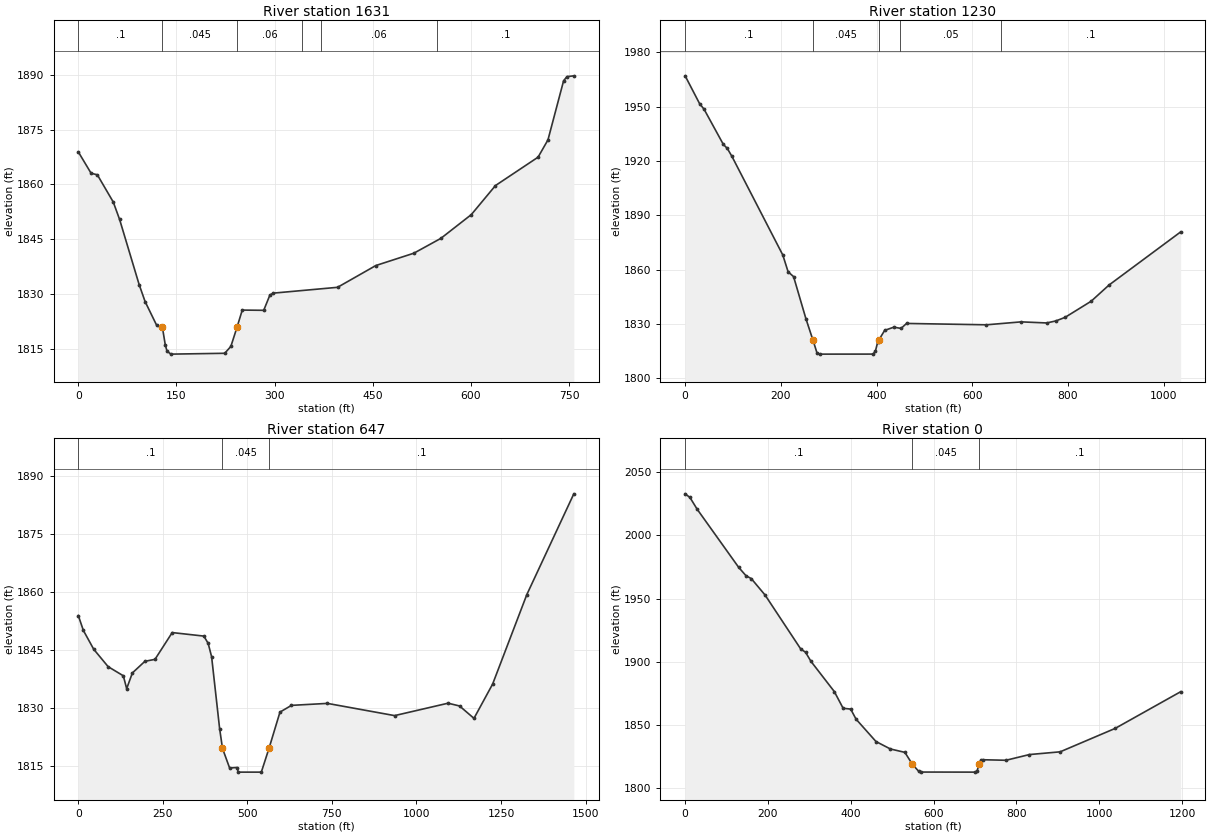
Type RM Length L Ch R = 1 ,1631    ,401.1,401.1,401.1
XS GIS Cut Line= 4
2229415.82577057709847.317814226  2229515.712461710077.829784286
2229660.93504785710313.5774017982229843.69673063710451.487930262
#Sta/Elev= 30
       0 1868.89    19.5 1863.05    29.1 1862.61    53.4 1855.15    63.1 1850.37
    92.9 1832.55     102 1827.89   119.7 1821.37   128.5 1820.79   132.8 1816.09
   135.5 1814.28   141.5 1813.47   223.7  1813.7   233.1 1815.59   242.61820.902
   250.5 1825.54   283.3 1825.48   292.7 1829.65   297.6 1830.18   396.1 1831.78
   454.6 1837.75   512.7 1841.13     554  1845.2   600.5 1851.71   637.4 1859.67
   702.5 1867.45   717.6 1872.19   741.5 1888.39   746.6 1889.52   757.1 1889.74
#Mann= 6 ,-1,0
       0      .1       0   128.5    .045       0   242.6     .06       0
  341.22      .1       0  371.22     .06       0  548.11      .1       0
Bank Sta=128.5,242.6
XS Rating Curve= 0 ,0
Exp/Cntr(USF)=0,0
Exp/Cntr=0.3,0.1

Type RM Length L Ch R = 1 ,1230    ,583.4,583.4,583.4
XS GIS Cut Line= 3
2228930.04014136709900.3269243042229408.46831302710604.058466453
2229561.06364374710708.247054698
#Sta/Elev= 30
       0 1966.95    30.1 1951.65    39.6 1948.51    79.9 1929.09    88.1 1926.91
    97.8 1922.51   204.2 1868.06   215.2 1858.85   226.7 1856.15   252.5 1832.91
     267 1821.25   267.1 1821.25   275.7 1813.99   281.3 1813.41   392.8 1813.43
   397.7 1815.05   402.5 1820.08  405.03 1821.26     417 1826.51   436.3 1828.29
   451.3 1827.59   462.8 1830.34   629.9 1829.59   702.4 1831.21   755.6 1830.61
   774.9 1831.72   794.3 1833.72   848.7  1842.6   886.1 1851.55  1035.7 1880.83
#Mann= 5 ,-1,0
       0      .1       0     267    .045       0  405.03     .06       0
     450     .05       0     660      .1       0
Bank Sta=267.1,405.03
XS Rating Curve= 0 ,0
Exp/Cntr(USF)=0,0
Exp/Cntr=0.3,0.1

Type RM Length L Ch R = 1 ,647     ,646.7,646.7,646.7
XS GIS Cut Line= 3
2228207.23297104710230.3486731222228304.83450652710361.784144627
2229530.20780609710800.815483126
#Sta/Elev= 30
       0 1853.83      15 1849.98    45.6 1845.12    88.2 1840.62   133.1 1838.26
     143 1834.93   159.9    1839     197 1842.01   226.7 1842.51   277.7 1849.44
   371.2 1848.53     384 1846.65   394.2 1843.19   417.9 1824.59   426.4 1819.47
   447.4 1814.42   468.9 1814.53   473.2 1813.34   541.2 1813.34  564.08 1819.53
   596.4 1828.87   630.4 1830.61   736.6 1831.12   935.4 1827.96  1093.5 1831.17
  1127.5 1830.45  1170.1 1827.25  1225.3 1836.12  1326.4 1859.26  1465.4 1885.33
#Mann= 3 ,0,0
       0      .1       0   426.4    .045       0  564.08      .1       0
Bank Sta=426.4,564.08
XS Rating Curve= 0 ,0
Exp/Cntr(USF)=0,0
Exp/Cntr=0.3,0.1

Type RM Length L Ch R = 1 ,0       ,,,
XS GIS Cut Line= 3
 2228365.5659522711244.4543857122229291.42384223710842.192484319
2229477.87928395710827.552040789
#Sta/Elev= 30
       0 2032.85    11.6 2029.97      29 2020.68   129.3 1974.67   146.8 1968.12
   159.8 1965.75     193 1952.79   279.2 1910.05   290.7 1907.55   303.8 1900.32
   360.2  1876.4   381.5 1863.18   399.7 1862.53   412.8 1854.55   460.8 1836.88
   495.7 1830.97   530.6  1828.3   548.7 1818.87   563.9 1813.34   569.8 1812.72
   700.8 1812.66     705 1813.66   709.8 1818.87   713.7 1821.99   718.1 1822.47
   774.8 1822.04   831.3 1826.56   905.6 1828.73  1038.3 1847.241196.498 1876.27
#Mann= 3 ,-1,0
       0      .1       0   548.7    .045       0   709.8      .1       0
Bank Sta=548.7,709.8
XS Rating Curve= 0 ,0
Exp/Cntr(USF)=0,0
Exp/Cntr=0.3,0.1
LCMann Table=0

Chan Stop Cuts=-1
Use User Specified Reach Order=0
Composite Channel Slope=5