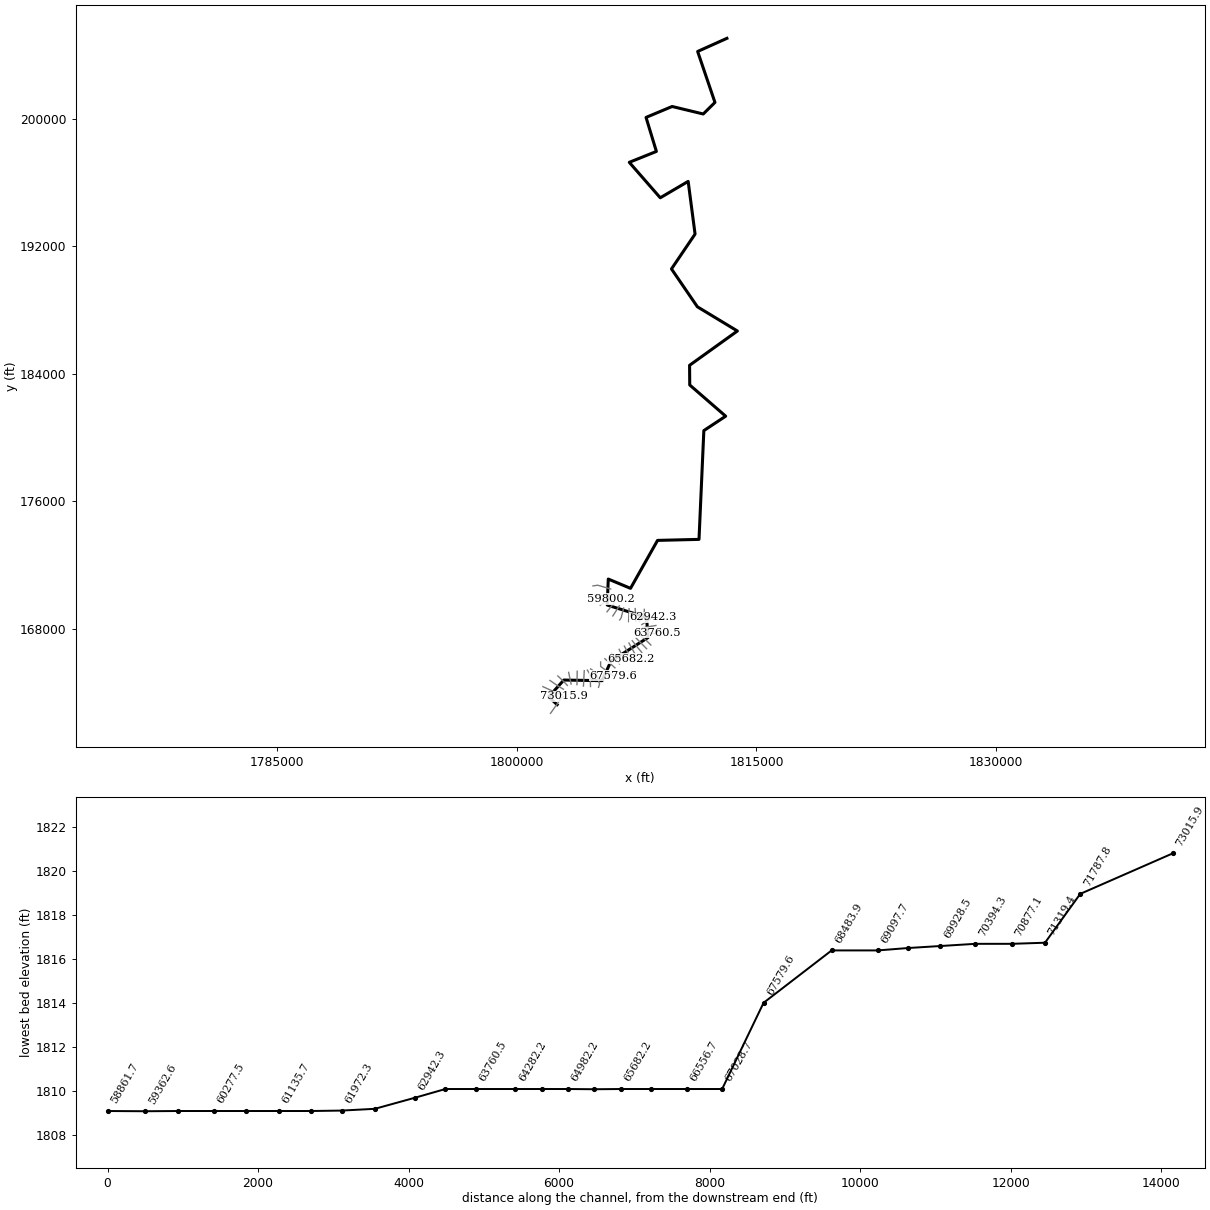
--- MIDFKRV2.prj (project) ---

Proj Title=MIDFKRV2
Current Plan=p01
Default Exp/Contr=0,0
English Units
Geom File=g01
Flow File=f01
Plan File=p01
BEGIN DESCRIPTION:
END DESCRIPTION:
DSS Export Rating Curves= 0
DSS Export Rating Curve Sorted= 0
DSS Export Volume Flow Curves= 0
DXF OffsetX= 0
DXF OffsetY= 0
DXF ScaleX= 0
DXF ScaleY= 0

--- MIDFKRV2.p01 (plan) ---

Plan Title=Floodplain
Program Version=4.00
Geom File=g01
Flow File=f01
K Sum by GR=0
Std Step Tol=0.01
Critical Tol=0.01
Num of Std Step Trials=20
Max Error Tol=0.3
Flow Tol Ratio=0.001
Split Flow NTrial=30
Split Flow Tol=0.02
Split Flow Ratio=0.02
Log Output Level=0
Friction Slope Method=1
Unsteady Friction Slope Method=2
Unsteady Bridges Friction Slope Method=1
Global Log Level=0
CheckData=False
Run HTab=0
Run UNet=0
Run PostProcess=0
UNET Theta=0
UNET Theta Warmup=0
UNET ZTol=0
UNET ZSATol=0
UNET MxIter=0
UNET MaxInSteps=0
UNET DtIC=0
UNET DtMin=0
UNET MaxCRTS=0
UNET WFStab=0
UNET SFStab=0
UNET WFX=0
UNET SFX=0
UNET DSS MLevel=0
UNET DZMax Abort=0
UNET Convert EG Bridges=0
UNET Use Existing IB Tables=0
UNET Froude Limit=0
UNET Froude Power=0
Write IC File=0
Echo Input=False
Echo Output=False
Write Detailed=0

--- MIDFKRV2.f01 (steady flow) ---

Flow Title=NFF Regression Equation
Program Version=4.10
Number of Profiles= 1
Profile Names=P100yr
River Rch & RM=MIDFKRV2,Main            ,73015.9
15704.47
River Rch & RM=MIDFKRV2,Main            ,214.3
   17181
River Rch & RM=MIDFKRV2,Main            ,214.3
17179.22
Boundary for River Rch & Prof#=MIDFKRV2,Main            , 1
Up Type= 0
Dn Type= 3
Dn Slope=0.025
DSS Import GetInterval= 0
DSS Import GetPeak= 0
DSS Import FillOption= 0

--- MIDFKRV2.g01 (geometry) ---

Geom Title=USGS 10m DEM
Program Version=4.10

River Reach=MIDFKRV2        ,Main
Reach XY= 30
     1802521.636      163237.718     1801996.071      163729.777
     1802940.711      164783.142     1805336.544       164744.08
      1805894.27      165974.548     1808205.468      167445.903
     1808123.002      168717.604     1805657.182      169491.982
     1805724.022      171122.624     1807115.949      170539.291
     1808808.658      173549.708     1811402.895      173613.001
     1811705.793      180440.333      1813071.45      181345.691
     1810822.981      183303.614     1810812.495      184538.564
     1813805.644      186691.853     1811300.629      188212.363
     1809679.752      190587.468     1811156.314      192774.968
     1810724.022       196082.26     1808977.691      195053.429
     1807038.632      197278.969     1808735.741      197962.468
     1808087.304      200097.885     1809720.116      200784.083
     1811668.033      200312.728     1812401.106      201039.291
     1811317.772      204237.208     1813149.044      205061.396

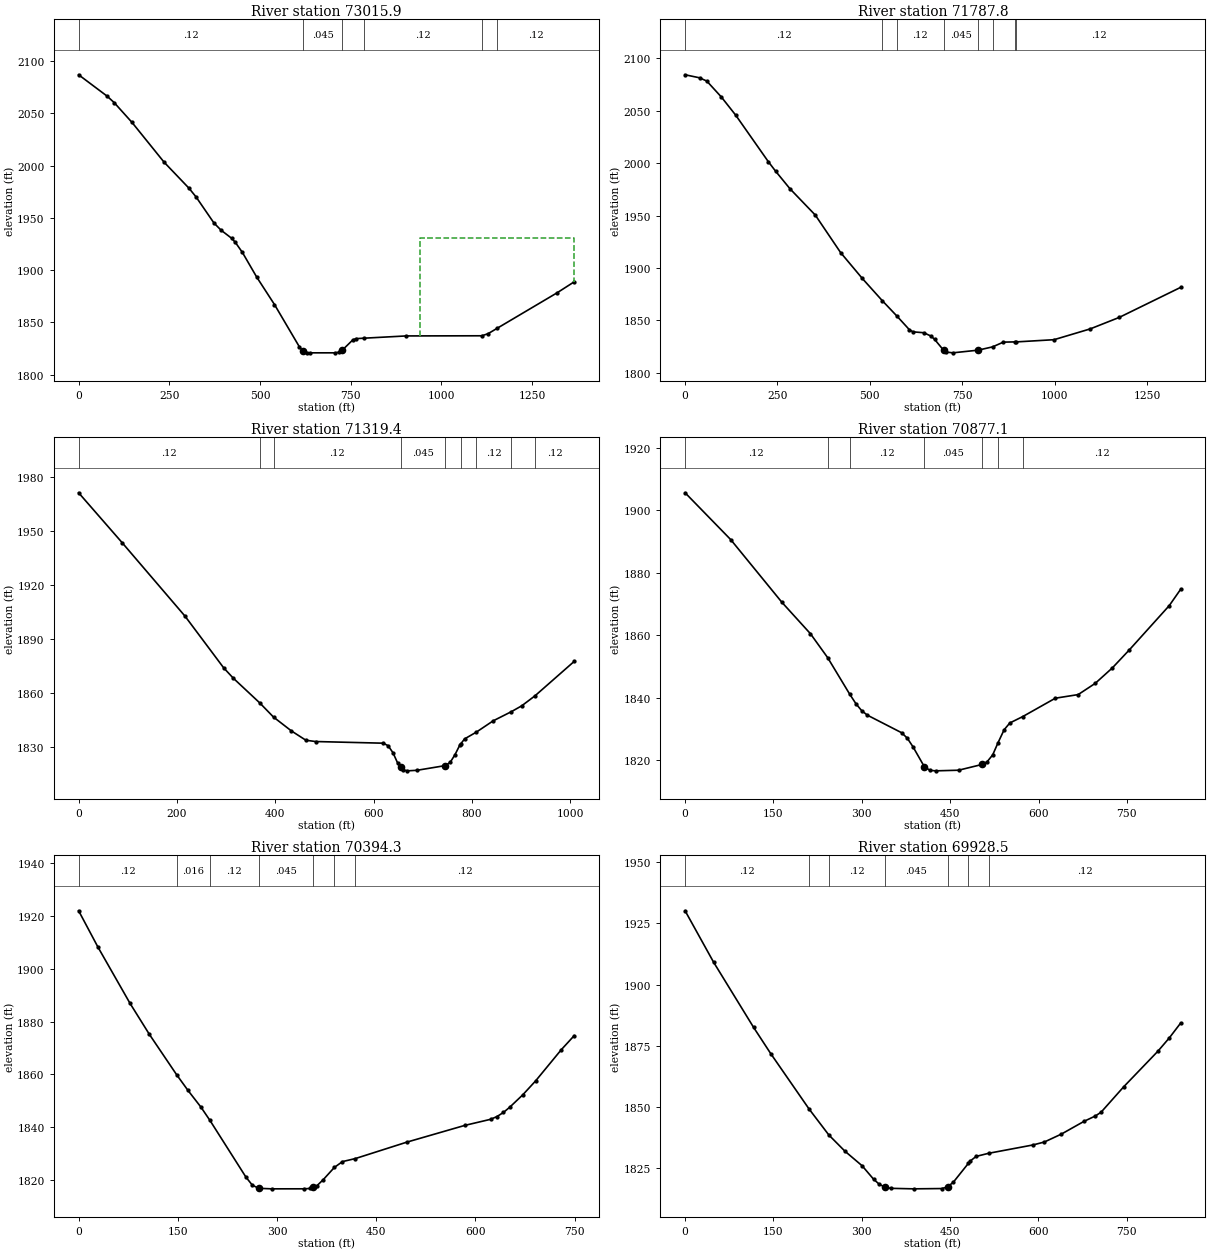
Type RM Length L Ch R = 1 ,73015.9 ,1279.8,1228.1,1176.3
XS GIS Cut Line= 3
      1802106.46      162691.842     1802783.543      163655.384
     1802942.758       163755.63
#Sta/Elev= 30
       0 2086.83    78.5 2066.39    98.1 2060.16   147.2 2041.22   235.5 2003.22
   304.2 1978.28   323.8  1969.9   372.9 1945.05   392.6 1938.13     422 1930.32
   431.8 1926.55   451.4 1916.84   490.7 1893.33   539.8    1867   608.4 1826.55
   618.3 1822.36   628.1 1820.84   637.9 1820.79   706.6  1820.8   716.4 1821.26
   726.2 1823.22   755.7 1833.16   765.5  1834.4  785.541834.788   902.9 1836.97
 1111.251837.111  1128.6 1839.12 1153.761844.332  1318.8 1878.24  1365.8 1888.71
#Mann= 6 ,-1 , 0
       0     .12       0   618.3    .045       0   726.2    .016       0
  785.54     .12       0 1111.25     .06       0 1153.76     .12       0
#XS Ineff= 2 , 0
                          940.98          1930.5
Permanent Ineff=
       F       F
Bank Sta=618.3,726.2
XS Rating Curve= 0 ,0
Exp/Cntr=0.3,0.1

Type RM Length L Ch R = 1 ,71787.8 ,474.1,468.4,463.1
XS GIS Cut Line= 3
     1801630.015      164370.326     1802672.583      163896.878
     1802867.441      163878.021
#Sta/Elev= 30
       0 2084.33    39.2 2081.44    58.7 2078.32    97.9  2063.2     137 2045.75
   225.1 2001.44   244.7  1992.4   283.8 1975.53   352.3 1950.42   420.8 1914.63
   479.5 1889.94  533.221868.862  573.461853.908   606.8 1841.04   616.6 1838.99
   645.9 1838.14   665.5  1834.9   675.3 1831.73  699.211821.497   704.6 1819.82
   724.2 1818.95   792.7  1821.5  831.841824.632   861.2 1829.18  891.82 1829.39
  896.24 1829.39   998.2 1831.49  1096.1 1841.79  1174.4 1852.72  1340.8 1881.43
#Mann= 8 ,-1 , 0
       0     .12       0  533.22    .016       0  573.46     .12       0
  699.21    .045       0   792.7     .12       0  831.84    .016       0
  891.82     .06       0  896.24     .12       0
Bank Sta=699.21,792.7
XS Rating Curve= 0 ,0
Exp/Cntr=0.3,0.1

Type RM Length L Ch R = 1 ,71319.4 ,450.5,442.4,432.2
XS GIS Cut Line= 3
     1802072.733      164759.582     1802606.795      164390.135
      1802916.04      164207.976
#Sta/Elev= 30
       0 1971.18    88.6 1943.44   216.5 1902.64   295.2 1873.91   314.9 1868.14
  368.371854.503  396.511846.597   432.9 1838.91   462.4 1833.73   482.1 1833.01
   619.9 1832.09   629.7 1830.69   639.6 1826.79   649.4 1820.89  654.961818.855
   659.1 1817.34   668.8 1816.73   688.2 1817.02   746.4 1819.66   756.1 1821.47
   765.8  1825.7   775.5 1830.98  777.661831.753   785.2 1834.45  809.151838.218
   843.4 1844.49  880.431849.583   901.6 1852.85  928.621858.407  1008.3 1877.51
#Mann= 9 ,-1 , 0
       0     .12       0  368.37    .016       0  396.51     .12       0
  654.96    .045       0   746.4     .12       0  777.66    .016       0
  809.15     .12       0  880.43    .016       0  928.62     .12       0
Bank Sta=654.96,746.4
XS Rating Curve= 0 ,0
Exp/Cntr=0.3,0.1

Type RM Length L Ch R = 1 ,70877.1 ,505.6,482.7,461.6
XS GIS Cut Line= 3
     1802565.531      165040.461     1802895.889      164728.122
      1803162.19      164447.765
#Sta/Elev= 30
       0 1905.56    77.4  1890.6   164.4 1870.54   212.8 1860.51  241.951852.885
  279.421841.196   290.2 1838.09   299.9 1835.89   309.5 1834.47   367.6 1828.86
   377.2 1827.13   386.9 1824.36   406.3 1817.96   415.9 1816.83   425.6 1816.68
   464.3 1816.88  504.421818.732   512.6 1819.55   522.3  1821.8  531.151825.614
   541.6  1829.8   551.3 1831.98  573.071834.008   628.6  1839.9   667.3 1841.05
   696.3 1844.64   725.3 1849.57   754.3 1855.36     822  1869.5   841.3 1874.71
#Mann= 7 ,-1 , 0
       0     .12       0  241.95    .016       0  279.42     .12       0
   406.3    .045       0  504.42     .12       0  531.15    .016       0
  573.07     .12       0
Bank Sta=406.3,504.42
XS Rating Curve= 0 ,0
Exp/Cntr=0.3,0.1

Type RM Length L Ch R = 1 ,70394.3 ,474.3,465.9,457.5
XS GIS Cut Line= 2
     1803242.978      165265.314     1803396.981      164532.126
#Sta/Elev= 30
       0 1922.01    29.2 1908.25    77.8  1886.9     107 1875.18     1481859.968
   165.4 1853.94   184.9 1847.64  198.46 1842.63     253  1821.1   262.7 1818.05
   272.4 1816.88   291.9 1816.68   340.5 1816.69   350.3 1816.82  354.051817.199
     360  1817.8   369.7 1820.12  386.691824.803   398.9    1827  418.341828.147
   496.2 1834.37   583.8 1840.71   622.7 1843.01   632.4 1844.05   642.2 1845.61
   651.9 1847.63   671.4 1852.27   690.8 1857.54   729.7 1869.38   749.2  1874.7
#Mann= 7 ,-1 , 0
       0     .12       0     148    .016       0  198.46     .12       0
   272.4    .045       0  354.05     .12       0  386.69    .016       0
  418.34     .12       0
Bank Sta=272.4,354.05
XS Rating Curve= 0 ,0
Exp/Cntr=0.3,0.1

Type RM Length L Ch R = 1 ,69928.5 ,426.1,424.7,423.4
XS GIS Cut Line= 3
     1803778.979      165336.571     1803772.151      164909.801
     1803762.589      164494.904
#Sta/Elev= 30
       0 1930.15    48.5 1909.11   116.4 1882.51   145.5  1871.8  210.651849.173
   244.21838.571   271.6 1831.94   300.7 1826.01   320.1 1820.54   329.8 1818.46
   339.5 1817.27   349.2 1816.79     388 1816.58   436.5  1816.7   446.1 1817.42
   455.8 1819.33  481.241826.991   484.7    1828   494.4 1829.83  515.451831.089
   590.9  1834.5   610.2  1835.7   639.2 1838.94   677.8 1844.16   697.1 1846.36
   706.7 1847.89   745.3 1858.32   803.2  1872.8   822.5 1878.21   841.8 1884.28
#Mann= 7 ,-1 , 0
       0     .12       0  210.65    .016       0   244.2     .12       0
   339.5    .045       0   446.1     .12       0  481.24    .016       0
  515.45     .12       0
Bank Sta=339.5,446.1
XS Rating Curve= 0 ,0
Exp/Cntr=0.3,0.1

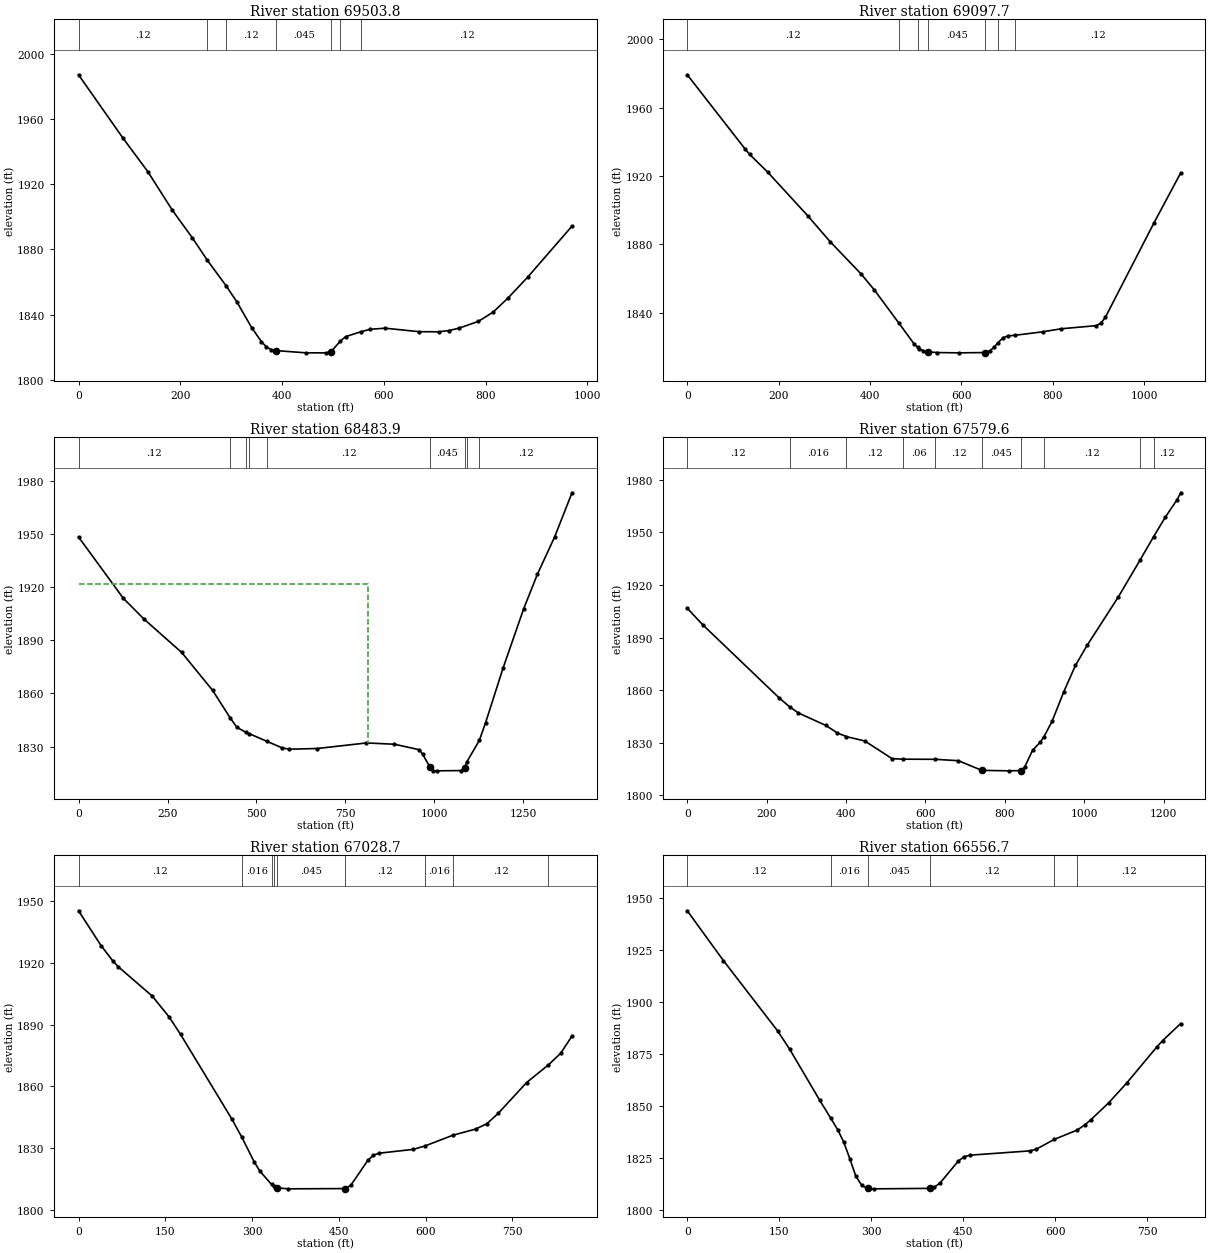
Type RM Length L Ch R = 1 ,69503.8 ,401.8,406,410.2
XS GIS Cut Line= 3
      1804219.96      165372.846     1804194.363      164877.961
     1804169.875      164404.511
#Sta/Elev= 30
       0 1987.11    87.4 1948.21     136 1927.73   184.6 1903.88   223.5 1887.12
  253.31 1873.19  290.351857.467   310.9 1847.88   340.1    1832   359.5 1823.32
   369.2 1820.14     379 1818.39   388.7 1817.86     447 1816.49   485.8 1816.49
   495.6 1817.01  514.641823.751   524.6  1826.4  554.851829.451     573 1830.92
     602 1831.62   669.7 1829.46   708.4  1829.4   727.8 1830.18   747.1 1831.57
   785.8 1835.82   814.8 1841.52   843.8 1850.09   882.6 1862.97   969.6 1894.23
#Mann= 7 ,-1 , 0
       0     .12       0  253.31    .016       0  290.35     .12       0
   388.7    .045       0   495.6     .12       0  514.64    .016       0
  554.85     .12       0
Bank Sta=388.7,495.6
XS Rating Curve= 0 ,0
Exp/Cntr=0.3,0.1

Type RM Length L Ch R = 1 ,69097.7 ,604.7,613.9,623
XS GIS Cut Line= 3
     1804413.284       165407.59     1804589.249      165126.045
     1804611.124      164377.932
#Sta/Elev= 30
       0 1979.27     127 1935.66   136.7 1932.58   175.8 1922.32   263.7 1896.69
   312.5 1881.58   380.6 1862.57   409.8 1853.15  463.03 1833.89   497.2 1821.39
  504.341819.583     507 1818.91   516.7 1817.62   526.4 1817.05   545.8 1816.55
   594.4 1816.38   652.8 1816.54   662.5  1817.5   672.2 1819.84  680.371822.367
   691.6 1825.23   701.4 1826.29  716.931826.648   779.1 1828.73     818 1830.46
   895.8 1832.32   905.5 1833.73   915.2 1837.11  1022.1 1892.67  1080.4 1921.82
#Mann= 7 ,-1 , 0
       0     .12       0  463.03    .016       0  504.34     .04       0
   526.4    .045       0   652.8     .12       0  680.37    .016       0
  716.93     .12       0
Bank Sta=526.4,652.8
XS Rating Curve= 0 ,0
Exp/Cntr=0.3,0.1

Type RM Length L Ch R = 1 ,68483.9 ,880.8,904.3,927.8
XS GIS Cut Line= 4
     1804612.818      165483.587     1804957.863      165252.285
     1805177.791      164537.503     1805112.814      164324.007
#Sta/Elev= 30
       0 1948.19   125.6 1913.69   183.6 1901.98   289.8 1883.11   376.8  1861.7
  425.69 1846.33   444.9  1840.9   471.11837.996  479.741837.308  529.871832.963
   572.8 1829.24   592.5 1828.58   671.2 1828.97     809  1832.1   887.7 1831.37
   956.6  1828.3   966.4 1825.91  987.651818.351     996 1816.47  1005.8 1816.38
  1074.7 1816.54  1084.5 1818.18    10911821.437 1126.041833.517  1143.6 1843.51
  1192.4 1874.09  1250.6  1907.7  1289.4 1927.27  1337.9 1948.35  1386.4  1973.1
#Mann= 9 ,-1 , 0
       0     .12       0  425.69    .016       0   471.1     .12       0
  479.74     .06       0  529.87     .12       0  987.65    .045       0
  1084.5     .12       0    1091    .016       0 1126.04     .12       0
#XS Ineff= 2 , 0
          812.78 1921.95
Permanent Ineff=
       F       F
Bank Sta=987.65,1084.5
XS Rating Curve= 0 ,0
Exp/Cntr=0.3,0.1

Type RM Length L Ch R = 1 ,67579.6 ,554.4,550.8,547.2
XS GIS Cut Line= 3
     1805245.499      165916.606     1805245.499      165636.462
     1806019.797      165063.571
#Sta/Elev= 30
       0 1906.73    38.6  1897.4   231.8 1855.55  257.761850.529   280.1    1847
   348.9 1839.92   378.4 1835.59  401.051833.516   447.2 1831.03     516 1820.94
  544.531820.653  624.871820.573   683.1 1819.79   742.1 1814.27   810.9    1814
   840.4 1814.15   850.2 1816.19   869.8 1825.65   889.5 1830.39  898.941833.569
     919  1842.2   948.5 1859.04     978 1874.12  1007.4 1885.57  1086.1 1913.21
 1140.831934.238 1174.761947.501    1204 1958.54  1233.5 1968.47  1243.3 1972.61
#Mann= 10 ,-1 , 0
       0     .12       0  257.76    .016       0  401.05     .12       0
  544.53     .06       0  624.87     .12       0   742.1    .045       0
   840.4    .016       0  898.94     .12       0 1140.83    .016       0
 1174.76     .12       0
Bank Sta=742.1,840.4
XS Rating Curve= 0 ,0
Exp/Cntr=0.3,0.1

Type RM Length L Ch R = 1 ,67028.7 ,479.5,472,464.5
XS GIS Cut Line= 2
     1805509.655      166123.593     1806140.894      165549.739
#Sta/Elev= 30
       0 1945.34    39.2 1928.31    58.8 1921.12    68.6 1918.15   127.5 1903.83
   156.9 1893.59   176.5 1885.16   264.8 1844.17  282.481835.104     304    1823
   313.8 1818.62  333.711812.206  337.761811.504   343.2 1810.56   362.8 1810.08
   460.9 1810.21   470.7  1811.8   500.1 1823.93   509.9 1826.44   519.7 1827.42
   578.5 1829.27  598.881830.929  647.251836.165   686.4 1839.15     706 1841.77
   725.6 1846.81   774.6 1861.78  812.421870.404   833.5    1876   853.1 1884.43
#Mann= 9 ,-1 , 0
       0     .12       0  282.48    .016       0  333.71     .12       0
  337.76     .08       0   343.2    .045       0   460.9     .12       0
  598.88    .016       0  647.25     .12       0  812.42    .016       0
Bank Sta=343.2,460.9
XS Rating Curve= 0 ,0
Exp/Cntr=0.3,0.1

Type RM Length L Ch R = 1 ,66556.7 ,483,477.1,471.3
XS GIS Cut Line= 2
     1805946.065      166449.815     1806418.804      165798.202
#Sta/Elev= 30
       0 1943.87    58.9 1919.92   147.3  1886.1   166.9 1877.34     216 1852.72
  233.781844.198   245.4 1838.52   255.2 1832.61   265.1 1824.62   274.9 1816.23
   284.7 1811.71   294.5 1810.26   304.3 1810.08  395.251810.299   402.5 1810.78
   412.3 1812.85   441.8 1823.34   451.6 1825.52   461.4 1826.28   559.6 1828.36
   569.4 1829.16  598.921833.903  635.641838.306     648 1840.73   657.8 1843.17
   687.2  1851.4   716.7 1860.93   765.8  1878.3   775.6 1881.45     805 1889.63
#Mann= 6 ,-1 , 0
       0     .12       0  233.78    .016       0   294.5    .045       0
  395.25     .12       0  598.92    .016       0  635.64     .12       0
Bank Sta=294.5,395.25
XS Rating Curve= 0 ,0
Exp/Cntr=0.3,0.1

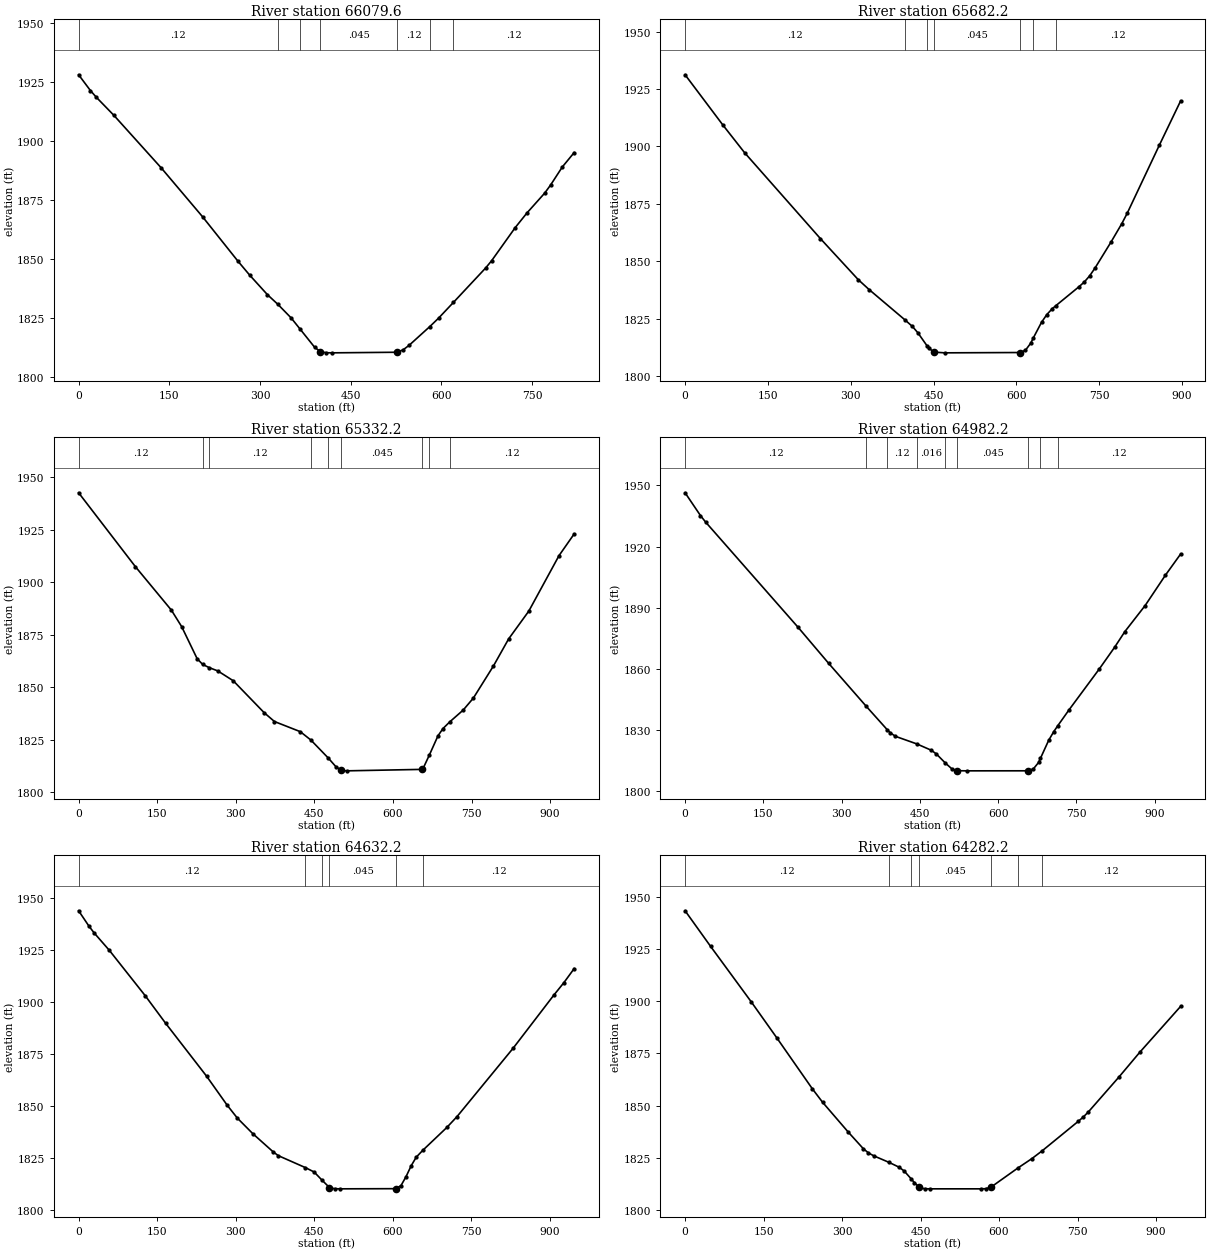
Type RM Length L Ch R = 1 ,66079.6 ,396.5,397.4,398.2
XS GIS Cut Line= 2
     1806401.017        166711.3     1806774.488      165981.931
#Sta/Elev= 30
       0 1928.17    19.5 1921.47    29.3 1918.61    58.5 1910.89   136.6 1888.62
   204.9 1867.88   263.4 1849.02   282.9 1843.06   312.2 1834.78  329.42 1830.69
   351.2 1824.96  366.351820.119   390.2 1812.46  399.821810.585   409.7 1810.12
   419.5 1810.08   526.8 1810.33   536.5 1811.35   546.3 1813.24  580.541821.197
   595.1 1824.79  619.651831.471   673.1 1846.14   682.9  1849.2   721.9 1863.26
   741.4 1869.51   770.6  1877.9   780.4 1881.35   799.9 1889.06   819.4 1895.14
#Mann= 7 ,-1 , 0
       0     .12       0  329.42    .016       0  366.35     .12       0
  399.82    .045       0   526.8     .12       0  580.54    .016       0
  619.65     .12       0
Bank Sta=399.82,526.8
XS Rating Curve= 0 ,0
Exp/Cntr=0.3,0.1

Type RM Length L Ch R = 1 ,65682.2 ,349.7,350,350.3
XS GIS Cut Line= 3
     1806728.425      166912.588     1806980.402      166447.401
     1807155.761      166123.661
#Sta/Elev= 30
       0 1931.22    68.6 1909.27   107.8 1897.25   244.9 1859.87   313.5 1841.96
   333.1 1837.66  397.311824.587   411.5 1821.59   421.3 1818.86  438.741812.903
   440.9 1812.18   450.7 1810.39   470.3 1810.08   606.6 1810.22   616.2  1811.2
   625.9 1814.32  630.271816.482   645.3 1823.37     655 1826.78   664.7 1829.29
  671.141830.605   713.1 1838.87   722.8 1840.95   732.5 1843.63   742.2 1847.03
   771.3 1858.41   790.6 1866.33   800.3 1870.81   858.5 1900.48   897.2 1919.85
#Mann= 7 ,-1 , 0
       0     .12       0  397.31    .016       0  438.74     .12       0
   450.7    .045       0   606.6     .12       0  630.27    .016       0
  671.14     .12       0
Bank Sta=450.7,606.6
XS Rating Curve= 0 ,0
Exp/Cntr=0.3,0.1

Type RM Length L Ch R = 1 ,65332.2 ,343.6,350,357.3
XS GIS Cut Line= 3
     1807016.926      167106.339     1807287.529      166615.243
     1807473.385       166277.95
#Sta/Elev= 30
       0 1942.55   108.2 1907.39   177.1 1886.61   196.7 1878.76   226.2 1863.49
  236.841860.747  249.741859.191   265.6 1857.68   295.1 1852.99   354.1 1837.78
   373.8 1833.56     423 1828.74  443.291824.743  476.161816.248   491.8 1811.83
   501.7  1810.3   511.5 1810.07  654.441810.759     657 1810.98   669.31817.541
   685.9 1826.77   695.5 1830.24  708.211833.369     734 1839.03   753.3  1844.7
   791.8 1860.07   820.7 1872.92   859.2 1886.17   916.9 1912.62   945.8 1922.95
#Mann= 9 ,-1 , 0
       0     .12       0  236.84     .06       0  249.74     .12       0
  443.29    .016       0  476.16     .12       0   501.7    .045       0
  654.44     .12       0   669.3    .016       0  708.21     .12       0
Bank Sta=501.7,654.44
XS Rating Curve= 0 ,0
Exp/Cntr=0.3,0.1

Type RM Length L Ch R = 1 ,64982.2 ,346.1,350,353
XS GIS Cut Line= 3
     1807222.771      167253.058     1807584.316      166799.199
     1807821.763      166515.794
#Sta/Elev= 30
       0  1946.4    29.5 1935.22    39.3 1932.05   216.4 1880.51   275.4 1862.72
  347.351841.697  387.191830.331   393.4 1828.74   403.2    1827   444.21823.283
   472.1 1820.16   481.9 1818.31  498.541814.002   511.4 1811.06   521.2 1810.14
   540.9 1810.08   658.1  1810.1   667.8 1811.07   677.6 1814.17  681.221816.193
     697 1825.03   706.8 1829.32  714.321832.142   735.9 1839.93   794.3 1860.11
   823.5 1870.69     843 1878.32   881.9  1891.1   920.8 1905.99     950 1916.38
#Mann= 9 ,-1 , 0
       0     .12       0  347.35     .06       0  387.19     .12       0
   444.2    .016       0  498.54     .12       0   521.2    .045       0
   658.1     .12       0  681.22    .016       0  714.32     .12       0
Bank Sta=521.2,658.1
XS Rating Curve= 0 ,0
Exp/Cntr=0.3,0.1

Type RM Length L Ch R = 1 ,64632.2 ,345.8,350,350.3
XS GIS Cut Line= 3
     1807459.172      167424.852     1807843.303      167034.319
     1808123.081      166749.878
#Sta/Elev= 30
       0 1943.72    19.6 1936.38    29.4 1933.15    58.7  1924.7   127.2 1902.91
   166.3 1889.63   244.6 1864.18   283.7 1850.32   303.2 1844.09   332.6 1836.64
   371.7 1827.85   381.5 1826.03  433.331820.277     450 1818.17  464.871814.289
   479.3 1810.69   489.1 1810.14   498.9 1810.08   606.2 1810.16   615.9 1811.64
   625.6 1815.96   635.4 1821.18   645.1 1825.32  657.641828.612   703.5 1839.58
     723 1844.81     830 1877.61   907.8 1903.14   927.3 1909.23   946.8 1915.94
#Mann= 6 ,-1 , 0
       0     .12       0  433.33    .016       0  464.87     .12       0
   479.3    .045       0   606.2    .016       0  657.64     .12       0
Bank Sta=479.3,606.2
XS Rating Curve= 0 ,0
Exp/Cntr=0.3,0.1

Type RM Length L Ch R = 1 ,64282.2 ,503,521.7,544.3
XS GIS Cut Line= 3
     1807686.367      167611.596     1808086.626      167285.829
     1808391.391      166981.063
#Sta/Elev= 30
       0 1943.42    48.7 1926.36   126.6 1899.69   175.3 1882.48   243.4 1857.98
   262.9 1851.56   311.6 1837.36   340.8 1829.28   350.5  1827.3   360.3 1825.94
  390.13 1822.73     409 1820.46   418.7 1818.64  432.341814.798   438.2 1813.04
   447.9 1810.76   457.6 1810.13   467.4 1810.08     565 1810.08   574.8 1810.15
   584.6 1810.89  636.191820.096     663 1824.61  682.561828.332   751.2  1842.4
     761 1844.51   770.8 1846.98   829.5 1863.79   868.7 1875.48   947.1 1897.58
#Mann= 7 ,-1 , 0
       0     .12       0  390.13    .016       0  432.34     .12       0
   447.9    .045       0   584.6     .12       0  636.19    .016       0
  682.56     .12       0
Bank Sta=447.9,584.6
XS Rating Curve= 0 ,0
Exp/Cntr=0.3,0.1

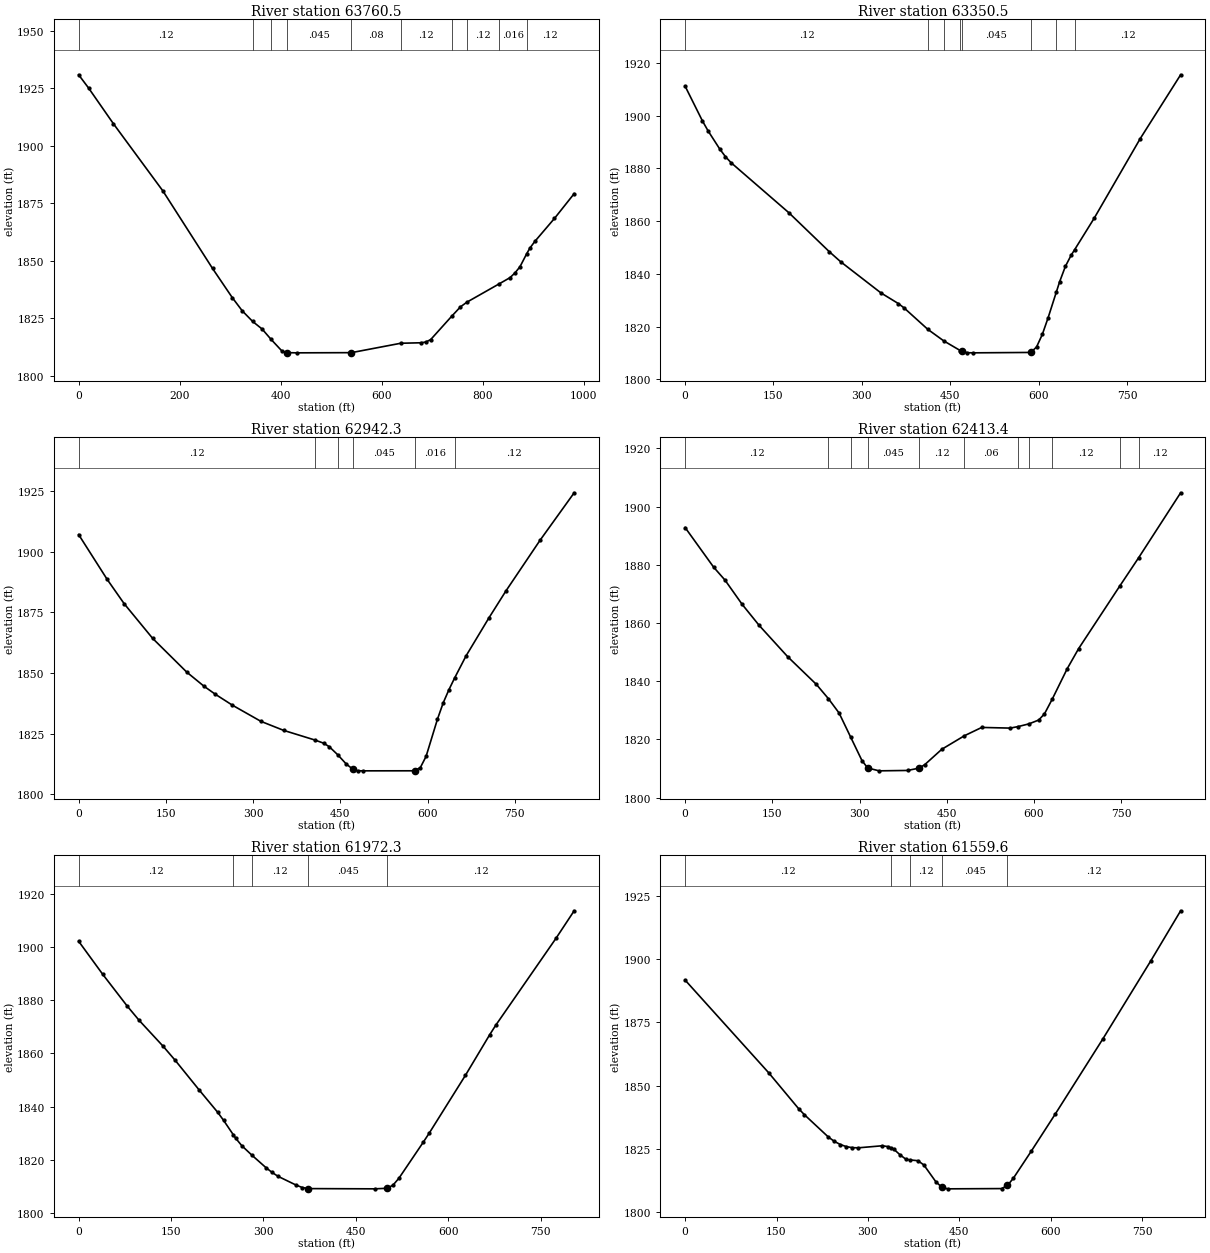
Type RM Length L Ch R = 1 ,63760.5 ,396.2,410,423.3
XS GIS Cut Line= 3
     1807839.459      167838.387     1808698.624      167678.128
     1808781.437      167746.413
#Sta/Elev= 30
       0 1930.84    19.6 1925.12    68.7 1909.64   166.9 1880.38   265.1 1846.75
   304.4 1834.02   324.1  1828.3  344.461823.738   363.3 1820.43  380.891815.973
   402.6 1810.87   412.4 1810.16   432.1 1810.08   540.1 1810.16  637.841814.242
   677.6 1814.45   687.4 1814.76   697.2 1815.85  738.471825.903   756.1 1830.05
  769.021832.104  832.531840.009   854.3 1842.74   864.2 1844.82     874 1847.48
  886.991852.996   893.5 1855.54   903.3 1858.44   942.3 1868.46   981.3 1879.22
#Mann= 10 ,-1 , 0
       0     .12       0  344.46    .016       0  380.89     .12       0
   412.4    .045       0   540.1     .08       0  637.84     .12       0
  738.47    .016       0  769.02     .12       0  832.53    .016       0
  886.99     .12       0
Bank Sta=412.4,540.1
XS Rating Curve= 0 ,0
Exp/Cntr=0.3,0.1

Type RM Length L Ch R = 1 ,63350.5 ,393.5,408.2,423.3
XS GIS Cut Line= 2
     1807874.304      168065.819     1808702.913       168210.08
#Sta/Elev= 30
       0 1911.13    29.3    1898    39.1 1894.14    58.7 1887.34    68.5  1884.4
    78.2 1882.09     176 1863.19   244.5 1848.46   264.1 1844.58   332.5 1832.77
   361.9 1828.76   371.6 1827.12  411.951818.984  438.981814.615  466.931810.958
   469.4 1810.64   479.2 1810.12     489 1810.08   586.8 1810.23   596.6 1812.32
   606.4  1817.1   616.1 1823.33  630.12 1833.11   635.7 1837.01   645.5 1842.85
   655.3 1847.09  661.141849.149   694.4  1861.1   772.6 1891.28   841.1 1915.43
#Mann= 8 ,-1 , 0
       0     .12       0  411.95    .016       0  438.98     .12       0
  466.93     .08       0   469.4    .045       0   586.8     .12       0
  630.12    .016       0  661.14     .12       0
Bank Sta=469.4,586.8
XS Rating Curve= 0 ,0
Exp/Cntr=0.3,0.1

Type RM Length L Ch R = 1 ,62942.3 ,508.7,528.9,549
XS GIS Cut Line= 2
      1807824.43      168265.556     1808543.249      168722.788
#Sta/Elev= 30
       0 1906.98      49 1888.55    78.3 1878.51   127.3 1864.22     186 1850.31
   215.4 1844.55     235 1841.22   264.4 1836.71   313.4 1830.06   352.5 1826.34
  406.371822.357   421.1 1821.08   430.8 1819.64  445.151816.363   460.2 1812.46
  471.561810.331   479.8  1809.7   489.6 1809.68   577.7  1809.7   587.5 1811.05
   597.3 1815.62   616.9 1830.98   626.7 1837.64   636.5 1843.05   646.3 1847.88
   665.9 1856.97     705 1872.54   734.4 1883.71   793.2 1904.63   851.9  1924.2
#Mann= 6 ,-1 , 0
       0     .12       0  406.37    .016       0  445.15     .12       0
  471.56    .045       0   577.7    .016       0   646.3     .12       0
Bank Sta=471.56,577.7
XS Rating Curve= 0 ,0
Exp/Cntr=0.3,0.1

Type RM Length L Ch R = 1 ,62413.4 ,421.6,441.1,460.6
XS GIS Cut Line= 3
     1807660.454      168444.211     1807975.534      169065.281
     1807981.948      169220.829
#Sta/Elev= 30
       0 1892.82      49 1879.21    68.7 1874.72    98.1 1866.41   127.5 1859.14
   176.6 1848.37   225.6 1838.92  246.42 1833.99   264.8 1829.05  284.511820.852
   304.1 1812.72   313.9 1810.17   333.5 1809.18   382.5 1809.31   402.2 1810.11
     412 1811.29   441.4 1816.59  480.231821.238   510.1  1824.1   559.1 1823.87
  573.021824.412  591.381825.333   608.1 1826.65     618 1828.78  631.291833.814
   657.2 1844.34   676.8 1851.23  747.921872.853  779.741882.389   852.1 1904.76
#Mann= 11 ,-1 , 0
       0     .12       0  246.42    .016       0  284.51     .12       0
   313.9    .045       0   402.2     .12       0  480.23     .06       0
  573.02     .12       0  591.38    .016       0  631.29     .12       0
  747.92    .016       0  779.74     .12       0
Bank Sta=313.9,402.2
XS Rating Curve= 0 ,0
Exp/Cntr=0.3,0.1

Type RM Length L Ch R = 1 ,61972.3 ,415.9,412.7,409.4
XS GIS Cut Line= 2
     1807447.029      168466.188     1807409.309      169269.926
#Sta/Elev= 30
       0 1902.15    39.2  1889.7    78.5  1877.9    98.1 1872.46   137.4 1862.63
     157 1857.34   196.2 1846.12   225.7 1837.89   235.5 1834.79  251.421829.333
   255.1 1828.09   264.9 1825.32  281.131821.792   304.2 1817.06     314 1815.28
   323.8  1813.8   353.2  1810.5   363.1  1809.6   372.9 1809.19   480.8  1809.1
   500.4 1809.31   510.2 1810.43   520.1  1813.1   559.3 1826.53   569.1 1829.98
     628 1851.75   667.2 1866.93   677.1 1870.53   775.2 1903.29   804.6  1913.6
#Mann= 5 ,-1 , 0
       0     .12       0  251.42    .016       0  281.13     .12       0
   372.9    .045       0   500.4     .12       0
Bank Sta=372.9,500.4
XS Rating Curve= 0 ,0
Exp/Cntr=0.3,0.1

Type RM Length L Ch R = 1 ,61559.6 ,431.9,423.9,415.8
XS GIS Cut Line= 2
     1806994.252      168447.415     1807026.302      169259.842
#Sta/Elev= 30
       0 1891.79   137.1 1855.08   186.1 1840.89   195.9 1838.42   235.1  1829.6
   244.9 1827.89   254.7 1826.64   264.5 1825.81   274.3  1825.4   284.1 1825.33
   323.3 1826.14   333.1 1825.82  337.651825.295   342.9 1824.69   352.6 1822.58
   362.4 1820.78  369.771820.517     382 1820.23   391.8 1818.53   411.4 1811.89
   421.2 1809.72     431 1809.08   519.2 1809.18     529 1810.41   538.8 1813.35
   568.2 1824.07   607.4 1838.72   685.7 1868.57   764.1  1899.4   813.1 1919.25
#Mann= 5 ,-1 , 0
       0     .12       0  337.65    .016       0  369.77     .12       0
   421.2    .045       0     529     .12       0
Bank Sta=421.2,529
XS Rating Curve= 0 ,0
Exp/Cntr=0.3,0.1

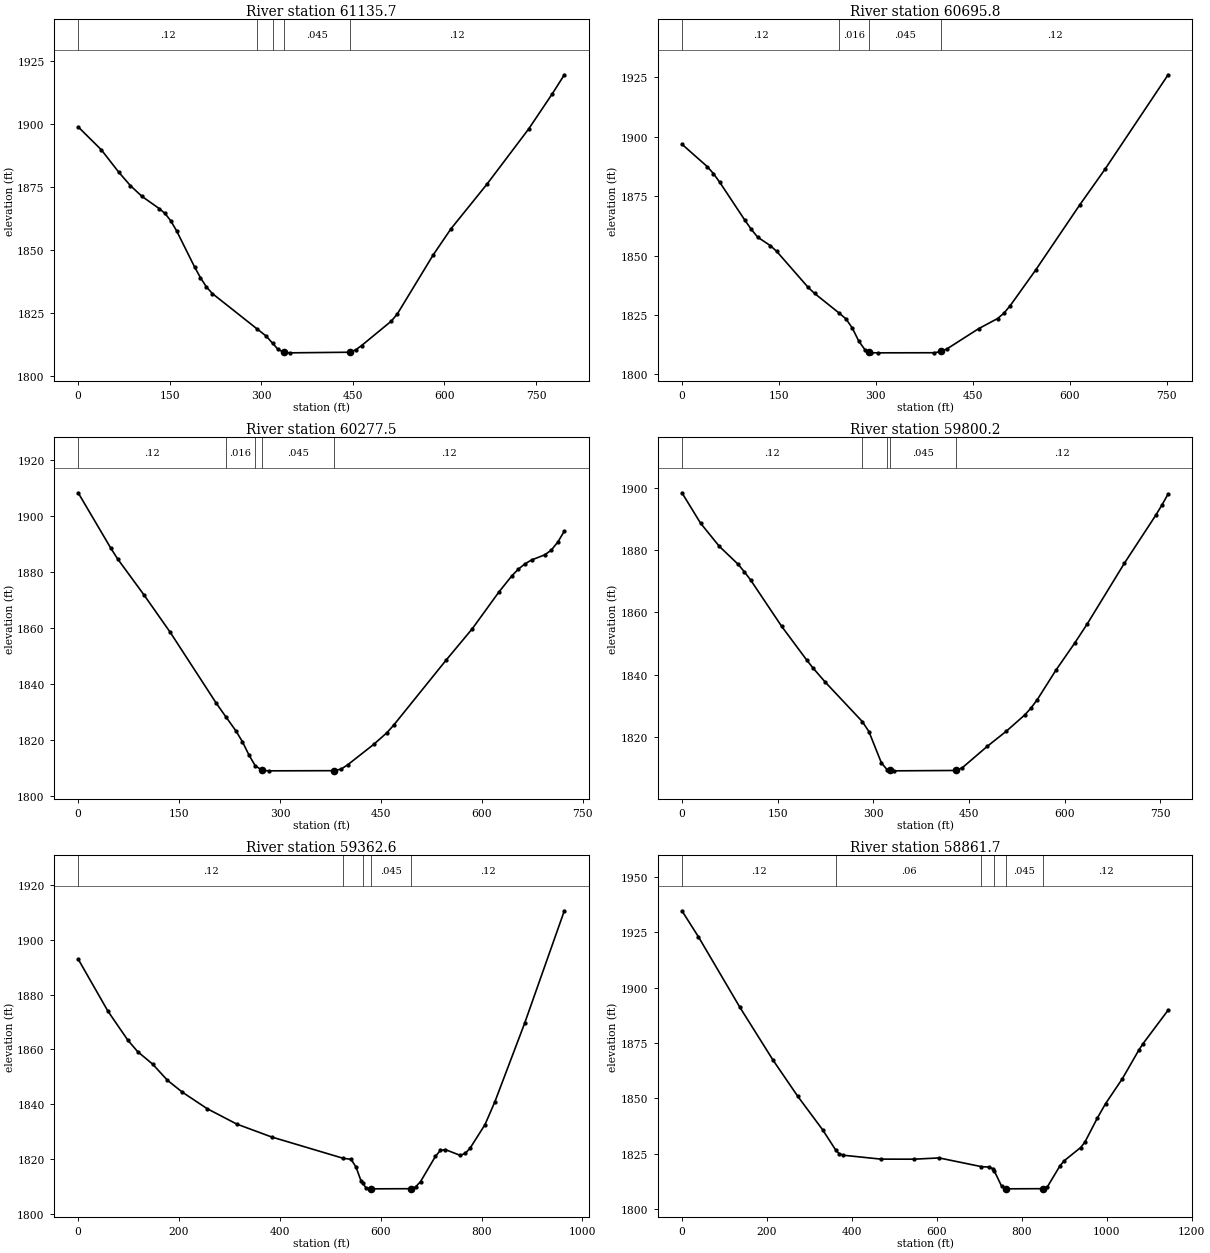
Type RM Length L Ch R = 1 ,61135.7 ,451.9,439.8,427.8
XS GIS Cut Line= 3
     1806438.423      168556.773     1806529.203      168690.106
       1806685.9        169305.7
#Sta/Elev= 30
       0 1898.96      38 1889.82    66.4 1880.96    85.4 1875.63   104.4 1871.33
   132.8 1866.46   142.3 1864.51   151.8 1861.57   161.3 1857.59   190.6  1843.3
   200.4 1838.94   210.2 1835.27   219.9 1832.65  293.621818.497   307.9 1815.77
  318.691812.858   327.4 1810.46   337.2 1809.28     347 1809.08   444.7 1809.32
   454.5 1810.24   464.3 1811.97   513.1 1821.71   522.9 1824.56   581.5 1847.97
   610.8 1858.43   669.5 1876.09   737.9 1898.07     777  1912.2   796.5 1919.67
#Mann= 5 ,-1 , 0
       0     .12       0  293.62    .016       0  318.69     .08       0
   337.2    .045       0   444.7     .12       0
Bank Sta=337.2,444.7
XS Rating Curve= 0 ,0
Exp/Cntr=0.3,0.1

Type RM Length L Ch R = 1 ,60695.8 ,421.7,418.3,414.8
XS GIS Cut Line= 2
     1806008.399      168806.702     1806415.244      169439.572
#Sta/Elev= 30
       0 1896.84    39.1 1887.44    48.8 1884.47    58.6 1880.79    97.7 1864.75
   107.5 1860.98   117.2 1857.74   136.8 1854.19   146.6 1851.77   195.4  1836.6
   205.2 1834.09  243.761825.704     254 1823.32   263.8 1819.44   273.6 1814.05
   283.4 1810.32  289.941809.518   293.1 1809.13   302.9 1809.08   390.8 1809.12
  401.291809.664   410.4 1810.78   459.2 1819.25   488.6 1823.52   498.3 1825.76
   508.1 1828.95   547.2 1843.82   615.6 1871.29   654.6 1886.26   752.4 1926.04
#Mann= 4 ,-1 , 0
       0     .12       0  243.76    .016       0  289.94    .045       0
  401.29     .12       0
Bank Sta=289.94,401.29
XS Rating Curve= 0 ,0
Exp/Cntr=0.3,0.1

Type RM Length L Ch R = 1 ,60277.5 ,491.5,477.3,462.9
XS GIS Cut Line= 2
     1805644.223      169065.287     1806089.441      169634.364
#Sta/Elev= 30
       0 1908.19    48.8 1888.33    58.6 1884.64    97.6 1871.86   136.7  1858.5
     205 1833.27  219.271828.405   234.3 1823.38   244.1 1819.47   253.9 1814.68
  263.06 1810.94   273.4 1809.25   283.2 1809.08   380.8 1809.14   390.6 1809.69
   400.3 1811.18   439.4 1818.55   458.9 1822.68   468.7 1825.31   546.8 1848.54
   585.8 1859.76   624.9 1872.71   644.4 1878.56   654.2 1880.98     664 1882.86
   673.7 1884.23   693.2 1886.05     703 1887.72   712.8 1890.62   722.5 1894.53
#Mann= 5 ,-1 , 0
       0     .12       0  219.27    .016       0  263.06     .12       0
   273.4    .045       0   380.8     .12       0
Bank Sta=273.4,380.8
XS Rating Curve= 0 ,0
Exp/Cntr=0.3,0.1

Type RM Length L Ch R = 1 ,59800.2 ,457.1,437.6,417.7
XS GIS Cut Line= 2
      1805215.41      169488.267     1805873.731      169872.288
#Sta/Elev= 30
       0 1898.37    29.3 1888.58    58.6 1881.17    87.9 1875.45    97.7 1873.03
   107.5 1870.41   156.3 1855.49   195.4 1844.71   205.2 1842.17   224.7 1837.56
  282.741824.902   293.1 1821.69   312.7 1811.62  322.211809.316   325.91809.202
   332.2 1809.08   429.9  1809.2   439.7 1810.11   478.8 1816.98   508.1 1821.74
   537.4 1827.03   547.2 1829.25     557 1831.94   586.3 1841.42   615.6 1850.08
   635.1 1856.18   693.7 1875.79   742.6 1891.11   752.4 1894.42   762.1 1897.99
#Mann= 5 ,-1 , 0
       0     .12       0  282.74    .016       0  322.21     .12       0
   325.9    .045       0   429.9     .12       0
Bank Sta=325.9,429.9
XS Rating Curve= 0 ,0
Exp/Cntr=0.3,0.1

Type RM Length L Ch R = 1 ,59362.6 ,511.8,500.9,489.9
XS GIS Cut Line= 2
     1804847.966      170099.863      1805811.98      170106.377
#Sta/Elev= 30
       0 1892.93      59 1873.92    98.4 1863.36     118 1859.14   147.6  1854.6
   177.1 1848.68   206.6 1844.35   255.8 1838.33   314.8 1832.68   383.6    1828
  525.961820.193     541 1819.87   550.9 1817.03   560.7 1812.06  564.651811.027
   570.6 1809.47   580.4 1809.07   659.1 1809.12   668.9 1809.75   678.8 1811.69
   708.3 1820.89   718.1 1823.08     728  1823.4   757.5 1821.29   767.3 1821.98
   777.1 1823.91   806.6 1832.48   826.3 1840.86   885.3 1869.52     964 1910.56
#Mann= 5 ,-1 , 0
       0     .12       0  525.96    .016       0  564.65     .04       0
   580.4    .045       0   659.1     .12       0
Bank Sta=580.4,659.1
XS Rating Curve= 0 ,0
Exp/Cntr=0.3,0.1

Type RM Length L Ch R = 1 ,58861.7 ,633.7,600.2,565.3
XS GIS Cut Line= 3
     1804765.279      170693.449     1805063.925      170736.113
     1805872.783      170499.678
#Sta/Elev= 30
       0 1934.73    38.9 1922.94   136.2 1891.18   214.1 1867.35   272.5 1850.93
   331.1 1835.79  362.371826.497   370.3 1824.96   380.1 1824.26   468.3 1822.51
   546.6 1822.48   605.4 1823.05  704.681819.121     723  1818.9   732.8 1818.14
  735.311817.133   752.4 1810.31   762.2 1809.08   850.4 1809.16   860.2 1809.98
   889.6 1819.39   899.4 1821.71   938.6 1827.75   948.4 1830.14   977.8 1841.07
   997.4 1847.64  1036.6 1858.82  1075.8 1871.88  1085.6 1874.75  1144.4 1889.82
#Mann= 6 ,-1 , 0
       0     .12       0  362.37     .06       0  704.68    .016       0
  735.31     .12       0   762.2    .045       0   850.4     .12       0
Bank Sta=762.2,850.4
XS Rating Curve= 0 ,0
Exp/Cntr=0.3,0.1