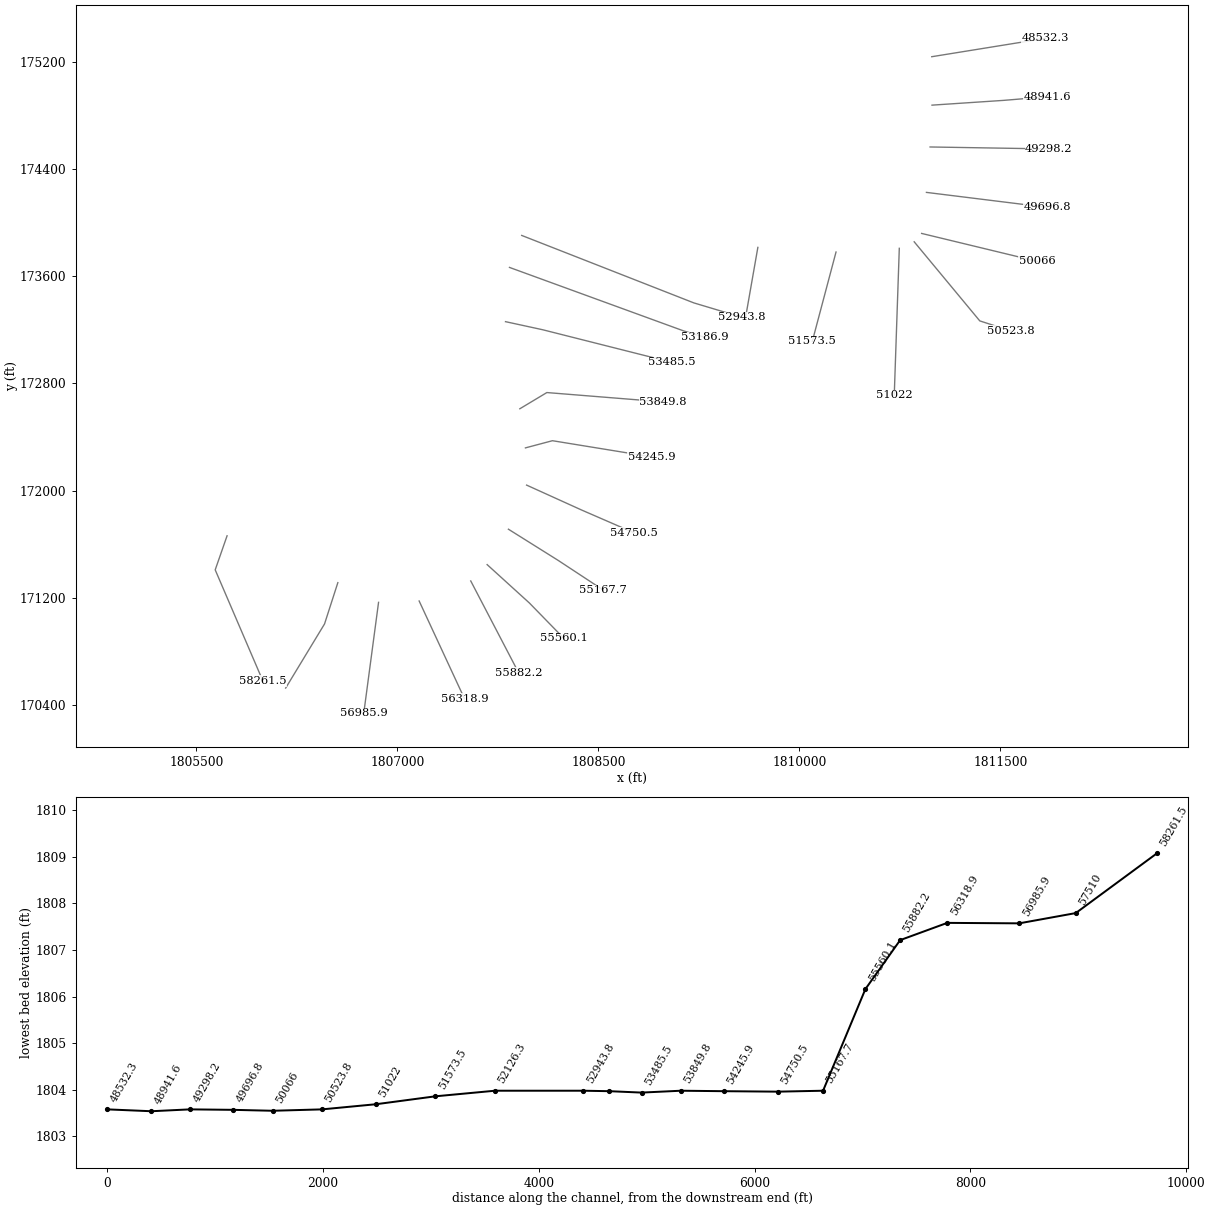
HEC-RAS study MIDFKRV2.prj: MIDFKRV2

--- MIDFKRV2.g01 (geometry) --- (continued)

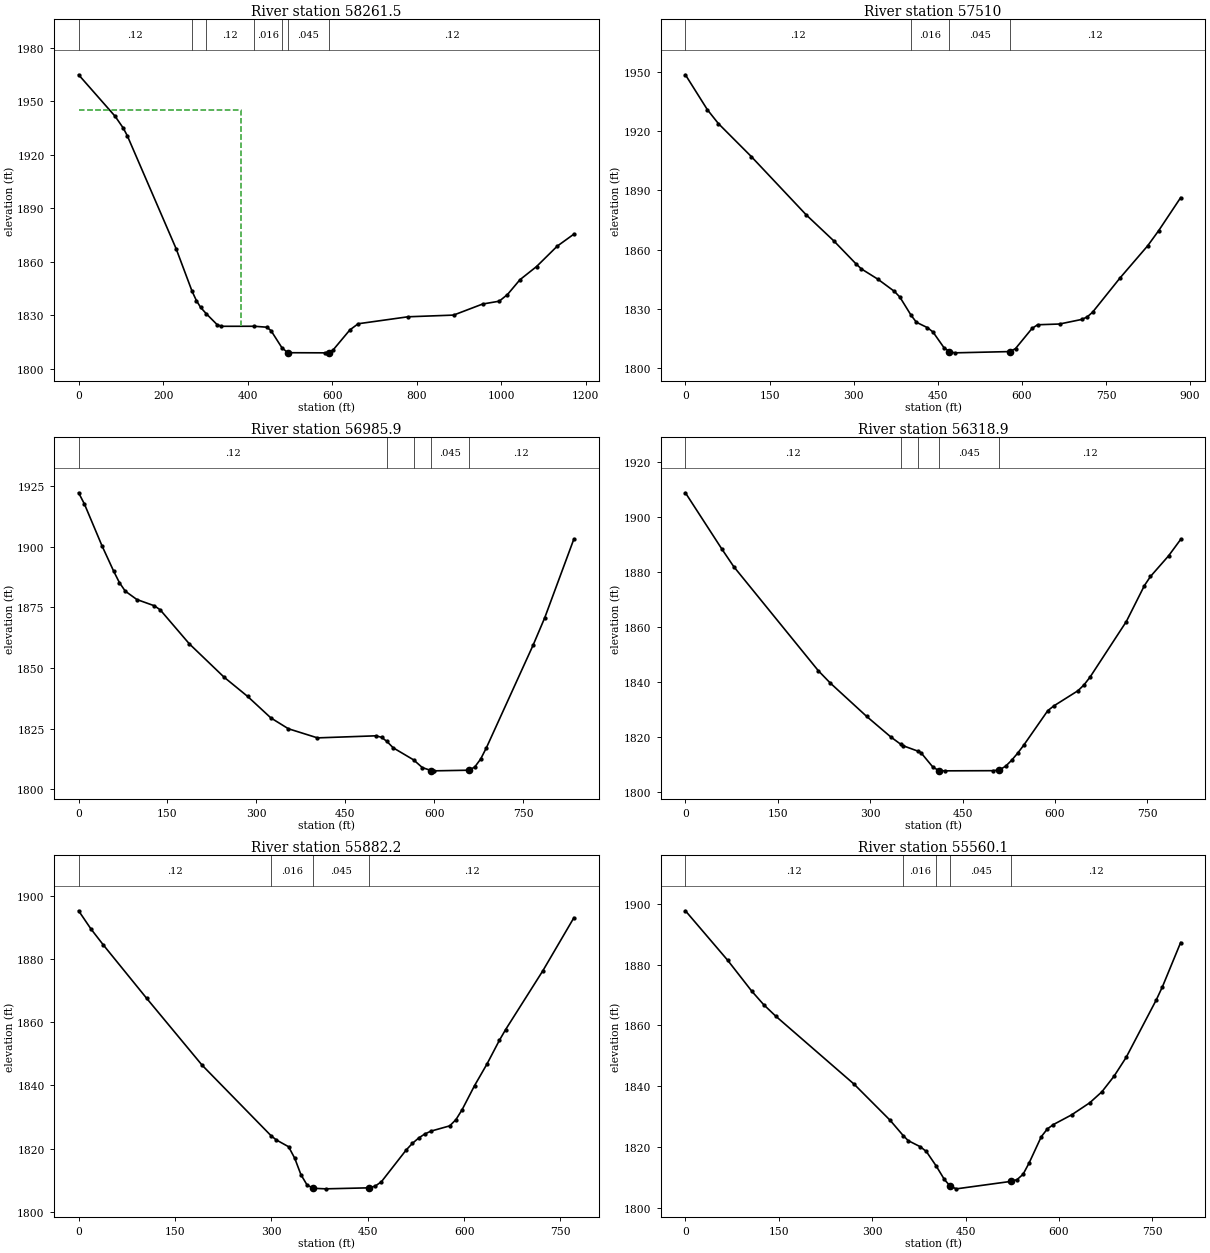
Type RM Length L Ch R = 1 ,58261.5 ,786.9,751.5,716.6
XS GIS Cut Line= 3
     1805729.107       171663.14     1805640.465      171409.031
      1805996.68      170579.087
#Sta/Elev= 30
       0 1964.89    86.5  1941.6   105.7 1935.01   115.3  1930.7   230.7 1867.49
  268.581843.568   278.9 1838.31   288.8 1834.54  302.011831.024     328 1824.84
   337.8 1823.94  415.671823.964   445.8 1823.43   455.6 1821.45  480.921812.048
   494.9 1809.14   583.3 1809.07   593.1 1809.25   602.9 1810.82   642.2 1821.94
   661.8 1825.37   779.6 1829.27   887.6 1830.22   956.3 1836.42   995.6 1838.01
  1015.2 1841.75  1044.7 1850.05  1083.9 1857.41    1133 1868.87  1172.3 1875.58
#Mann= 7 ,-1 , 0
       0     .12       0  268.58    .016       0  302.01     .12       0
  415.67    .016       0  480.92     .12       0   494.9    .045       0
   593.1     .12       0
#XS Ineff= 2 , 0
          383.95 1945.12
Permanent Ineff=
       F       F
Bank Sta=494.9,593.1
XS Rating Curve= 0 ,0
Exp/Cntr=0.3,0.1

Type RM Length L Ch R = 1 ,57510   ,508.6,524.1,539.6
XS GIS Cut Line= 3
     1806555.707      171313.378     1806456.437      171005.385
      1806166.38      170526.792
#Sta/Elev= 30
       0 1948.44    39.2 1930.76    58.8 1923.76   117.7 1907.02   215.7 1877.51
   264.8 1864.38     304 1852.87   313.8 1850.25   343.2 1845.05   372.7 1838.88
   382.5 1835.97  402.521826.764     412 1823.24   431.6 1820.54   441.4 1818.37
     461 1810.45   470.9 1808.37   480.7 1807.79   578.9 1808.43   588.7 1809.95
   618.1 1820.11     628 1821.99   667.2 1822.37   706.5 1824.67   716.3 1825.91
   726.1 1828.33   775.2 1845.71   824.3 1861.91     844  1869.6   883.2  1886.3
#Mann= 4 ,-1 , 0
       0     .12       0  402.52    .016       0   470.9    .045       0
   578.9     .12       0
Bank Sta=470.9,578.9
XS Rating Curve= 0 ,0
Exp/Cntr=0.3,0.1

Type RM Length L Ch R = 1 ,56985.9 ,645.9,667,688.1
XS GIS Cut Line= 2
     1806859.567      171166.452     1806749.092      170337.885
#Sta/Elev= 30
       0 1922.22     9.8 1917.58    39.3 1900.45      59 1889.98    68.8  1885.2
    78.7 1881.67    98.3 1878.21   127.8 1875.63   137.7 1873.96   186.8 1859.95
   245.8 1846.13   285.2 1838.27   324.5 1829.39     354 1824.93   403.2 1821.16
   501.5 1822.01   511.4  1821.4  520.471819.669     531 1817.06  565.391812.094
   580.2  1808.9  595.13 1807.69   599.9 1807.57   658.9 1807.83   668.7 1809.18
   678.6 1812.44   688.4 1817.15   767.1 1859.39   786.7 1870.66   835.9 1903.13
#Mann= 5 ,-1 , 0
       0     .12       0  520.47    .016       0  565.39     .12       0
  595.13    .045       0   658.9     .12       0
Bank Sta=595.13,658.9
XS Rating Curve= 0 ,0
Exp/Cntr=0.3,0.1

Type RM Length L Ch R = 1 ,56318.9 ,434.8,436.7,438.7
XS GIS Cut Line= 2
     1807162.525      171176.503     1807500.937      170447.165
#Sta/Elev= 30
       0 1908.78    58.8 1888.43    78.4 1881.92   215.7 1844.04   235.3 1839.51
   294.2  1827.4   333.4 1819.92  349.211817.311     353 1816.75  378.171814.691
   382.4 1814.19     402 1808.88   411.8 1807.66   421.6 1807.58   500.1 1807.64
   509.9 1807.97   519.7 1809.23   529.5  1811.4   539.3 1813.98   549.1 1816.87
   588.3 1829.49   598.1 1831.21   637.3 1836.74   647.1 1838.86     657 1841.73
   715.8 1861.92   745.2 1875.02     755 1878.32   784.4 1885.83     804  1891.8
#Mann= 5 ,-1 , 0
       0     .12       0  349.21    .016       0  378.17     .12       0
   411.8    .045       0   509.9     .12       0
Bank Sta=411.8,509.9
XS Rating Curve= 0 ,0
Exp/Cntr=0.3,0.1

Type RM Length L Ch R = 1 ,55882.2 ,310.1,322.1,333.1
XS GIS Cut Line= 3
     1807547.516      171326.139      1807734.24      170968.252
     1807904.077       170642.73
#Sta/Elev= 30
       0 1895.42    19.2 1889.65    38.4  1884.6   105.7  1867.7   192.2 1846.44
  299.791824.009   307.6 1822.74   326.8 1820.57   336.4  1816.9     346 1811.71
   355.6 1808.42   365.2 1807.39   384.4 1807.21     452 1807.53   461.6 1808.07
   471.3 1809.47     510 1819.58   519.6 1821.65   529.3 1823.34   538.9 1824.62
   548.6 1825.53   577.6 1827.19   587.2 1829.14   596.9 1832.33   616.2 1839.94
   635.6 1846.81   654.9 1854.33   664.6 1857.74   722.5 1876.38   770.8 1893.19
#Mann= 4 ,-1 , 0
       0     .12       0  299.79    .016       0   365.2    .045       0
     452     .12       0
Bank Sta=365.2,452
XS Rating Curve= 0 ,0
Exp/Cntr=0.3,0.1

Type RM Length L Ch R = 1 ,55560.1 ,384.5,392.4,400.5
XS GIS Cut Line= 3
     1807669.989      171447.983     1807985.044      171161.777
     1808243.208      170896.992
#Sta/Elev= 30
       0 1897.78    67.7 1881.52   106.4 1871.34   125.8 1866.83   145.1 1863.06
   270.9 1840.66   328.9 1828.73  349.821823.714   357.9 1822.04   377.3 1820.03
     387 1818.47  402.631813.753     416 1809.24   425.6 1806.98   435.4 1806.16
     523 1808.62   532.7  1809.2   542.4 1810.96   552.2 1814.74   571.6 1823.33
   581.4 1825.91   591.1 1827.34   620.3 1830.53   649.5 1834.52   668.9 1838.12
   688.4 1843.24   707.9 1849.45   756.5 1868.48   766.3 1872.78   795.5 1887.32
#Mann= 5 ,-1 , 0
       0     .12       0  349.82    .016       0  402.63     .12       0
   425.6    .045       0     523     .12       0
Bank Sta=425.6,523
XS Rating Curve= 0 ,0
Exp/Cntr=0.3,0.1

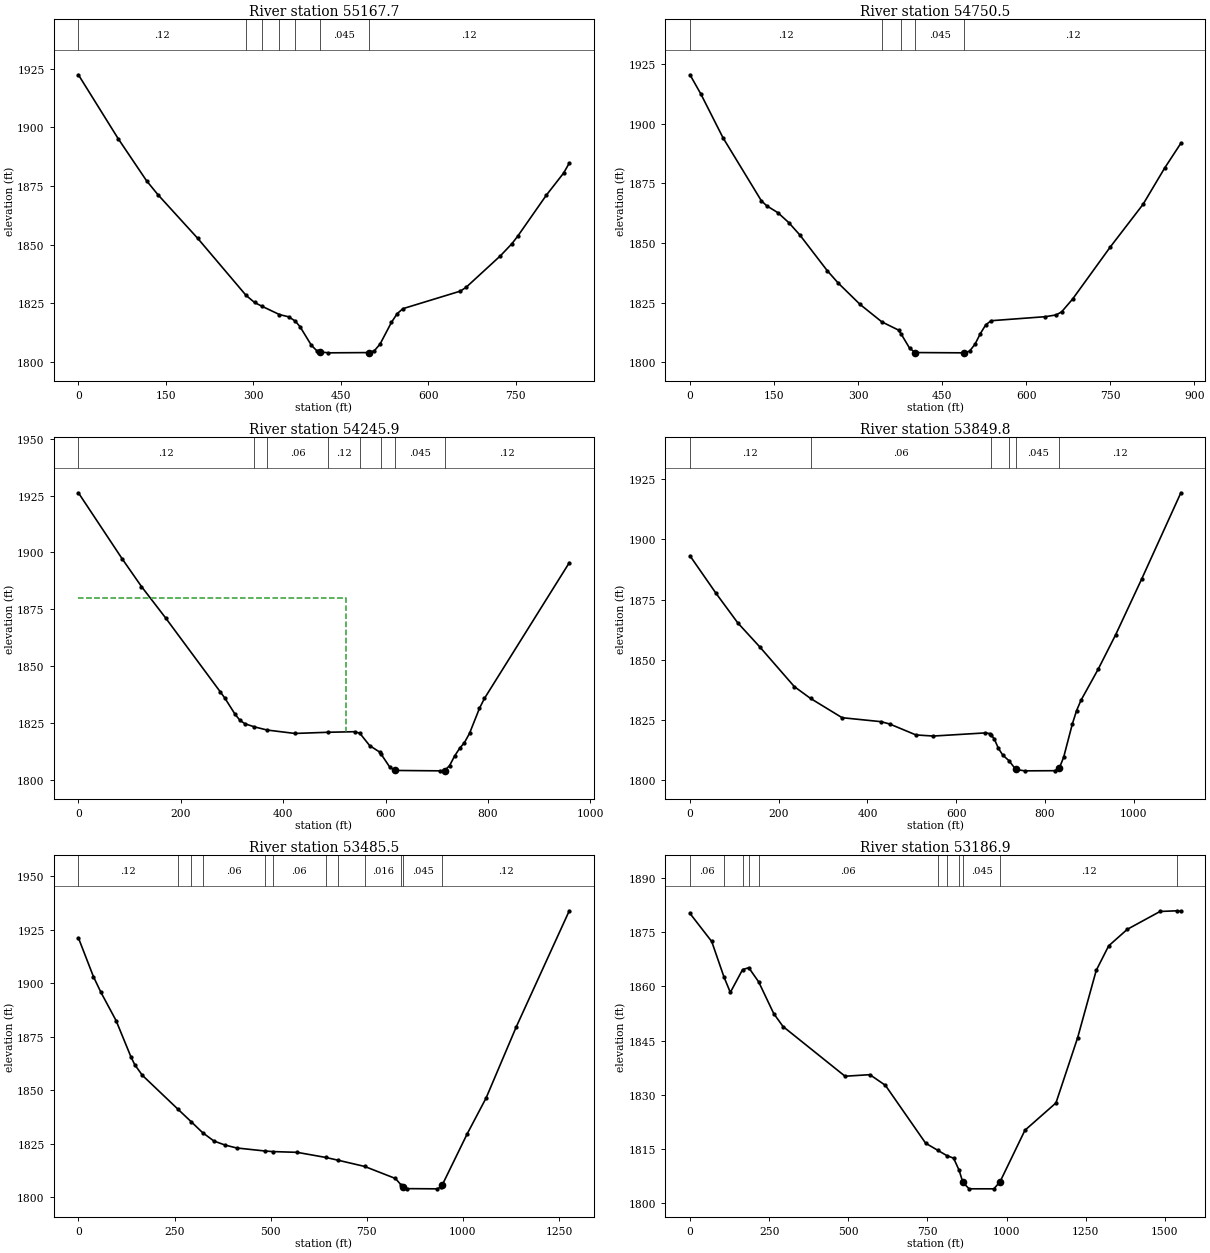
Type RM Length L Ch R = 1 ,55167.7 ,411.9,417.2,423.6
XS GIS Cut Line= 3
     1807828.718      171712.291     1808200.295      171479.375
     1808537.167      171257.722
#Sta/Elev= 30
       0 1922.41    68.2 1895.21   116.9 1877.26   136.4 1871.34   204.6 1852.75
  287.561828.445   302.1 1825.43  314.481823.856  344.691820.291   360.6 1819.32
  371.96  1817.5   380.1  1815.1   399.6 1807.18   409.3 1804.76  414.211804.391
   428.8 1803.98   497.6 1804.09   507.4 1804.85   517.2 1807.66   536.9 1816.99
   546.7 1820.67   556.6  1822.8   654.9 1830.26   664.8 1831.87   723.8 1845.33
   743.4 1850.46   753.3 1853.64   802.4 1871.11     832 1880.52   841.8  1884.8
#Mann= 7 ,-1 , 0
       0     .12       0  287.56     .06       0  314.48     .12       0
  344.69    .016       0  371.96     .12       0  414.21    .045       0
   497.6     .12       0
Bank Sta=414.21,497.6
XS Rating Curve= 0 ,0
Exp/Cntr=0.3,0.1

Type RM Length L Ch R = 1 ,54750.5 ,494.6,504.6,514
XS GIS Cut Line= 3
     1807964.409      172041.464      1808374.61      171855.604
     1808764.787      171686.141
#Sta/Elev= 30
       0 1920.44    19.6 1912.29    58.7 1894.14   127.3 1867.66   137.1 1865.52
   156.6  1862.7   176.2 1858.53   195.8 1853.38   244.8  1838.4   264.3 1833.22
   303.5 1824.22  342.341816.916     372 1813.49  376.781811.812   391.6 1805.98
   401.4 1804.08     489 1803.96   498.7 1804.65   508.4 1807.55     518 1812.02
   527.7 1815.73   537.4 1817.42     634 1819.11   653.4 1819.85     663 1821.15
   682.4 1826.44     750 1848.37   808.1 1866.13   846.7 1881.34   875.7 1891.76
#Mann= 5 ,-1 , 0
       0     .12       0  342.34    .016       0  376.78     .12       0
   401.4    .045       0     489     .12       0
Bank Sta=401.4,489
XS Rating Curve= 0 ,0
Exp/Cntr=0.3,0.1

Type RM Length L Ch R = 1 ,54245.9 ,393,396,399.1
XS GIS Cut Line= 3
     1807955.674      172319.203     1808157.241      172372.745
     1808897.825      172252.185
#Sta/Elev= 30
       0 1926.24    85.3 1897.27   123.2 1885.02   170.6 1871.14   276.8 1838.82
   286.5 1835.81     306 1828.86   315.8 1826.13   325.5 1824.66  343.761823.312
  368.631821.911   422.9 1820.41  487.651820.931   539.9 1821.18  549.751820.491
   569.1 1815.03   588.6 1812.22  591.291811.338   608.1 1805.65   617.8 1804.14
   705.5 1803.97   715.3 1804.11     725 1806.24   734.8 1810.44   744.5  1813.8
   754.2 1816.42     764 1820.43   783.5 1831.48   793.2 1835.82   958.9 1895.49
#Mann= 8 ,-1 , 0
       0     .12       0  343.76     .08       0  368.63     .06       0
  487.65     .12       0  549.75    .016       0  591.29     .12       0
   617.8    .045       0   715.3     .12       0
#XS Ineff= 2 , 0
          523.46  1879.8
Permanent Ineff=
       F       F
Bank Sta=617.8,715.3
XS Rating Curve= 0 ,0
Exp/Cntr=0.3,0.1

Type RM Length L Ch R = 1 ,53849.8 ,370.5,364.3,357.9
XS GIS Cut Line= 3
     1807913.919      172611.127     1808115.575       172732.12
     1808983.987      172662.248
#Sta/Elev= 30
       0 1893.23    58.8 1877.63   107.8 1865.37   156.8 1855.52   235.2 1838.93
  271.681834.037   342.8 1826.04     431 1824.38   450.5 1823.39   509.3 1818.88
   548.4 1818.42   665.9 1819.73   675.7 1819.43  678.371818.863   685.5 1817.35
   695.2  1813.3     705  1810.5   718.6 1808.25   734.4 1804.56     754 1803.98
   822.5 1804.04   832.3  1805.1   842.1 1809.56   861.7 1823.38   871.4 1829.02
   881.2 1833.24   920.4  1846.3   959.6 1860.54  1018.3 1883.69  1106.4 1919.39
#Mann= 6 ,-1 , 0
       0     .12       0  271.68     .06       0  678.37    .016       0
   718.6     .12       0   734.4    .045       0   832.3     .12       0
Bank Sta=734.4,832.3
XS Rating Curve= 0 ,0
Exp/Cntr=0.3,0.1

Type RM Length L Ch R = 1 ,53485.5 ,302.7,298.6,294.1
XS GIS Cut Line= 3
     1807806.966      173261.165     1808084.325       173200.87
     1809047.103      172957.744
#Sta/Elev= 30
       0 1921.21    39.2 1903.04    58.7 1895.71    97.9 1882.58     137 1865.46
   146.8 1861.87   166.4 1856.98  258.671841.192  292.791835.395  323.131830.182
   352.7 1826.26   382.2 1824.35   411.6 1823.04  486.141821.601  505.181821.354
     569 1820.99  643.531818.606  675.651817.302  744.381814.411   824.6 1808.78
  838.941805.856   844.2 1804.75   854.1 1804.04   932.7 1803.94   942.6 1804.73
  946.861805.921  1011.4 1829.67  1060.5  1846.4  1139.2 1879.73  1276.8 1933.85
#Mann= 12 ,-1 , 0
       0     .12       0  258.67     .08       0  292.79     .12       0
  323.13     .06       0  486.14     .08       0  505.18     .06       0
  643.53     .12       0  675.65     .06       0  744.38    .016       0
  838.94     .08       0   844.2    .045       0  946.86     .12       0
Bank Sta=844.2,946.86
XS Rating Curve= 0 ,0
Exp/Cntr=0.3,0.1

Type RM Length L Ch R = 1 ,53186.9 ,238.9,243.1,261.1
XS GIS Cut Line= 3
     1807836.645      173665.976     1809134.388      173192.885
     1809296.638      173144.302
#Sta/Elev= 30
       0 1880.14    68.6 1872.39  107.291862.587   127.4  1858.3  166.181864.618
  185.651865.135   216.91861.226   264.5 1852.45   293.9 1848.87   489.8 1835.12
   568.2 1835.55   617.2 1832.61   744.5 1816.58   782.71814.632  810.731813.188
   832.7 1812.45  849.911809.152   862.1 1805.73   881.7 1803.98     960 1803.97
   979.6 1805.96    1058 1820.17    1156 1827.73  1224.5 1845.77  1283.3 1864.41
  1322.5 1871.18  1381.3 1875.75  1484.8 1880.69 1539.241880.883  1550.6 1880.74
#Mann= 11 ,-1 , 0
       0     .06       0  107.29     .08       0  166.18    .016       0
  185.65     .08       0   216.9     .06       0   782.7     .08       0
  810.73    .016       0  849.91     .12       0   862.1    .045       0
   979.6     .12       0 1539.24     .08       0
Bank Sta=862.1,979.6
XS Rating Curve= 0 ,0
Exp/Cntr=0.3,0.1

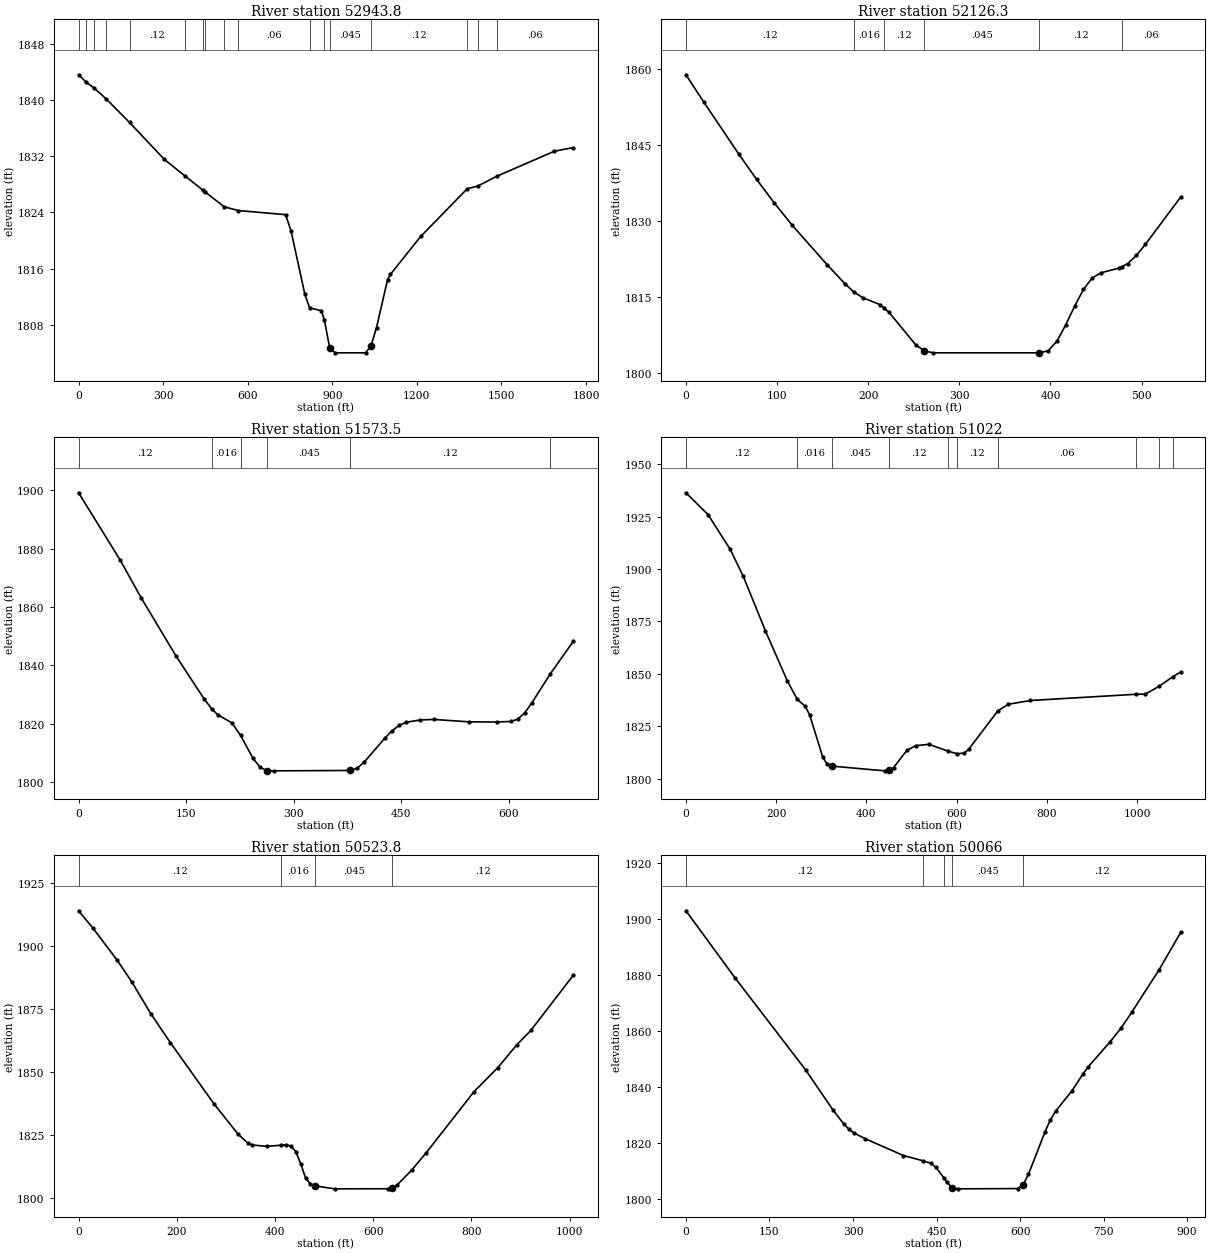
Type RM Length L Ch R = 1 ,52943.8 ,874.7,817.5,746.9
XS GIS Cut Line= 3
     1807927.791      173904.691     1809212.513      173401.219
     1809571.871      173293.614
#Sta/Elev= 30
       0 1843.62   27.181842.554   53.651841.769   96.581840.233  180.681836.821
   303.4 1831.59  377.921829.174  440.971827.172  448.381826.938   516.51824.796
  567.061824.264     734 1823.68   753.5 1821.38   802.5 1812.35  819.261810.388
   861.2 1809.99  872.241808.591   890.5 1804.73   910.1 1803.98  1017.8 1803.98
  1037.3 1804.97  1056.9 1807.59    1096 1814.43  1105.8 1815.15  1213.5 1820.57
 1378.25 1827.36 1417.191827.777 1482.961829.146  1687.6 1832.72    1755 1833.24
#Mann= 17 ,-1 , 0
       0     .12       0   27.18     .06       0   53.65     .12       0
   96.58     .06       0  180.68     .12       0  377.92     .06       0
  440.97     .12       0  448.38     .06       0   516.5     .08       0
  567.06     .06       0  819.26    .016       0  872.24     .12       0
   890.5    .045       0  1037.3     .12       0 1378.25     .08       0
 1417.19     .12       0 1482.96     .06       0
Bank Sta=890.5,1037.3
XS Rating Curve= 0 ,0
Exp/Cntr=0.3,0.1

Type RM Length L Ch R = 1 ,52126.3 ,556.1,552.8,549.5
XS GIS Cut Line= 2
     1809690.227      173815.453     1809596.477      173280.731
#Sta/Elev= 30
       0 1858.93    19.4 1853.59    58.2  1843.2    77.6 1838.25    96.9 1833.61
   116.3 1829.26   155.1 1821.36   174.5 1817.63  184.02 1816.04   193.9 1814.89
   213.3 1813.49  217.441812.837     223 1811.96     252 1805.59   261.7 1804.35
   271.4 1803.98   387.8 1803.98   397.5 1804.38   407.2  1806.3   416.8 1809.53
   426.6  1813.2   436.2 1816.52   445.9 1818.79   455.6 1819.81     475 1820.71
  478.361821.022   484.7 1821.61   494.4 1823.24   504.1 1825.41   542.9 1834.76
#Mann= 6 ,-1 , 0
       0     .12       0  184.02    .016       0  217.44     .12       0
   261.7    .045       0   387.8     .12       0  478.36     .06       0
Bank Sta=261.7,387.8
XS Rating Curve= 0 ,0
Exp/Cntr=0.3,0.1

Type RM Length L Ch R = 1 ,51573.5 ,543,551.5,560
XS GIS Cut Line= 2
     1810273.561      173780.731     1810096.477      173114.064
#Sta/Elev= 30
       0 1899.21    58.3 1875.99    87.4 1863.12     136 1843.16   174.9 1828.56
  186.251824.902   194.3 1823.06   213.7  1820.3  225.881816.014   242.9 1808.27
   252.6 1805.19   262.3 1803.89     272 1803.86   378.9 1803.99   388.6  1804.8
   398.3 1806.88   427.5 1815.23   437.2 1817.62   446.9 1819.45   456.6 1820.51
     476  1821.3   495.5 1821.48   544.1 1820.67   582.9  1820.6   602.4 1820.79
   612.1 1821.56   621.8  1823.7   631.5 1826.99  657.621837.111   689.8  1848.3
#Mann= 6 ,-1 , 0
       0     .12       0  186.25    .016       0  225.88     .12       0
   262.3    .045       0   378.9     .12       0  657.62     .06       0
Bank Sta=262.3,378.9
XS Rating Curve= 0 ,0
Exp/Cntr=0.3,0.1

Type RM Length L Ch R = 1 ,51022   ,470.8,498.3,525.7
XS GIS Cut Line= 2
     1810745.783      173808.509     1810708.127      172712.271
#Sta/Elev= 30
       0 1936.38      49 1925.97    97.9  1909.5   127.3 1896.43   176.3 1870.46
   225.2 1846.42  247.171837.742   264.4 1834.52   274.2 1830.46   303.6 1810.06
   313.4 1806.79   323.2 1805.95   440.7 1803.69   450.5 1803.94   460.3 1805.22
   489.7 1813.43   509.3  1815.7   538.6 1816.34  582.021813.034  601.061811.872
     617 1812.16   626.8 1813.94  691.361832.251   714.9 1835.48   763.9 1837.26
  998.341840.231  1018.5  1840.3 1049.281844.065 1079.53 1848.61  1096.9 1850.83
#Mann= 10 ,-1 , 0
       0     .12       0  247.17    .016       0   323.2    .045       0
   450.5     .12       0  582.02     .06       0  601.06     .12       0
  691.36     .06       0  998.34     .08       0 1049.28     .06       0
 1079.53     .12       0
Bank Sta=323.2,450.5
XS Rating Curve= 0 ,0
Exp/Cntr=0.3,0.1

Type RM Length L Ch R = 1 ,50523.8 ,433.7,457.8,481.9
XS GIS Cut Line= 3
     1810856.894       173857.12     1811346.477      173266.842
     1811575.343      173192.865
#Sta/Elev= 30
       0 1914.09    29.5 1907.12    78.7 1894.41   108.2 1885.88   147.5 1873.04
   186.8  1861.7   275.3 1837.46   324.4 1825.39   344.1 1821.82     354    1821
   383.4 1820.46  412.711820.925   422.8 1821.12   432.6 1820.53   442.4 1818.37
   452.3 1813.52   462.1 1807.92   471.9 1805.53   481.8 1804.77   521.1 1803.58
   629.2 1803.62   639.1    1804   648.9  1805.2   678.4 1811.05   707.9 1817.95
   805.4 1842.26   853.5 1851.72     892 1860.77   920.8 1866.52  1007.4  1888.5
#Mann= 4 ,-1 , 0
       0     .12       0  412.71    .016       0   481.8    .045       0
   639.1     .12       0
Bank Sta=481.8,639.1
XS Rating Curve= 0 ,0
Exp/Cntr=0.3,0.1

Type RM Length L Ch R = 1 ,50066   ,364.9,369.2,373.5
XS GIS Cut Line= 2
      1810912.45       173919.62      1811776.04      173710.967
#Sta/Elev= 30
       0 1902.89    87.9    1879   214.8 1846.08   263.6 1831.86   283.1 1826.79
   292.9 1824.82   302.7 1823.41   322.2 1821.43   390.5 1815.46  426.42 1813.53
   439.3 1812.72   449.1 1811.18  463.261807.433   468.6 1805.93   478.4  1803.9
   488.2 1803.55   595.6 1803.65   605.3 1804.97   615.1 1808.75   644.4 1823.73
   654.1  1828.1   663.9 1831.32   693.2 1838.58   712.7 1844.51   722.5 1847.18
   761.5 1856.04     781 1860.89   800.6 1866.66   849.4 1881.74   888.4 1895.16
#Mann= 5 ,-1 , 0
       0     .12       0  426.42    .016       0  463.26     .12       0
   478.4    .045       0   605.3     .12       0
Bank Sta=478.4,605.3
XS Rating Curve= 0 ,0
Exp/Cntr=0.3,0.1

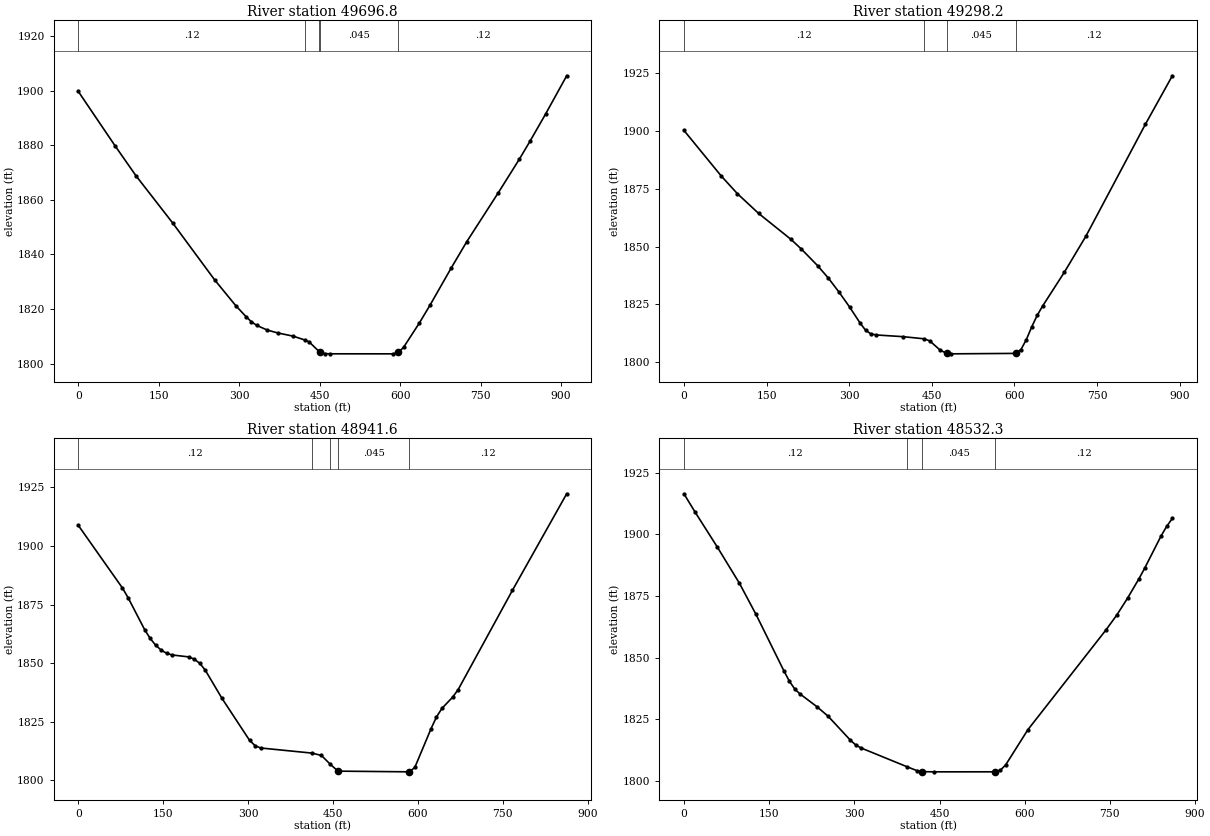
Type RM Length L Ch R = 1 ,49696.8 ,394.5,398.5,402.6
XS GIS Cut Line= 3
     1810948.383      174225.852     1811491.727      174158.534
     1811851.816       174113.92
#Sta/Elev= 30
       0  1899.8    68.4  1879.9   107.5 1868.88     176 1851.54   254.2 1830.68
   293.3 1821.29   312.9 1817.16   322.6 1815.35   332.4 1814.03     352  1812.3
   371.5 1811.25   400.8 1810.04  422.361808.632   430.2 1807.96  448.821804.432
   449.7 1804.26   459.5 1803.65   469.3 1803.58   586.7 1803.57   596.5 1804.07
   606.3 1805.96   635.8 1814.91   655.4 1821.36   694.6 1834.89     724 1844.68
   782.9 1862.66   822.1 1874.96   841.7 1881.46   871.1 1891.55   910.3 1905.53
#Mann= 5 ,-1 , 0
       0     .12       0  422.36    .016       0  448.82     .12       0
   449.7    .045       0   596.5     .12       0
Bank Sta=449.7,596.5
XS Rating Curve= 0 ,0
Exp/Cntr=0.3,0.1

Type RM Length L Ch R = 1 ,49298.2 ,353.5,356.6,360.3
XS GIS Cut Line= 3
     1810975.519      174564.835     1811518.749      174555.854
     1811862.178      174550.176
#Sta/Elev= 30
       0 1900.26    67.9 1880.49      97  1872.9   135.8  1864.3     194 1853.18
   213.4 1848.89   242.6 1841.76     262 1836.43   281.4 1830.36   300.8 1823.85
   320.2  1816.8   329.9 1813.78   339.6 1812.19   349.3 1811.75   397.8 1811.01
  436.031810.089   446.3 1809.19   465.7 1805.09  477.531803.783   485.1 1803.58
   602.2 1803.77     612 1805.45   621.8 1809.76   631.6 1815.29   641.4  1820.2
   651.2 1824.24   690.5 1838.79   729.8 1854.44   837.7 1902.82   886.8 1923.88
#Mann= 4 ,-1 , 0
       0     .12       0  436.03    .016       0  477.53    .045       0
   602.2     .12       0
Bank Sta=477.53,602.2
XS Rating Curve= 0 ,0
Exp/Cntr=0.3,0.1

Type RM Length L Ch R = 1 ,48941.6 ,405.8,409.3,412.3
XS GIS Cut Line= 3
     1810989.803      174877.043      1811525.49      174912.704
     1811850.164      174939.759
#Sta/Elev= 30
       0 1908.82    78.1 1882.03    87.8    1878   117.1 1864.33   126.9 1860.54
   136.7 1857.62   146.4 1855.53   156.2 1854.15   165.9 1853.45   195.2 1852.63
     205 1851.64   214.8 1849.84   224.5 1846.89   253.8 1834.93   302.6 1816.98
   312.4 1814.69   322.1 1813.73  413.071811.535   429.5 1810.54  445.51 1806.68
   458.8 1803.84   584.8 1803.54   594.4  1805.4   623.1 1821.96   632.7 1826.96
   642.3 1830.63   661.4 1835.47     671 1838.67   766.8 1881.04   862.7  1922.3
#Mann= 5 ,-1 , 0
       0     .12       0  413.07    .016       0  445.51     .12       0
   458.8    .045       0   584.8     .12       0
Bank Sta=458.8,584.8
XS Rating Curve= 0 ,0
Exp/Cntr=0.3,0.1

Type RM Length L Ch R = 1 ,48532.3 ,426.4,425.7,425
XS GIS Cut Line= 3
     1810987.873      175238.439     1811469.939      175316.323
     1811836.725      175375.581
#Sta/Elev= 30
       0 1916.54    19.5 1909.17    58.6 1894.97    97.7  1880.2     127  1867.5
   175.8 1844.71   185.6 1840.43   195.3 1837.17   205.1  1835.1   234.4 1830.01
   253.9 1826.17     293 1816.46   302.8 1814.44   312.5 1813.22  391.951805.729
   410.2 1804.07     420 1803.66   439.5 1803.58     547 1803.59   556.8 1804.14
   566.5  1806.4   605.6  1820.7   742.5 1861.06   762.1 1867.26   781.6 1874.34
   801.2 1882.04     811 1886.21   840.3  1899.5   850.1 1903.34   859.9 1906.52
#Mann= 4 ,-1 , 0
       0     .12       0  391.95    .016       0     420    .045       0
     547     .12       0
Bank Sta=420,547
XS Rating Curve= 0 ,0
Exp/Cntr=0.3,0.1