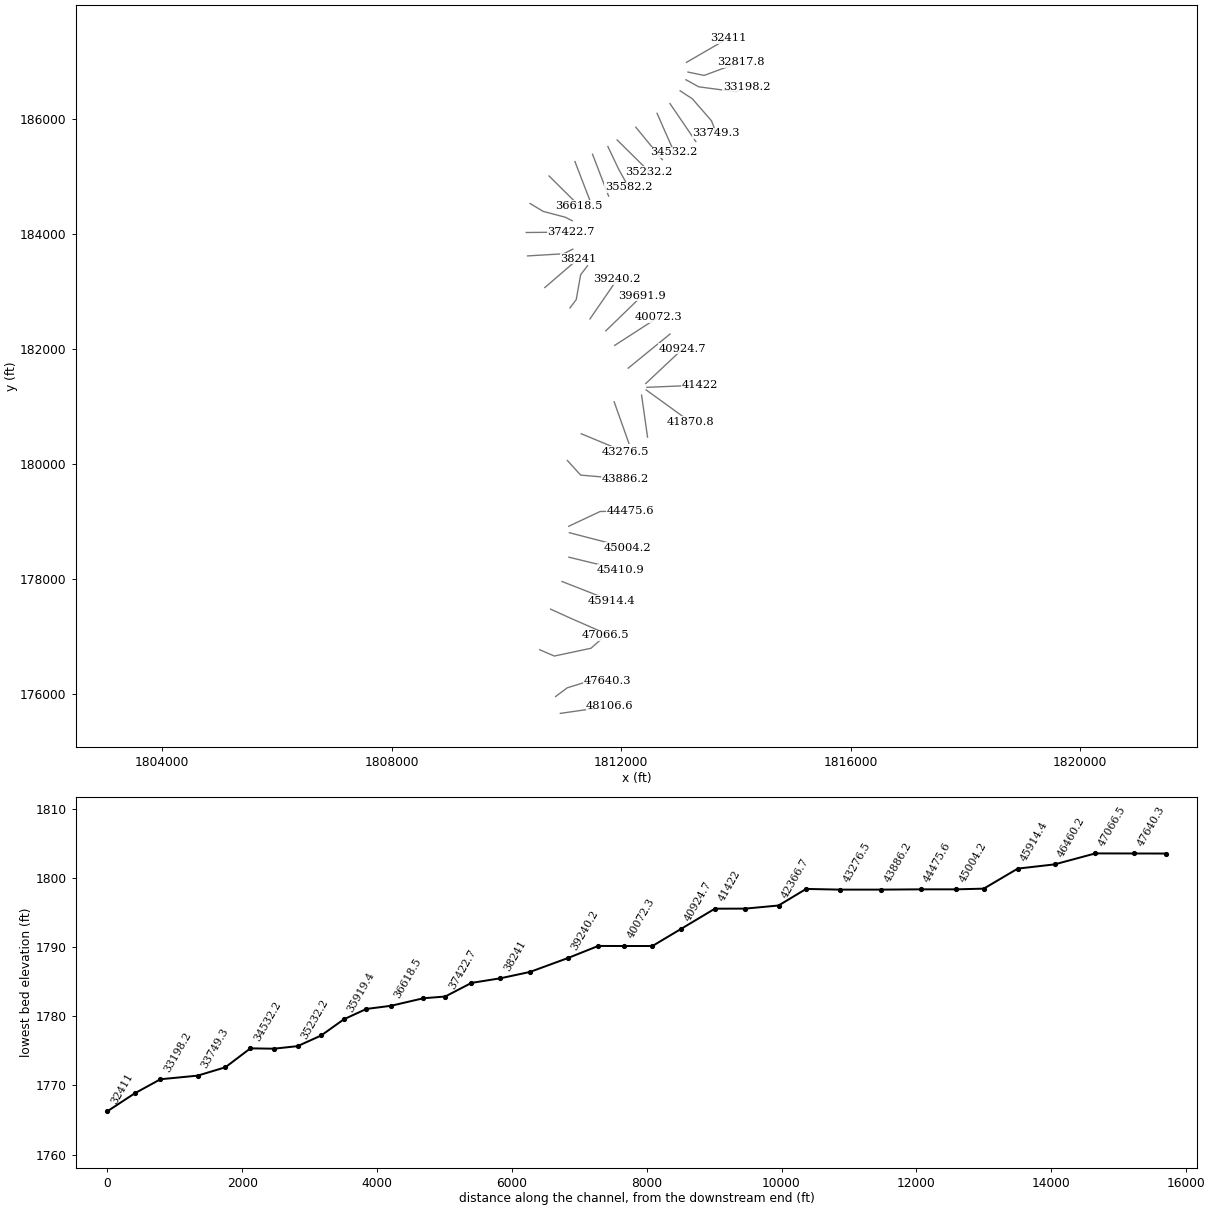
HEC-RAS study MIDFKRV2.prj: MIDFKRV2

--- MIDFKRV2.g01 (geometry) --- (continued)

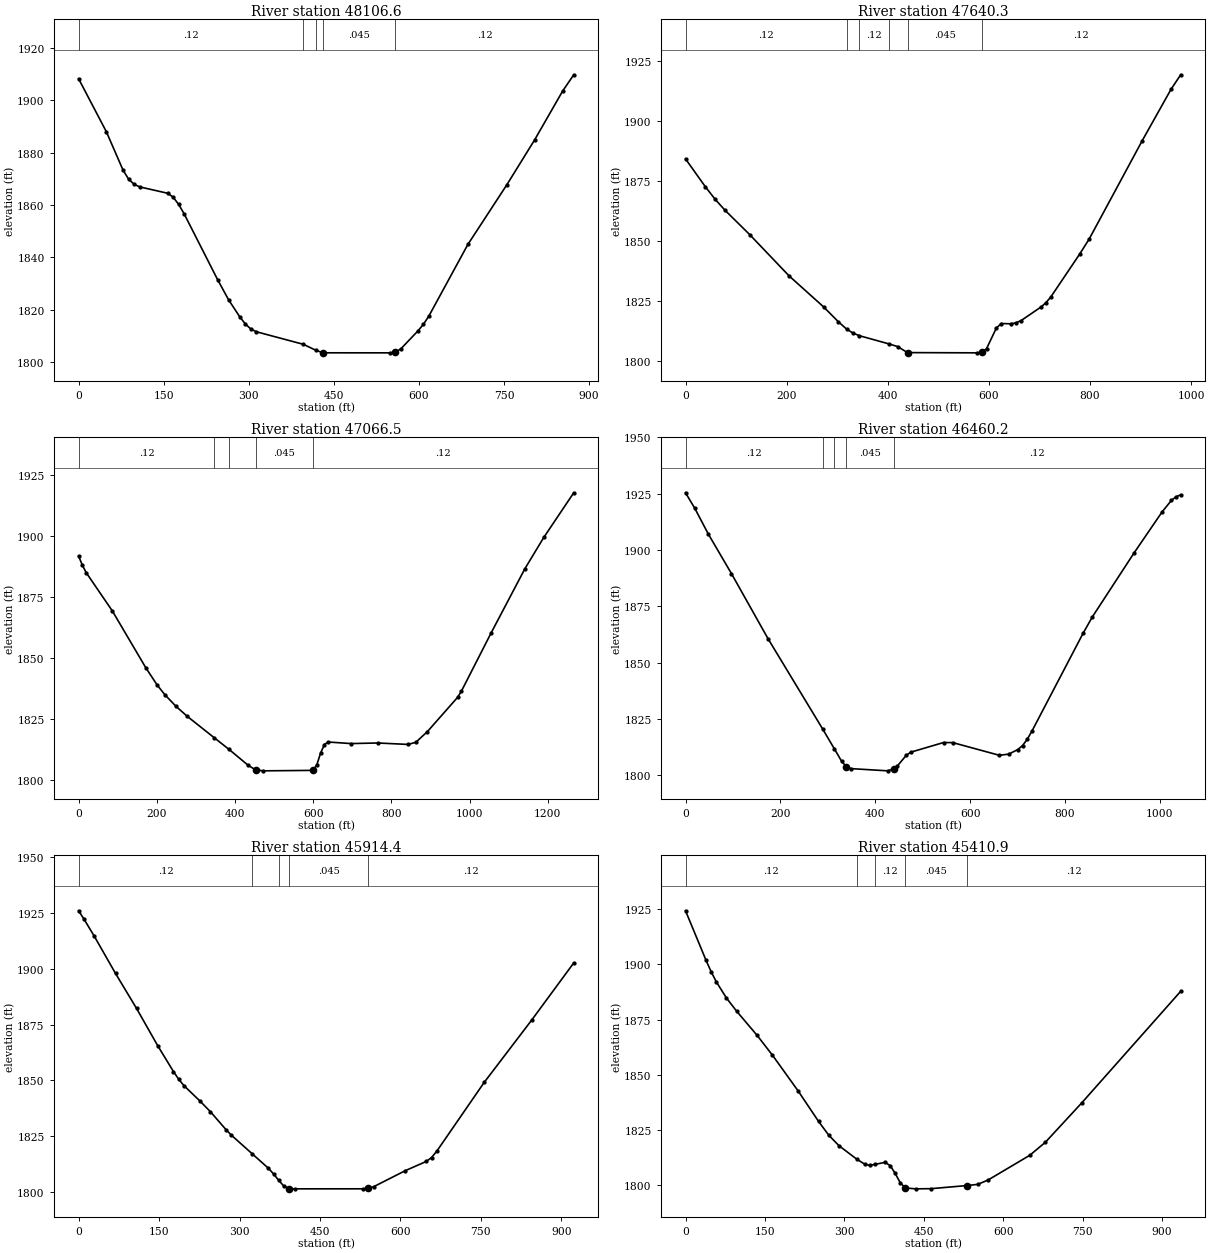
Type RM Length L Ch R = 1 ,48106.6 ,460.4,466.3,472.2
XS GIS Cut Line= 3
     1810940.914      175670.458     1811425.871      175739.849
     1811805.065      175794.106
#Sta/Elev= 30
       0 1908.16      49 1887.91    78.4 1873.26    88.2 1869.83      98 1867.87
   107.8 1866.89   156.8 1864.47   166.6    1863   176.4 1860.21   186.2 1856.56
     245 1831.52   264.5 1823.78   284.1 1817.32   293.9 1814.59   303.7 1812.65
   313.5  1811.6   396.51806.799  418.181804.542   431.1 1803.57   548.8 1803.56
   558.6 1803.77   568.5 1805.16   597.9 1811.84   607.8 1814.39   617.6 1817.61
   686.3 1844.91   755.1 1867.72   804.2 1884.89   853.3 1903.42     873 1909.68
#Mann= 5 ,-1 , 0
       0     .12       0   396.5    .016       0  418.18     .12       0
   431.1    .045       0   558.6     .12       0
Bank Sta=431.1,558.6
XS Rating Curve= 0 ,0
Exp/Cntr=0.3,0.1

Type RM Length L Ch R = 1 ,47640.3 ,577.1,573.8,570.3
XS GIS Cut Line= 4
     1810858.237      175963.159     1811061.596      176114.579
     1811509.672      176252.953     1811766.441      176240.428
#Sta/Elev= 30
       0 1884.35      39 1872.82    58.5 1867.55      78 1862.99   126.8 1852.86
   204.8 1835.64   273.1 1822.72   302.4 1816.52  318.631813.469   331.7 1811.76
   344.1  1810.7  402.011807.321   419.6 1806.18   439.2 1803.67     576 1803.57
   585.7 1803.74   595.5 1805.29     615 1813.92   624.8 1815.78   644.3 1815.67
   654.1 1816.11   663.9 1817.01     703 1822.62   712.7 1824.39   722.5 1826.78
   779.6 1844.65   798.7 1851.01   903.4  1891.9   960.5 1913.34   979.6  1919.4
#Mann= 6 ,-1 , 0
       0     .12       0  318.63     .06       0   344.1     .12       0
  402.01    .016       0   439.2    .045       0   585.7     .12       0
Bank Sta=439.2,585.7
XS Rating Curve= 0 ,0
Exp/Cntr=0.3,0.1

Type RM Length L Ch R = 1 ,47066.5 ,629.8,606.3,583
XS GIS Cut Line= 4
     1810580.638       176775.32     1810836.061      176666.148
      1811474.95      176801.564     1811726.552      177023.758
#Sta/Elev= 30
       0 1891.61     9.6 1887.93    19.2  1884.9    86.2 1869.17   172.4 1845.71
   201.2 1838.72   220.3 1834.85     249 1830.05   277.8 1825.94  347.01 1817.14
  384.371812.428   433.7 1805.85   453.2 1803.93   472.7 1803.58   599.4 1803.77
   609.2 1805.98   618.9 1810.83   628.7 1814.36   638.4  1815.4   696.9 1814.76
   765.2    1815   843.1 1814.41   862.6 1815.29   891.9 1819.62   969.2 1833.68
   978.8 1836.14  1055.5 1860.23  1141.8 1886.53  1189.8 1899.27  1266.5  1917.6
#Mann= 5 ,-1 , 0
       0     .12       0  347.01    .016       0  384.37     .12       0
   453.2    .045       0   599.4     .12       0
Bank Sta=453.2,599.4
XS Rating Curve= 0 ,0
Exp/Cntr=0.3,0.1

Type RM Length L Ch R = 1 ,46460.2 ,544.2,545.8,547.4
XS GIS Cut Line= 3
     1810770.861      177480.582     1811114.679        177324.8
     1811725.562      177058.153
#Sta/Elev= 30
       0 1925.41    19.4 1918.56    48.4 1906.96    96.8 1889.55   174.2 1860.55
  288.94 1820.63  313.891811.738   329.1 1806.24   338.8 1803.88   348.4 1802.98
   426.5 1801.99  439.241802.872   446.1 1804.02   465.7 1808.94   475.5 1810.31
   544.1 1814.56   563.7 1814.51   661.7 1808.89   681.3  1809.4   700.9 1811.46
   710.7 1813.23   720.5    1816   730.3 1819.58   838.2 1863.02   857.8 1870.32
     946 1898.79  1004.8  1916.9  1024.4    1922  1034.2 1923.63    1044 1924.51
#Mann= 5 ,-1 , 0
       0     .12       0  288.94    .016       0  313.89     .12       0
   338.8    .045       0  439.24     .12       0
Bank Sta=338.8,439.24
XS Rating Curve= 0 ,0
Exp/Cntr=0.3,0.1

Type RM Length L Ch R = 1 ,45914.4 ,498.4,503.5,508.4
XS GIS Cut Line= 2
     1810970.527      177960.336     1811830.745      177625.132
#Sta/Elev= 30
       0 1926.02     9.8 1922.37    29.5  1914.5    68.8 1897.94     108 1882.26
   147.3 1865.62   176.8 1853.97   186.6 1850.52   196.4 1847.63   225.9 1840.84
   245.5 1836.02     275 1827.87   284.8 1825.44  324.221816.975   353.6 1810.67
   363.4 1808.09  372.781805.295     383 1802.51   392.9 1801.44   402.7 1801.38
   530.4 1801.39  539.331801.563     550 1802.32   608.9  1809.5   648.2 1813.66
     658  1815.4   667.9 1818.28   756.3 1849.12   844.6 1876.96   923.2 1902.65
#Mann= 5 ,-1 , 0
       0     .12       0  324.22    .016       0  372.78     .12       0
   392.9    .045       0  539.33     .12       0
Bank Sta=392.9,539.33
XS Rating Curve= 0 ,0
Exp/Cntr=0.3,0.1

Type RM Length L Ch R = 1 ,45410.9 ,407.2,406.7,406
XS GIS Cut Line= 3
     1811089.886      178382.691     1811559.393       178269.02
     1811998.813      178162.634
#Sta/Elev= 30
       0 1924.27    38.6 1901.94    48.3 1896.75      58 1892.19    77.3 1884.81
    96.6 1878.82   135.3 1867.88   164.2 1858.94   212.6  1842.8   251.2 1829.01
   270.5 1822.76   289.8    1818   323.71811.857   338.2 1809.68   347.8  1809.1
  357.561809.515   376.8 1810.47   386.5    1809   396.1 1805.43   405.8 1801.14
   415.4 1798.88   434.8 1798.48   463.8 1798.56   532.2 1799.98   551.9  1800.5
   571.5 1802.48   650.2 1813.65   679.6 1819.53   748.4 1837.37   935.2 1887.82
#Mann= 5 ,-1 , 0
       0     .12       0   323.7    .016       0  357.56     .12       0
   415.4    .045       0   532.2     .12       0
Bank Sta=415.4,532.2
XS Rating Curve= 0 ,0
Exp/Cntr=0.3,0.1

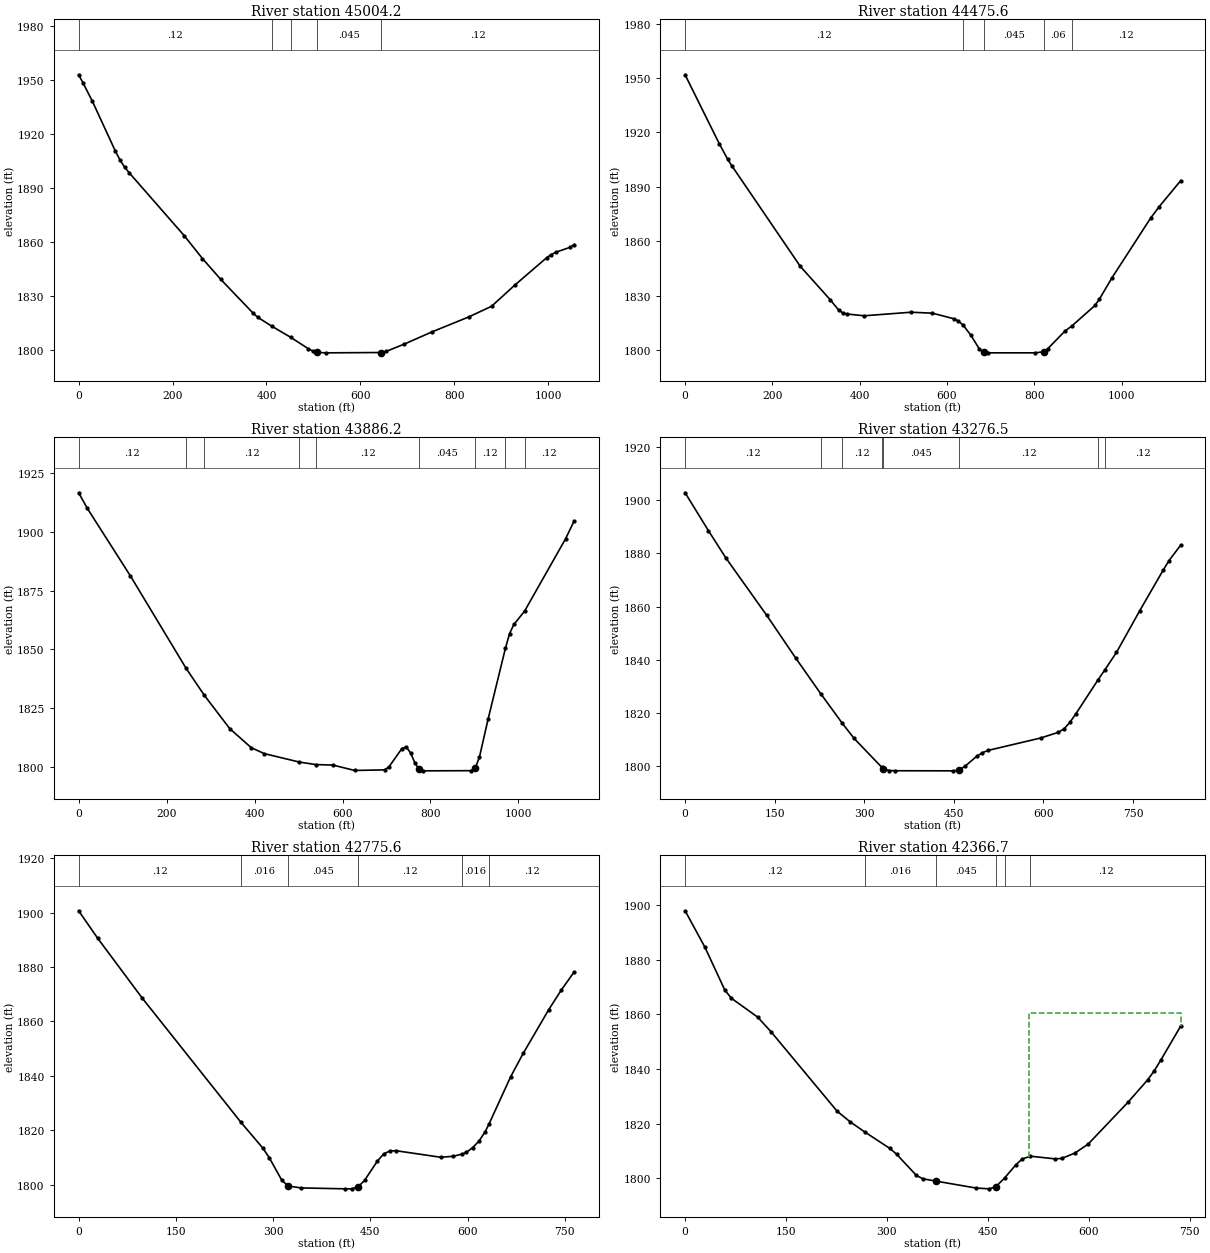
Type RM Length L Ch R = 1 ,45004.2 ,518.6,528.7,538.8
XS GIS Cut Line= 2
     1811097.845      178808.164      1812119.48      178543.404
#Sta/Elev= 30
       0 1953.07     9.8 1948.36    29.3 1938.32    78.2 1910.64      88 1905.72
    97.7 1901.77   107.5 1898.62   224.8 1863.59   263.8  1850.8   302.9 1839.19
   371.3 1820.53   381.1 1818.23   411.7 1813.15  451.641807.015   488.6 1800.77
   498.4 1799.36   508.2 1798.58   527.7 1798.38     645 1798.56   654.7 1799.16
   693.8 1803.26   752.4 1810.02   830.6 1818.32   879.5 1824.29   928.4 1835.93
   996.8  1851.3  1006.5 1853.02  1016.3 1854.33  1045.6    1857  1055.4 1858.54
#Mann= 5 ,-1 , 0
       0     .12       0   411.7    .016       0  451.64     .12       0
   508.2    .045       0     645     .12       0
Bank Sta=508.2,645
XS Rating Curve= 0 ,0
Exp/Cntr=0.3,0.1

Type RM Length L Ch R = 1 ,44475.6 ,593.4,589.4,585.4
XS GIS Cut Line= 3
     1811086.061       178919.62     1811634.672      179176.564
     1812164.312      179184.059
#Sta/Elev= 30
       0 1951.73    78.2 1913.76    97.7 1905.07   107.5  1901.4   263.8 1846.13
   332.2 1827.75   351.8    1822   361.5 1820.39   371.3 1819.79   410.4 1818.82
   517.9 1820.78   566.7 1820.26   615.6 1817.19   625.4 1816.06  636.681813.802
   654.8  1808.1   674.5  1800.4   684.3 1798.62   694.1 1798.38     802 1798.38
   821.6 1798.96   831.4 1800.76   870.6 1810.43  886.021813.149   939.3 1824.52
   949.1 1827.92   978.6 1839.92  1066.8 1872.72  1086.4 1879.01  1135.5  1893.3
#Mann= 5 ,-1 , 0
       0     .12       0  636.68    .016       0   684.3    .045       0
   821.6     .06       0  886.02     .12       0
Bank Sta=684.3,821.6
XS Rating Curve= 0 ,0
Exp/Cntr=0.3,0.1

Type RM Length L Ch R = 1 ,43886.2 ,621.4,609.7,597
XS GIS Cut Line= 3
     1811063.369      180062.637     1811294.394      179808.509
     1812074.774      179741.285
#Sta/Elev= 30
       0 1916.65    19.6 1910.07   117.8 1881.25  244.421841.936  285.841830.471
   343.4 1816.34   392.4  1808.2   421.8 1805.68  501.381802.094  539.33    1801
   578.4 1800.79   627.4  1798.5   695.9 1798.75   705.7 1800.07   735.1 1807.83
   744.9 1808.53   754.7 1805.98   764.4 1801.79   774.2 1798.92     784 1798.34
   891.7 1798.41   901.5 1799.39   911.3 1804.17   930.9 1820.29  970.331850.443
   979.8 1856.75   989.6 1860.61 1014.051866.325  1107.1 1897.06  1126.7 1904.67
#Mann= 9 ,-1 , 0
       0     .12       0  244.42    .016       0  285.84     .12       0
  501.38    .016       0  539.33     .12       0   774.2    .045       0
   901.5     .12       0  970.33    .016       0 1014.05     .12       0
Bank Sta=774.2,901.5
XS Rating Curve= 0 ,0
Exp/Cntr=0.3,0.1

Type RM Length L Ch R = 1 ,43276.5 ,531.9,500.8,470
XS GIS Cut Line= 2
     1811305.051      180526.362     1812071.694      180209.411
#Sta/Elev= 30
       0 1902.81      39  1888.6    68.3 1878.31   136.6 1856.78   185.4 1840.64
  227.451827.202  263.211816.196     283  1810.5   329.41799.642   331.8 1799.12
   341.6 1798.45   351.4 1798.38     449 1798.34   458.7 1798.61   468.5 1800.04
     488 1803.77   497.8 1805.16   507.5 1806.03   595.3 1810.68   624.6 1812.79
   634.4 1814.11   644.1 1816.52   653.9 1819.67  691.351832.539  702.361836.159
   722.2 1842.84   761.3 1858.57   800.3 1873.73   810.1 1877.32   829.6 1883.12
#Mann= 8 ,-1 , 0
       0     .12       0  227.45    .016       0  263.21     .12       0
   329.4     .08       0   331.8    .045       0   458.7     .12       0
  691.35    .016       0  702.36     .12       0
Bank Sta=331.8,458.7
XS Rating Curve= 0 ,0
Exp/Cntr=0.3,0.1

Type RM Length L Ch R = 1 ,42775.6 ,416.5,408.9,401.3
XS GIS Cut Line= 2
     1811878.514      181081.305      1812135.65      180361.327
#Sta/Elev= 30
       0 1900.72    29.4 1890.61      98 1868.64  250.161822.986   284.2 1813.41
     294 1809.93   313.6 1801.54   323.4 1799.48     343 1798.78   411.7 1798.44
   421.5 1798.46   431.3 1799.22   441.1 1801.54   460.7 1808.58   470.5 1811.27
   480.3 1812.38   490.1 1812.45   558.7 1810.05   578.3 1810.44  591.281811.219
   597.9 1811.82   607.7 1813.58   617.5 1815.93   627.3 1819.49  633.391822.436
   666.5 1839.67   686.1 1848.38   725.3 1864.37   744.9 1871.65   764.5 1878.25
#Mann= 6 ,-1 , 0
       0     .12       0  250.16    .016       0   323.4    .045       0
   431.3     .12       0  591.28    .016       0  633.39     .12       0
Bank Sta=323.4,431.3
XS Rating Curve= 0 ,0
Exp/Cntr=0.3,0.1

Type RM Length L Ch R = 1 ,42366.7 ,465.1,495.9,526.6
XS GIS Cut Line= 2
     1812356.894      181197.398      1812460.68      180468.015
#Sta/Elev= 30
       0 1898.02    29.5 1884.65    58.9 1869.01    68.8 1865.94     108    1859
   127.7 1853.67   225.9 1824.54   245.6 1820.58  266.781816.957   304.5 1810.84
   314.3 1808.78   343.8 1800.96   353.6 1799.72   373.3 1798.86   432.2 1796.35
   451.9 1796.04   461.7 1796.76  474.961800.003   491.2 1804.71     501 1806.96
  513.341808.017   550.1 1807.03   559.9 1807.19   579.6 1809.17   599.2 1812.45
   658.2 1827.73   687.6 1835.99   697.4 1839.31   707.3 1843.28   736.7 1855.69
#Mann= 6 ,-1 , 0
       0     .12       0  266.78    .016       0   373.3    .045       0
   461.7     .12       0  474.96    .016       0  513.34     .12       0
#XS Ineff= 2 , 0
                          511.93         1860.55
Permanent Ineff=
       F       F
Bank Sta=373.3,461.7
XS Rating Curve= 0 ,0
Exp/Cntr=0.3,0.1

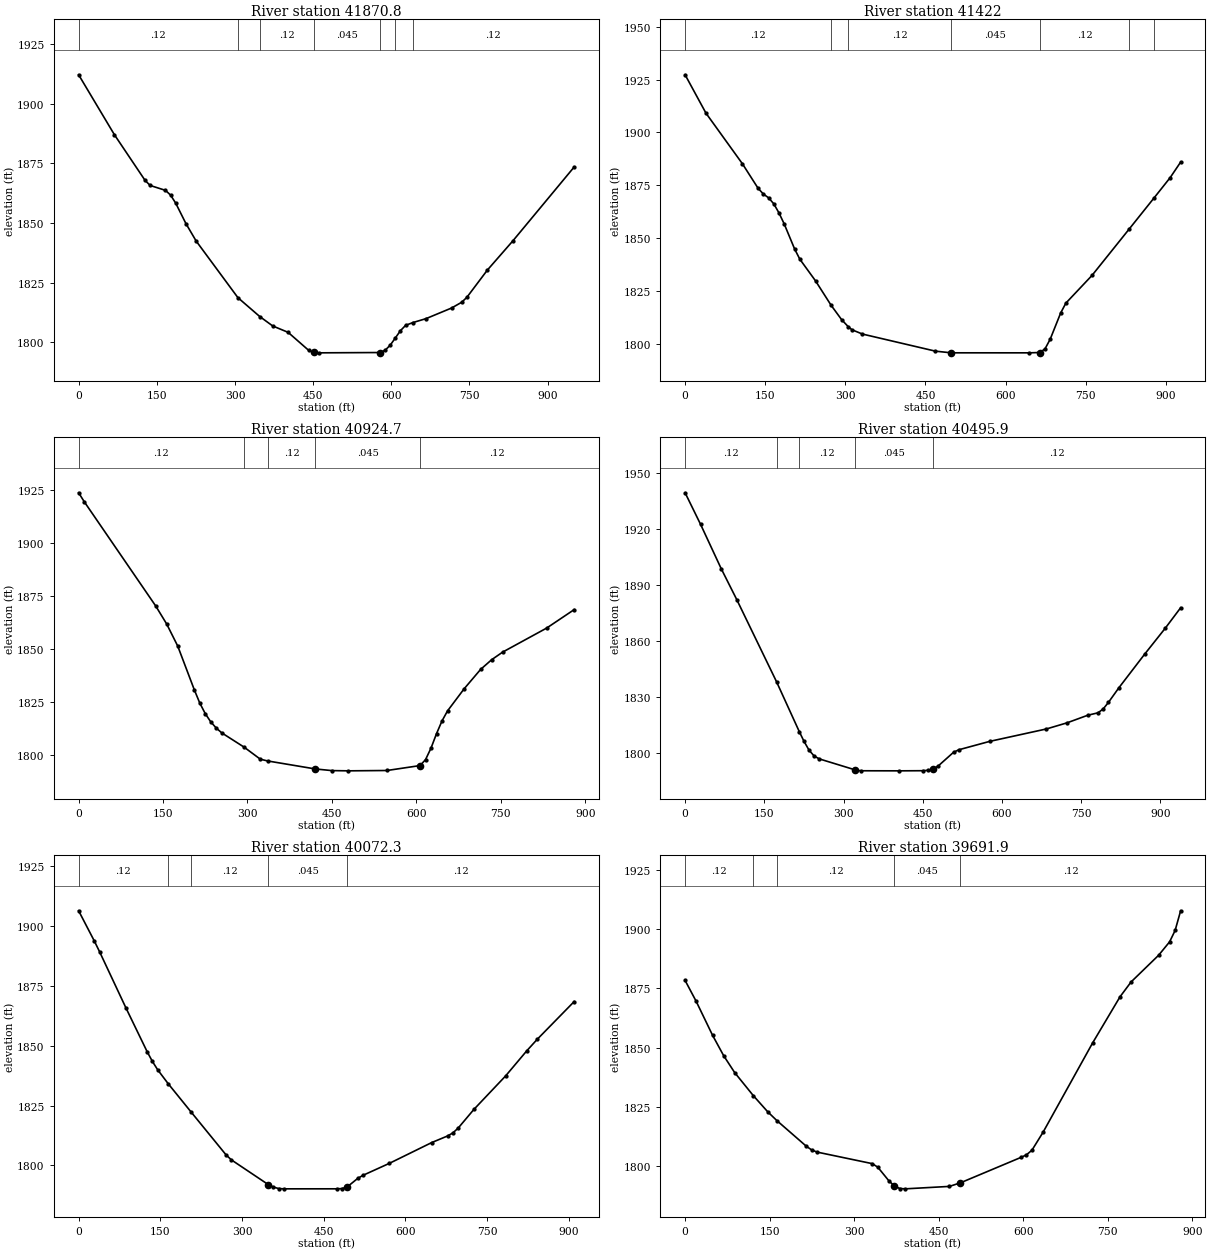
Type RM Length L Ch R = 1 ,41870.8 ,424.2,448.8,473.5
XS GIS Cut Line= 2
     1812436.755      181287.675     1813208.429      180731.809
#Sta/Elev= 30
       0 1912.05    68.6 1886.97   127.5 1867.82   137.3 1865.69   166.7 1863.64
   176.5 1861.64   186.3 1858.28   205.9 1849.73   225.5 1842.43  305.71 1818.69
  347.591810.796   372.6 1806.83     402 1804.18   441.2 1796.69     451 1795.74
   460.8 1795.59   578.5 1795.72   588.3 1796.68   598.1 1798.84  608.071801.903
   617.7  1804.9   627.5  1807.1  641.081808.241   666.7 1809.92   715.7 1814.36
   735.3  1816.8   745.1 1818.85   784.4 1830.25   833.4  1842.5     951 1873.43
#Mann= 7 ,-1 , 0
       0     .12       0  305.71    .016       0  347.59     .12       0
     451    .045       0   578.5     .12       0  608.07    .016       0
  641.08     .12       0
Bank Sta=451,578.5
XS Rating Curve= 0 ,0
Exp/Cntr=0.3,0.1

Type RM Length L Ch R = 1 ,41422   ,470.6,497.3,523.9
XS GIS Cut Line= 2
     1812450.644      181332.814     1813377.631      181371.709
#Sta/Elev= 30
       0 1927.31    39.1 1909.12   107.4 1885.12   136.7 1873.52   146.5 1870.82
   156.3 1869.03     166 1866.19   175.8 1861.86   185.6 1856.62   205.1 1844.75
   214.9 1839.91   244.2 1829.68  273.371818.111     293 1811.32  305.191808.037
   312.5  1806.5   332.1 1804.47   468.8 1796.37   498.1 1795.59   644.6 1795.58
   664.1 1795.74   673.9 1797.47   683.6 1802.06   703.2 1814.47   712.9 1819.13
   761.8 1832.24  831.481854.235  877.771868.887   908.3 1878.62   927.8 1885.94
#Mann= 7 ,-1 , 0
       0     .12       0  273.37    .016       0  305.19     .12       0
   498.1    .045       0   664.1     .12       0  831.48    .016       0
  877.77     .12       0
Bank Sta=498.1,664.1
XS Rating Curve= 0 ,0
Exp/Cntr=0.3,0.1

Type RM Length L Ch R = 1 ,40924.7 ,431.3,428.8,426.2
XS GIS Cut Line= 2
     1812429.811      181398.786     1813072.619       182000.43
#Sta/Elev= 30
       0 1923.55     9.8 1919.41     137 1870.25   156.5 1861.76   176.1 1851.38
   205.4  1830.9   215.2  1824.6     225 1819.59   234.8 1815.71   244.6 1812.79
   254.4 1810.53  293.99 1803.83   322.8 1798.16  335.571797.342   420.7 1793.56
     450 1792.79   479.4 1792.68   547.8 1792.84   606.5 1795.16   616.3 1797.94
   626.1  1803.4   635.9 1810.22   645.7 1816.23   655.4 1820.89   684.8 1831.26
   714.1  1840.4   733.7 1844.96   753.3 1848.56   831.5 1859.87   880.4 1868.56
#Mann= 5 ,-1 , 0
       0     .12       0  293.99    .016       0  335.57     .12       0
   420.7    .045       0   606.5     .12       0
Bank Sta=420.7,606.5
XS Rating Curve= 0 ,0
Exp/Cntr=0.3,0.1

Type RM Length L Ch R = 1 ,40495.9 ,428.4,423.6,418.9
XS GIS Cut Line= 2
     1812124.255      181666.148     1812852.577      182258.103
#Sta/Elev= 30
       0 1939.37    29.3 1922.44    68.4 1898.64    97.8 1882.08   173.21837.974
  216.18 1811.27   224.9 1806.18   234.6 1801.33   244.4 1798.13   254.2 1796.58
   322.6 1790.65   332.4 1790.22     406 1790.18   449.7 1790.25   459.5 1790.45
   469.3 1791.16     479  1792.7   508.4 1800.13   518.2 1801.47   576.8 1805.98
   684.4 1812.66   723.5 1815.95   762.6 1820.01   782.1 1821.32   791.9 1823.42
   801.7 1826.88   821.2 1834.62   870.1 1852.69   909.2 1866.64   938.5 1877.68
#Mann= 5 ,-1 , 0
       0     .12       0   173.2    .016       0  216.18     .12       0
   322.6    .045       0   469.3     .12       0
Bank Sta=322.6,469.3
XS Rating Curve= 0 ,0
Exp/Cntr=0.3,0.1

Type RM Length L Ch R = 1 ,40072.3 ,373,380.4,387.7
XS GIS Cut Line= 3
     1811887.673      182060.679     1812253.702      182296.052
     1812652.982      182552.808
#Sta/Elev= 30
       0 1906.42      29  1893.7    38.7 1889.18      87 1865.75   125.7 1847.56
   135.4 1843.46   145.1 1839.97  164.191834.202  206.141822.403   270.8 1804.35
   280.4  1802.3   348.1 1791.98   357.8 1790.89   367.5  1790.3   377.2 1790.18
   473.9 1790.19   483.6 1790.29   493.3 1791.01   512.7 1794.59   522.4 1795.86
   570.8 1800.86   648.3 1809.52   677.4 1812.28   687.1 1813.55   696.8 1815.55
   725.8 1823.39   783.9 1837.35   822.7 1847.84   842.1  1852.7   909.9 1868.47
#Mann= 5 ,-1 , 0
       0     .12       0  164.19    .016       0  206.14     .12       0
   348.1    .045       0   493.3     .12       0
Bank Sta=348.1,493.3
XS Rating Curve= 0 ,0
Exp/Cntr=0.3,0.1

Type RM Length L Ch R = 1 ,39691.9 ,444.1,451.7,459.3
XS GIS Cut Line= 2
     1811733.333      182313.688        1812366.      182923.999
#Sta/Elev= 30
       0 1878.39    19.5 1869.62    48.8 1855.14    68.4 1846.55    87.9 1839.41
  120.87 1829.68   146.5 1822.82  162.641819.109   214.9 1808.25   224.6 1806.64
   234.4 1805.73   332.1 1800.85   341.9 1799.34   361.4 1793.62   371.2 1791.39
   380.9 1790.33   390.7 1790.19   468.8 1791.22   488.4 1792.73   595.8 1803.49
   605.6 1804.59   615.3 1806.54   634.9 1814.09   722.8 1851.88   771.6 1871.48
   791.2 1877.75     840 1889.04   859.5 1894.72   869.3 1899.54   879.1 1907.87
#Mann= 5 ,-1 , 0
       0     .12       0  120.87    .016       0  162.64     .12       0
   371.2    .045       0   488.4     .12       0
Bank Sta=371.2,488.4
XS Rating Curve= 0 ,0
Exp/Cntr=0.3,0.1

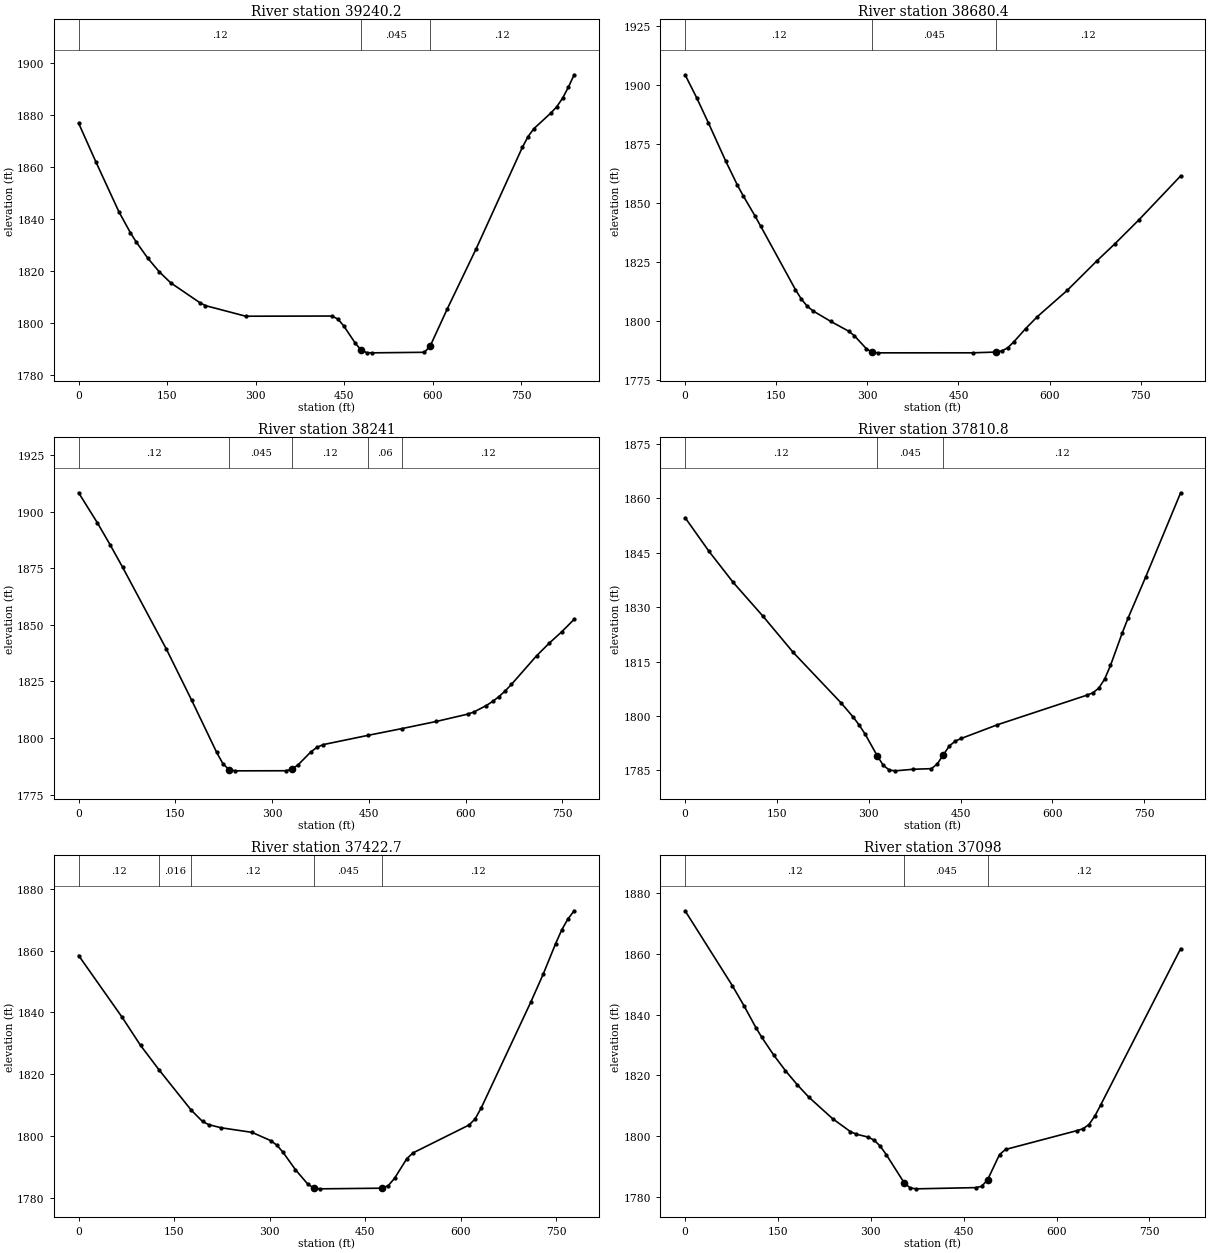
Type RM Length L Ch R = 1 ,39240.2 ,545.1,559.8,574.5
XS GIS Cut Line= 2
     1811456.792      182520.358     1811933.789      183211.181
#Sta/Elev= 30
       0 1876.77    29.3 1861.86    68.3 1842.67    87.8 1834.59    97.6 1831.07
   117.1 1824.86   136.7 1819.58   156.2 1815.33     205 1807.78   214.8  1806.6
   283.1 1802.52   429.5 1802.59   439.3 1801.39     449 1798.84   468.6 1792.16
   478.3 1789.56   488.1  1788.5   497.8 1788.43   585.7 1788.64   595.5 1791.01
   624.7 1805.42   673.6 1828.54   751.6 1867.43   761.4 1871.64   771.2 1874.66
   800.4 1880.77   810.2 1883.16     820 1886.45   829.7 1890.65   839.5  1895.4
#Mann= 3 ,-1 , 0
       0     .12       0   478.3    .045       0   595.5     .12       0
Bank Sta=478.3,595.5
XS Rating Curve= 0 ,0
Exp/Cntr=0.3,0.1

Type RM Length L Ch R = 1 ,38680.4 ,463.7,439.4,415.1
XS GIS Cut Line= 4
     1811108.769      182712.016     1811218.005       182857.12
     1811294.394      183287.675       1811414.4      183443.683
#Sta/Elev= 30
       0  1904.4    19.1 1894.63    38.2 1884.08    66.9 1867.78      86 1857.63
    95.6 1853.09   114.7 1844.67   124.3 1840.23   181.6 1813.27   191.3 1809.25
   201.1  1806.2   210.8 1804.18   239.9 1799.75   269.1 1795.63   278.8 1793.65
   298.2 1788.23     308  1786.6   317.7 1786.43   473.1 1786.44     512 1786.76
   521.7 1787.24   531.4 1788.66   541.2 1791.12   560.6 1796.72     580 1801.82
   628.8 1812.88     678 1825.49   707.5  1832.7   746.8 1842.79   815.7 1861.49
#Mann= 3 ,-1 , 0
       0     .12       0     308    .045       0     512     .12       0
Bank Sta=308,512
XS Rating Curve= 0 ,0
Exp/Cntr=0.3,0.1

Type RM Length L Ch R = 1 ,38241   ,454.8,430.2,405.8
XS GIS Cut Line= 2
     1810670.336      183065.764     1811253.705      183565.795
#Sta/Elev= 30
       0 1908.37    29.2 1895.04    48.6 1885.51    68.1 1875.51   136.2 1839.21
   175.1  1816.8     214 1793.68   223.7 1788.67   233.4 1785.96   243.2 1785.51
     321 1785.55   330.7  1786.2   340.4  1788.2   359.9 1793.83   369.6 1795.92
   379.3  1797.1  448.98 1801.21   501.81804.209   554.4 1807.32     603 1810.55
   612.7 1811.49   632.2 1814.38   641.9 1816.18   651.6 1818.28   661.4 1820.83
   671.1 1823.72     710 1836.34   729.4 1841.86   748.9 1846.91   768.3 1852.47
#Mann= 5 ,-1 , 0
       0     .12       0   233.4    .045       0   330.7     .12       0
  448.98     .06       0   501.8     .12       0
Bank Sta=233.4,330.7
XS Rating Curve= 0 ,0
Exp/Cntr=0.3,0.1

Type RM Length L Ch R = 1 ,37810.8 ,389.9,388.2,386.2
XS GIS Cut Line= 3
     1810368.839      183614.872     1810995.783      183652.259
     1811158.375      183732.765
#Sta/Elev= 30
       0 1854.68    39.2 1845.35    78.5 1836.83   127.6 1827.42   176.6 1817.51
   255.2 1803.51   274.8 1799.63   284.6 1797.42   294.4 1794.88     314 1788.94
   323.8 1786.34   333.7 1785.04   343.5 1784.84   372.9 1785.28   402.4 1785.44
   412.2 1786.78     422 1789.32   431.8 1791.72   441.6 1793.07   451.4 1793.79
   510.3 1797.56   656.7 1805.73   666.2 1806.37   675.8 1807.66   685.4 1810.16
   694.9  1813.9     714 1822.82   723.6 1826.96   752.2 1838.23   809.5 1861.54
#Mann= 3 ,-1 , 0
       0     .12       0     314    .045       0     422     .12       0
Bank Sta=314,422
XS Rating Curve= 0 ,0
Exp/Cntr=0.3,0.1

Type RM Length L Ch R = 1 ,37422.7 ,334.9,324.7,314.5
XS GIS Cut Line= 2
     1810346.681      184021.404     1811124.649       184028.79
#Sta/Elev= 30
       0 1858.41    68.1 1838.47    97.2 1829.31  126.851821.234   176.71808.364
   194.5 1804.68   204.2 1803.66   223.7 1802.64   272.3 1801.15   301.5 1798.48
   311.2 1797.02   320.9  1794.7   340.4 1789.07   359.8 1784.39   369.6  1783.1
   379.3 1782.87   476.5 1783.08   486.2 1783.93     496 1786.29   515.4 1792.68
   525.2 1794.53   612.7 1803.51   622.4 1805.48   632.1 1809.08   709.9 1843.33
   729.4 1852.38   748.8 1862.22   758.6 1866.75   768.3 1870.27     778 1872.89
#Mann= 5 ,-1 , 0
       0     .12       0  126.85    .016       0   176.7     .12       0
   369.6    .045       0   476.5     .12       0
Bank Sta=369.6,476.5
XS Rating Curve= 0 ,0
Exp/Cntr=0.3,0.1

Type RM Length L Ch R = 1 ,37098   ,499,479.5,460.3
XS GIS Cut Line= 4
     1810412.424      184525.457     1810641.616       184388.37
     1811023.561      184287.675     1811147.632      184226.353
#Sta/Elev= 30
       0 1874.17    76.3 1849.52    95.4 1842.81   114.5 1835.65     124 1832.47
   143.1 1826.68   162.1 1821.53   181.2 1816.89   200.3 1812.72   238.4  1805.7
   267.1 1801.45   276.7 1800.61     296 1799.64   305.6 1798.61   315.2 1796.68
   324.9  1793.9   353.8 1784.65   363.4 1782.94     373 1782.62   469.4 1783.02
     479 1783.45   488.6 1785.57   507.9 1793.91   517.6 1795.58   633.2  1801.8
   642.8  1802.4   652.4 1803.79   662.1 1806.64   671.3 1810.22   800.5 1861.69
#Mann= 3 ,-1 , 0
       0     .12       0   353.8    .045       0   488.6     .12       0
Bank Sta=353.8,488.6
XS Rating Curve= 0 ,0
Exp/Cntr=0.3,0.1

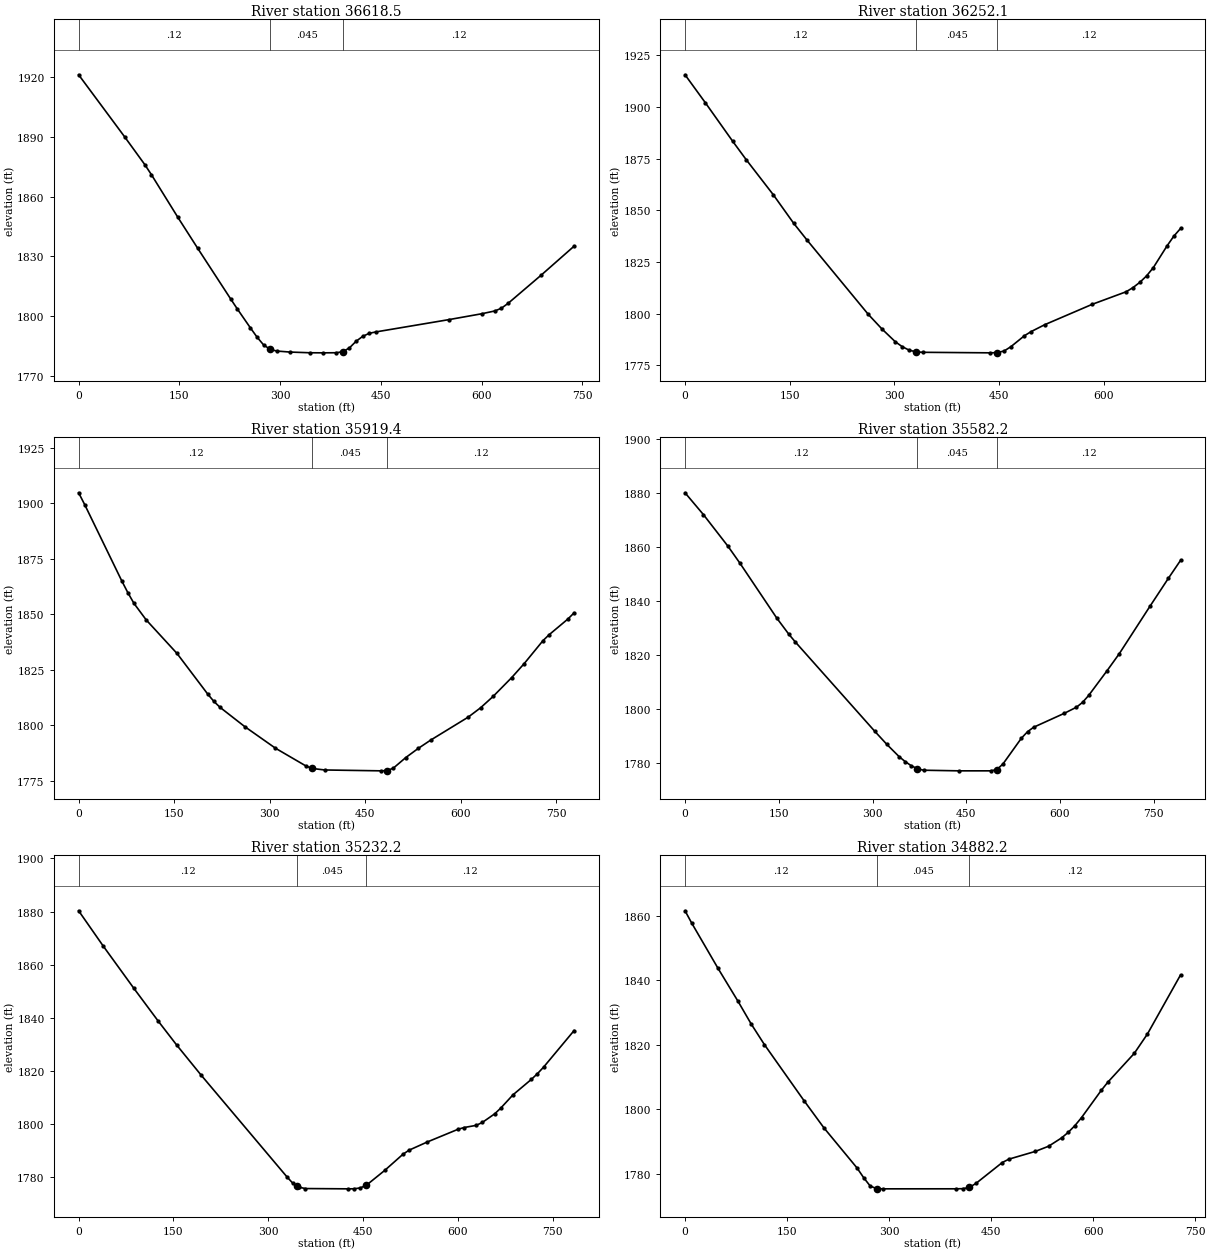
Type RM Length L Ch R = 1 ,36618.5 ,382.2,366.5,350.1
XS GIS Cut Line= 2
     1810743.733      185003.076     1811268.696      184484.901
#Sta/Elev= 30
       0  1921.2    68.8 1889.89    98.4 1876.13   108.2 1871.11   147.5 1849.71
     177 1834.17   226.2 1808.67     236 1803.69   255.7 1794.07   265.5 1789.47
   275.4 1785.49   285.2 1783.27     295 1782.43   314.7 1781.92   344.2 1781.57
   363.9 1781.53   383.6 1781.58   393.4 1782.11   403.2 1784.04   413.1 1787.36
   422.9 1789.82   432.7 1791.34   442.6 1792.04   550.8 1798.19   599.9 1801.15
   619.6 1802.57   629.4 1803.95   639.3 1806.38   688.4 1820.51   737.6 1835.12
#Mann= 3 ,-1 , 0
       0     .12       0   285.2    .045       0   393.4     .12       0
Bank Sta=285.2,393.4
XS Rating Curve= 0 ,0
Exp/Cntr=0.3,0.1

Type RM Length L Ch R = 1 ,36252.1 ,332.7,332.6,332.6
XS GIS Cut Line= 2
     1811195.202      185253.668     1811450.713      184591.146
#Sta/Elev= 30
       0 1915.52    29.2 1901.96    68.1 1883.46    87.5 1874.54   126.4 1857.55
   155.6 1843.76   175.1 1835.48   262.6 1799.68   282.1 1792.64   301.5 1786.38
   311.3 1784.05     321  1782.4   330.7 1781.56   340.4 1781.33   437.7 1781.07
   447.4  1781.2   457.2 1781.95   466.9 1784.02   486.4 1789.34   496.1 1791.36
   515.5 1794.68   583.6 1804.54   632.3 1810.62     642 1812.62   651.7 1815.14
   661.4 1818.26   671.2 1822.32   690.6  1832.7   700.4 1837.45   710.1  1841.2
#Mann= 3 ,-1 , 0
       0     .12       0   330.7    .045       0   447.4     .12       0
Bank Sta=330.7,447.4
XS Rating Curve= 0 ,0
Exp/Cntr=0.3,0.1

Type RM Length L Ch R = 1 ,35919.4 ,334.3,337.2,342.3
XS GIS Cut Line= 3
     1811501.925       185379.82      1811640.87      185019.314
     1811781.721      184653.861
#Sta/Elev= 30
       0 1904.76     9.7 1899.33    67.6 1865.17    77.3 1859.78    86.9 1854.96
   106.2 1847.49   154.5 1832.42   202.8  1814.1   212.5  1810.8   222.2 1808.13
   260.8  1799.5   309.1 1789.76   357.4 1781.69     367 1780.64   386.4 1779.97
   474.5 1779.58   484.3 1779.69   494.1 1780.78   513.6 1785.54   533.2 1789.67
   552.8 1793.42   611.6 1803.74   631.1 1807.96   650.7 1813.05   680.1  1821.6
   699.7 1827.89   729.1 1838.19   738.8 1840.87   768.2 1847.92     778 1850.72
#Mann= 3 ,-1 , 0
       0     .12       0     367    .045       0   484.3     .12       0
Bank Sta=367,484.3
XS Rating Curve= 0 ,0
Exp/Cntr=0.3,0.1

Type RM Length L Ch R = 1 ,35582.2 ,336.9,350,360.8
XS GIS Cut Line= 3
     1811768.936      185515.696     1811954.224      185127.107
     1812130.084       184810.37
#Sta/Elev= 30
       0 1880.22    29.4 1872.14    68.5 1860.48    88.1 1854.05   146.8  1833.8
   166.3 1827.76   176.1 1825.06   303.3 1791.95   322.9 1787.03   342.4 1782.52
   352.2 1780.66     362 1779.12   371.8    1778   381.6 1777.46     438 1777.23
   489.2 1777.23     499  1777.7   508.8 1779.81   538.2 1789.32     548 1791.72
   557.8 1793.38   606.8 1798.53   626.3  1800.8   636.1  1802.6   645.9 1805.18
   675.3 1814.33   694.9 1820.65   743.8 1838.15   773.2 1848.49   792.8 1855.17
#Mann= 3 ,-1 , 0
       0     .12       0   371.8    .045       0     499     .12       0
Bank Sta=371.8,499
XS Rating Curve= 0 ,0
Exp/Cntr=0.3,0.1

Type RM Length L Ch R = 1 ,35232.2 ,354,350,346
XS GIS Cut Line= 3
     1811930.688      185628.546     1812234.388      185329.573
     1812489.314      185078.614
#Sta/Elev= 30
       0  1880.3    38.7  1867.1    87.2 1851.18   125.9  1838.8     155 1829.83
   193.7  1818.5   329.3 1780.27     339 1777.76  345.58 1776.79   348.7 1776.33
   358.4  1775.8   426.2 1775.69   435.8 1775.71   445.5 1776.03   455.2 1777.04
   484.2 1782.61   513.2 1788.72   522.8 1790.24   551.8 1793.34   600.2 1798.09
   609.9 1798.76   629.2 1799.58   638.9 1800.71   658.2  1803.9   667.9 1806.08
   687.2 1811.06   716.2 1816.86   725.9 1819.02   735.6 1821.48   783.9 1835.25
#Mann= 3 ,-1 , 0
       0     .12       0  345.58    .045       0   455.2     .12       0
Bank Sta=345.58,455.2
XS Rating Curve= 0 ,0
Exp/Cntr=0.3,0.1

Type RM Length L Ch R = 1 ,34882.2 ,360.4,350,340
XS GIS Cut Line= 3
     1812256.286       185850.52      1812478.37       185579.91
      1812718.17      185287.091
#Sta/Elev= 30
       0  1861.6     9.7 1857.82    48.6  1843.7    77.8 1833.55    97.2  1826.5
   116.7 1820.08     175 1802.67   204.2 1794.25   252.8 1781.83   262.6  1778.8
   272.3 1776.18     282 1775.37   291.7 1775.32   398.6 1775.33   408.3 1775.37
     418 1775.76   427.7 1776.99   466.5 1783.49   476.2 1784.53     515 1786.93
   534.5 1788.53   553.9 1791.15   563.6 1792.88   573.3 1794.94     583 1797.42
   612.1 1805.89   621.8 1808.44   660.6 1817.36     680 1823.39   728.6 1841.68
#Mann= 3 ,-1 , 0
       0     .12       0     282    .045       0     418     .12       0
Bank Sta=282,418
XS Rating Curve= 0 ,0
Exp/Cntr=0.3,0.1

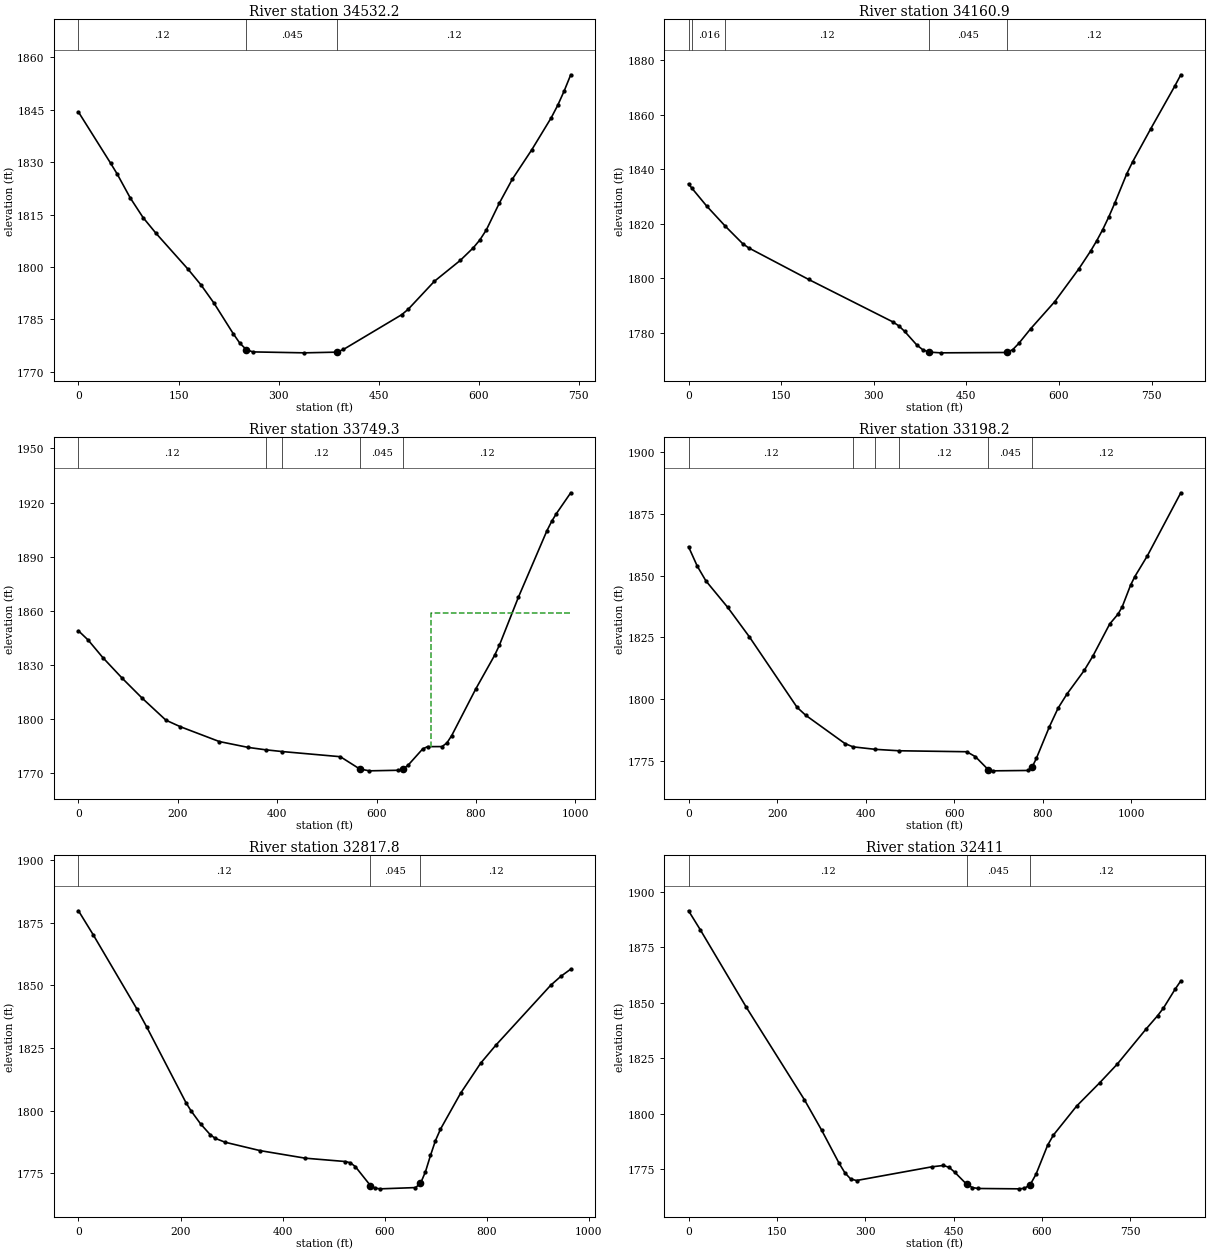
Type RM Length L Ch R = 1 ,34532.2 ,364.1,371.2,378
XS GIS Cut Line= 3
     1812627.254      186091.594     1812762.949       185781.29
     1812926.094      185416.944
#Sta/Elev= 30
       0 1844.37    48.4 1829.64    58.1 1826.59    77.4 1819.83    96.8 1814.14
   116.1 1809.65   164.5 1799.28   183.8  1794.8   203.2  1789.6   232.2  1780.8
   241.9 1778.14   251.6  1776.3   261.3 1775.64   338.7 1775.37   387.4 1775.57
   397.1 1776.33   484.7 1786.32   494.5  1787.9   533.4 1795.85   572.4 1801.87
   591.8 1805.46   601.6  1807.7   611.3 1810.56   630.8 1818.24   650.2 1825.08
   679.5 1833.55   708.7 1842.74   718.4 1846.29   728.1 1850.42   737.9 1855.04
#Mann= 3 ,-1 , 0
       0     .12       0   251.6    .045       0   387.4     .12       0
Bank Sta=251.6,387.4
XS Rating Curve= 0 ,0
Exp/Cntr=0.3,0.1

Type RM Length L Ch R = 1 ,34160.9 ,407.2,411.7,416.1
XS GIS Cut Line= 2
     1812852.133      186260.079     1813302.214      185601.942
#Sta/Elev= 30
       0  1834.6    5.121833.122    29.2 1826.53   59.841819.022    87.5 1812.73
    97.2 1811.16   194.5 1799.56   330.6 1784.02   340.3 1782.58     350 1780.51
   369.5 1775.56   379.2 1773.79   388.9 1772.91   408.4 1772.63   515.3 1772.76
   525.1 1773.81   534.8 1776.07   554.2 1781.49   593.1  1791.4     632 1803.39
   651.5 1810.07   661.2 1813.79   670.9 1817.87   680.6 1822.47   690.4 1827.59
   709.8 1838.33   719.5 1842.81   748.7 1854.87   787.6 1870.51   797.3 1874.64
#Mann= 5 ,-1 , 0
       0     .12       0    5.12    .016       0   59.84     .12       0
   388.9    .045       0   515.3     .12       0
Bank Sta=388.9,515.3
XS Rating Curve= 0 ,0
Exp/Cntr=0.3,0.1

Type RM Length L Ch R = 1 ,33749.3 ,523.5,551.1,578.7
XS GIS Cut Line= 4
     1813029.069      186481.651     1813242.311      186343.231
     1813575.644      185961.286     1813658.288      185746.867
#Sta/Elev= 30
       0 1848.98    19.6 1843.84    48.9 1834.19      88 1822.74   127.1 1811.98
     176 1799.49   205.3 1795.84   283.5 1787.65     342 1784.38  376.671783.081
  409.791782.112   527.2 1779.25   566.2 1772.45   585.7 1771.42   644.2 1771.74
   653.9  1772.5   663.7 1774.58   692.9 1783.54   702.7 1784.82   731.9 1784.86
   741.7 1786.86   751.4 1790.96   799.5 1816.62   837.8 1835.43   847.4 1841.02
   885.6 1867.55   943.1 1904.44   952.7 1909.63   962.2 1913.94     991 1925.44
#Mann= 5 ,-1 , 0
       0     .12       0  376.67    .016       0  409.79     .12       0
   566.2    .045       0   653.9     .12       0
#XS Ineff= 2 , 0
                          709.44            1859
Permanent Ineff=
       F       F
Bank Sta=566.2,653.9
XS Rating Curve= 0 ,0
Exp/Cntr=0.3,0.1

Type RM Length L Ch R = 1 ,33198.2 ,362,380.3,398.6
XS GIS Cut Line= 4
     1813129.928      186674.385     1813353.422      186551.564
       1814006.2      186464.759     1814188.368      186543.858
#Sta/Elev= 30
       0 1861.72    19.6  1853.9    39.2 1847.89    88.3  1837.2   137.3 1825.24
   245.2 1796.64   264.8 1793.41   353.3 1781.97  371.391780.628  422.151779.609
  475.431779.036   628.5 1778.64   648.2 1776.63   677.6 1771.28   687.5  1770.9
   766.1 1771.05   775.9 1772.31   785.8 1775.95   815.3  1788.8   834.9 1796.32
   854.6 1801.94   893.9 1811.59   913.5 1817.42   951.4  1830.4   970.3 1834.42
   979.7 1837.36   998.7 1846.18  1008.1 1849.58  1036.5 1858.02  1112.1 1883.59
#Mann= 6 ,-1 , 0
       0     .12       0  371.39     .06       0  422.15    .016       0
  475.43     .12       0   677.6    .045       0   775.9     .12       0
Bank Sta=677.6,775.9
XS Rating Curve= 0 ,0
Exp/Cntr=0.3,0.1

Type RM Length L Ch R = 1 ,32817.8 ,400.4,406.8,413.2
XS GIS Cut Line= 3
     1813165.761       186807.55     1813447.172      186749.481
     1814082.713      186983.628
#Sta/Elev= 30
       0 1879.71    28.7 1870.21   114.9 1840.42   134.1 1833.24   210.7  1803.2
   220.3 1800.05   239.4 1794.73   258.6 1790.37   268.2 1788.98   287.3 1787.45
     356  1784.1   444.4 1781.09   522.9 1779.76   532.7 1779.27   542.6 1777.72
     572  1770.2   581.8  1769.1   591.6 1768.87   660.4 1769.37   670.2 1771.01
     680 1775.72   689.8 1782.19   699.6 1788.13   709.4 1792.67   748.7 1806.95
     788 1818.93   817.4 1826.03   925.4 1850.03     945 1853.54   964.6 1856.45
#Mann= 3 ,-1 , 0
       0     .12       0     572    .045       0   670.2     .12       0
Bank Sta=572,670.2
XS Rating Curve= 0 ,0
Exp/Cntr=0.3,0.1

Type RM Length L Ch R = 1 ,32411   ,393.7,403.9,414.2
XS GIS Cut Line= 2
     1813138.849      186976.178     1813863.036      187393.553
#Sta/Elev= 30
       0 1891.48    19.7 1883.04    98.3 1847.94   196.7 1806.41   226.2 1792.59
   255.7 1777.75   265.5 1773.47   275.3 1770.71   285.2 1770.02     413 1776.18
   432.7  1776.8   442.5 1775.95   452.3 1773.66     472 1768.38   481.8 1766.87
   491.7 1766.43   560.5 1766.27   570.4 1766.49   580.2 1768.19     590 1772.86
   609.7 1785.92   619.5 1790.48   658.8  1803.5   698.2 1814.06   727.7 1822.37
   776.8 1838.22   796.5 1844.26   806.4  1847.7     826 1856.11   835.8 1859.91
#Mann= 3 ,-1 , 0
       0     .12       0     472    .045       0   580.2     .12       0
Bank Sta=472,580.2
XS Rating Curve= 0 ,0
Exp/Cntr=0.3,0.1