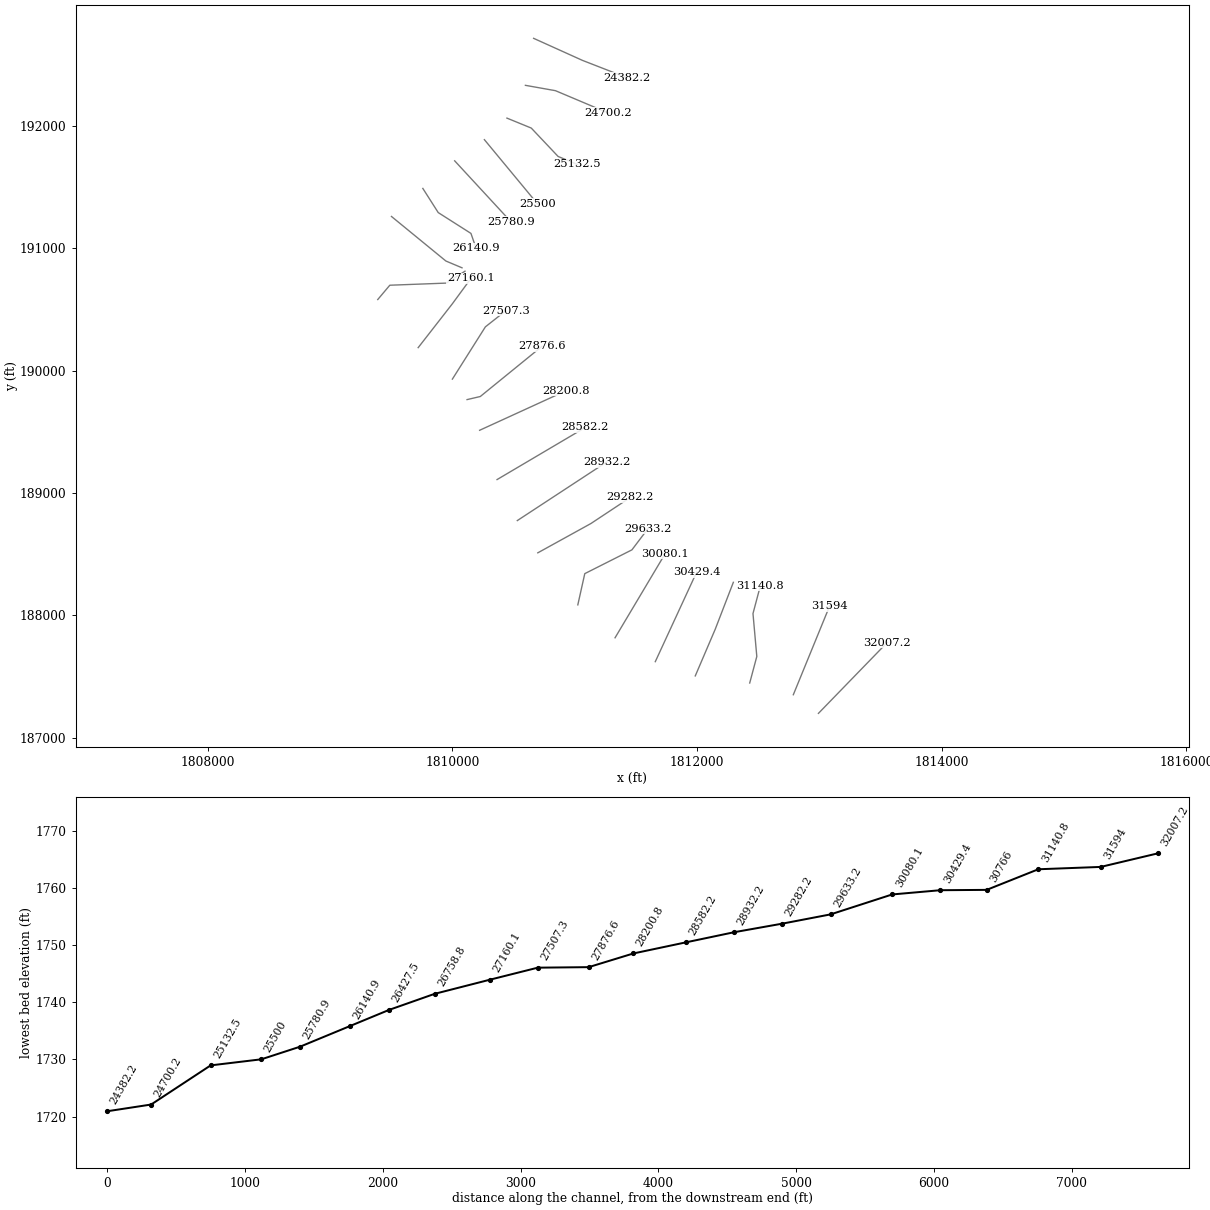
HEC-RAS study MIDFKRV2.prj: MIDFKRV2

--- MIDFKRV2.g01 (geometry) --- (continued)

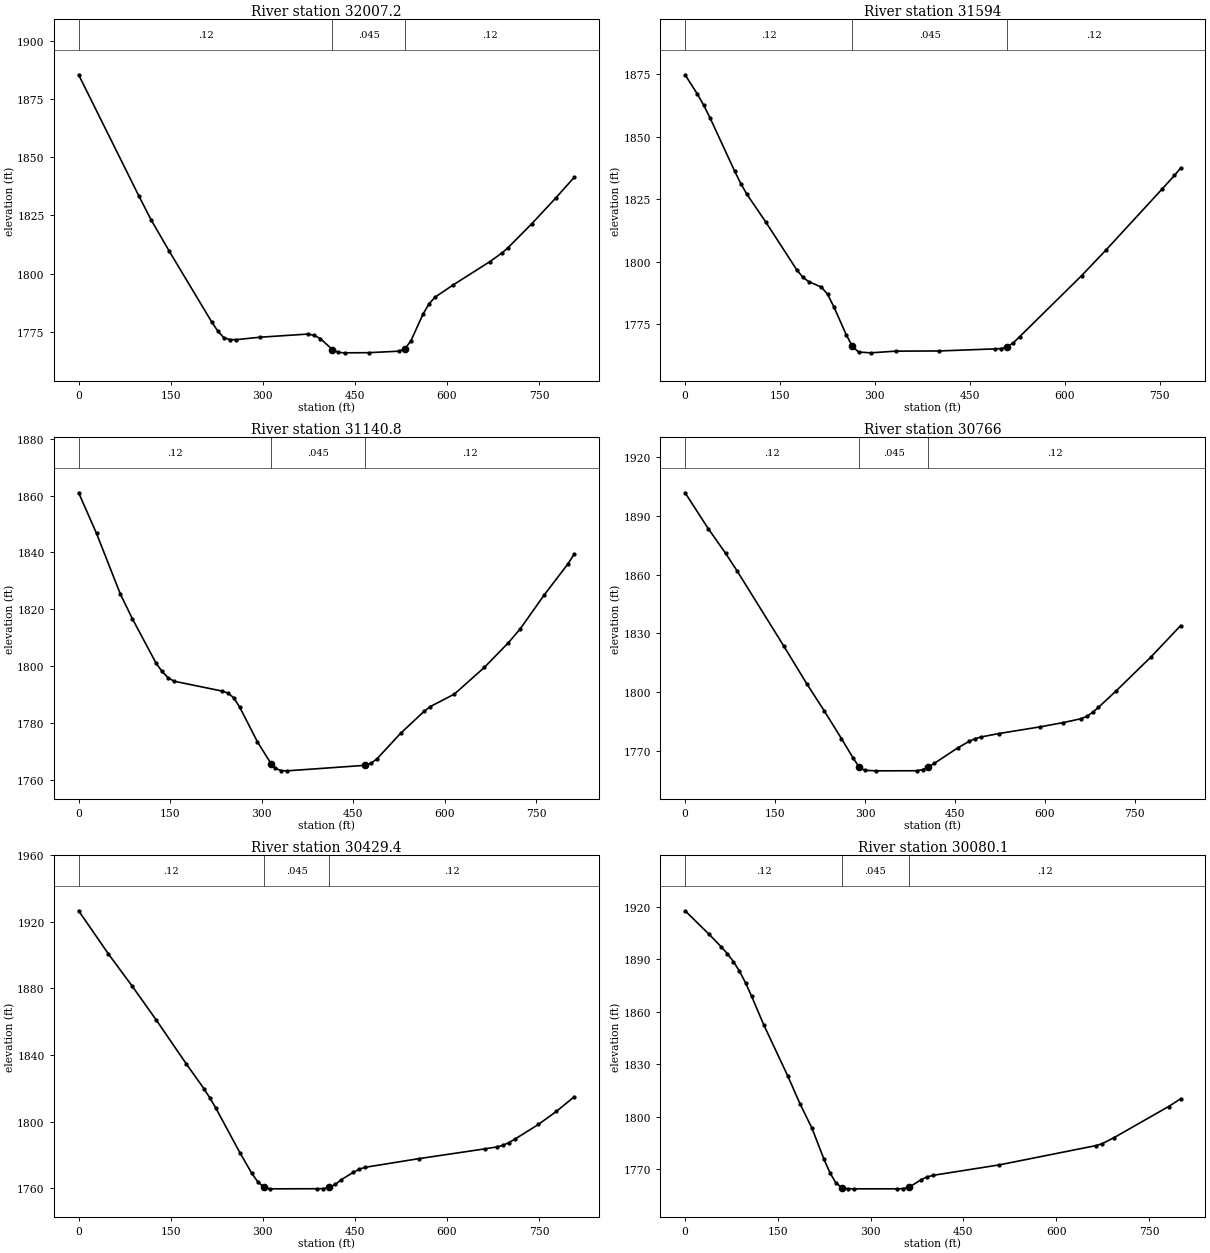
Type RM Length L Ch R = 1 ,32007.2 ,398.2,413.1,427.7
XS GIS Cut Line= 2
     1812992.571      187197.472     1813554.638      187776.658
#Sta/Elev= 30
       0 1885.33    98.4 1833.16   118.1 1823.05   147.6 1809.62   216.5 1779.37
   226.4 1775.45   236.2 1772.58   246.1 1771.69   255.9 1771.64   295.3  1772.7
     374 1774.07   383.8 1773.45   393.7 1772.09   413.4 1767.41   423.2 1766.18
   433.1    1766   472.4 1766.07   521.6 1766.71   531.5 1767.74   541.3 1771.21
     561 1782.66   570.9 1787.12   580.7 1789.93   610.2 1795.18   669.3 1805.05
     689 1808.77   698.8 1810.97   738.2 1821.44   777.6  1832.6   807.1 1841.31
#Mann= 3 ,-1 , 0
       0     .12       0   413.4    .045       0   531.5     .12       0
Bank Sta=413.4,531.5
XS Rating Curve= 0 ,0
Exp/Cntr=0.3,0.1

Type RM Length L Ch R = 1 ,31594   ,435.2,453.2,471.1
XS GIS Cut Line= 2
     1812787.355      187349.879     1813084.056      188074.838
#Sta/Elev= 30
       0 1874.78    19.6 1866.99    29.4  1862.6    39.2 1857.69    78.3 1836.28
    88.1 1831.26    97.9 1826.94   127.3 1816.02   176.2 1796.94     186 1793.86
   195.8 1792.04   215.4 1789.93   225.2 1787.06     235 1782.12   254.6 1770.95
   264.4  1766.2   274.2 1763.97   293.4 1763.64   332.9 1764.32   401.4 1764.39
   489.6 1765.22   499.4 1765.36   509.2 1765.97     519 1767.71   528.7 1770.06
   626.7 1794.47   665.8 1804.88     754 1829.11   773.5 1834.55   783.3 1837.53
#Mann= 3 ,-1 , 0
       0     .12       0   264.4    .045       0   509.2     .12       0
Bank Sta=264.4,509.2
XS Rating Curve= 0 ,0
Exp/Cntr=0.3,0.1

Type RM Length L Ch R = 1 ,31140.8 ,393.5,374.9,356.2
XS GIS Cut Line= 4
     1812430.847      187445.745     1812488.839      187662.675
     1812457.589       188013.37     1812518.168      188241.148
#Sta/Elev= 30
       0 1860.98    29.3  1846.7    68.3 1825.44    87.9 1816.77   126.9 1801.11
   136.7 1798.18   146.4 1796.03   156.2 1794.75   234.3 1791.31   244.1 1790.63
   253.9 1788.99   263.7 1785.75     293 1773.46  315.351765.775   322.4 1764.12
   332.1  1763.3   341.9 1763.23     469 1765.16   478.8 1765.85   488.6 1767.34
   527.7  1776.4   566.8 1784.24   576.6 1785.84   615.9  1790.2     665 1799.58
   704.3 1808.23   723.9 1813.15   763.2 1825.07   802.5 1836.09   812.3 1839.43
#Mann= 3 ,-1 , 0
       0     .12       0  315.35    .045       0     469     .12       0
Bank Sta=315.35,469
XS Rating Curve= 0 ,0
Exp/Cntr=0.3,0.1

Type RM Length L Ch R = 1 ,30766   ,337.6,336.6,335.5
XS GIS Cut Line= 3
     1811985.715       187503.68     1812149.003       187885.42
     1812297.038      188268.811
#Sta/Elev= 30
       0 1901.93    38.6 1883.59    67.6 1870.92    86.9 1861.83   164.2 1823.67
   202.8 1804.23   231.7 1790.47   260.7 1776.13     280 1766.28   289.7 1761.74
   299.3 1759.91   318.6 1759.63   386.2 1759.68   395.9 1760.25   405.5 1761.62
   415.2  1763.4   454.3 1771.32   473.9 1774.78   483.7 1776.12   493.5 1776.96
   522.8  1778.7   591.3 1782.11   630.5 1784.33   659.8 1786.29   669.6 1787.48
   679.4 1789.52   689.2 1792.12   718.5 1800.49   777.2 1818.05   826.2 1833.97
#Mann= 3 ,-1 , 0
       0     .12       0   289.7    .045       0   405.5     .12       0
Bank Sta=289.7,405.5
XS Rating Curve= 0 ,0
Exp/Cntr=0.3,0.1

Type RM Length L Ch R = 1 ,30429.4 ,353.3,349.3,345.4
XS GIS Cut Line= 2
     1811658.968      187620.172     1811997.585      188353.178
#Sta/Elev= 30
       0 1926.65    48.6 1900.69    87.6 1881.21   126.5    1861   175.1 1834.84
   204.3 1819.68     214 1814.06   223.8 1807.92   262.7 1781.31   282.1 1768.92
   291.8 1763.83   301.6 1760.63   311.3 1759.57   389.1 1759.63   398.9 1759.72
   408.6 1760.38   418.3 1762.27     428 1765.08   447.5 1769.48   457.2 1771.39
     467 1772.52   554.5 1777.72   661.5 1783.57     681 1784.72   690.7 1785.64
   700.4 1787.23   710.2 1789.29   749.1 1798.26   778.3 1806.08   807.4 1814.85
#Mann= 3 ,-1 , 0
       0     .12       0   301.6    .045       0   408.6     .12       0
Bank Sta=301.6,408.6
XS Rating Curve= 0 ,0
Exp/Cntr=0.3,0.1

Type RM Length L Ch R = 1 ,30080.1 ,468.8,446.9,425
XS GIS Cut Line= 2
     1811330.118      187815.409     1811740.139      188503.747
#Sta/Elev= 30
       0 1917.65    39.1 1904.12    58.6 1896.98    68.4 1893.13    78.2 1888.58
    87.9 1883.16    97.7 1876.53   107.5 1868.84     127 1852.66   166.1 1823.22
   185.6 1807.54   205.2  1793.4   224.7  1775.6   234.5 1767.81   244.3 1761.97
     254 1759.48   263.8 1758.85   273.6 1758.83     342 1758.84   351.8 1758.95
   361.5 1759.61   381.1 1763.94   390.8 1765.56   400.6 1766.53   508.1 1772.52
   664.4 1783.54   674.2 1784.59   693.7 1788.11   781.7 1805.84   801.2 1810.26
#Mann= 3 ,-1 , 0
       0     .12       0     254    .045       0   361.5     .12       0
Bank Sta=254,361.5
XS Rating Curve= 0 ,0
Exp/Cntr=0.3,0.1

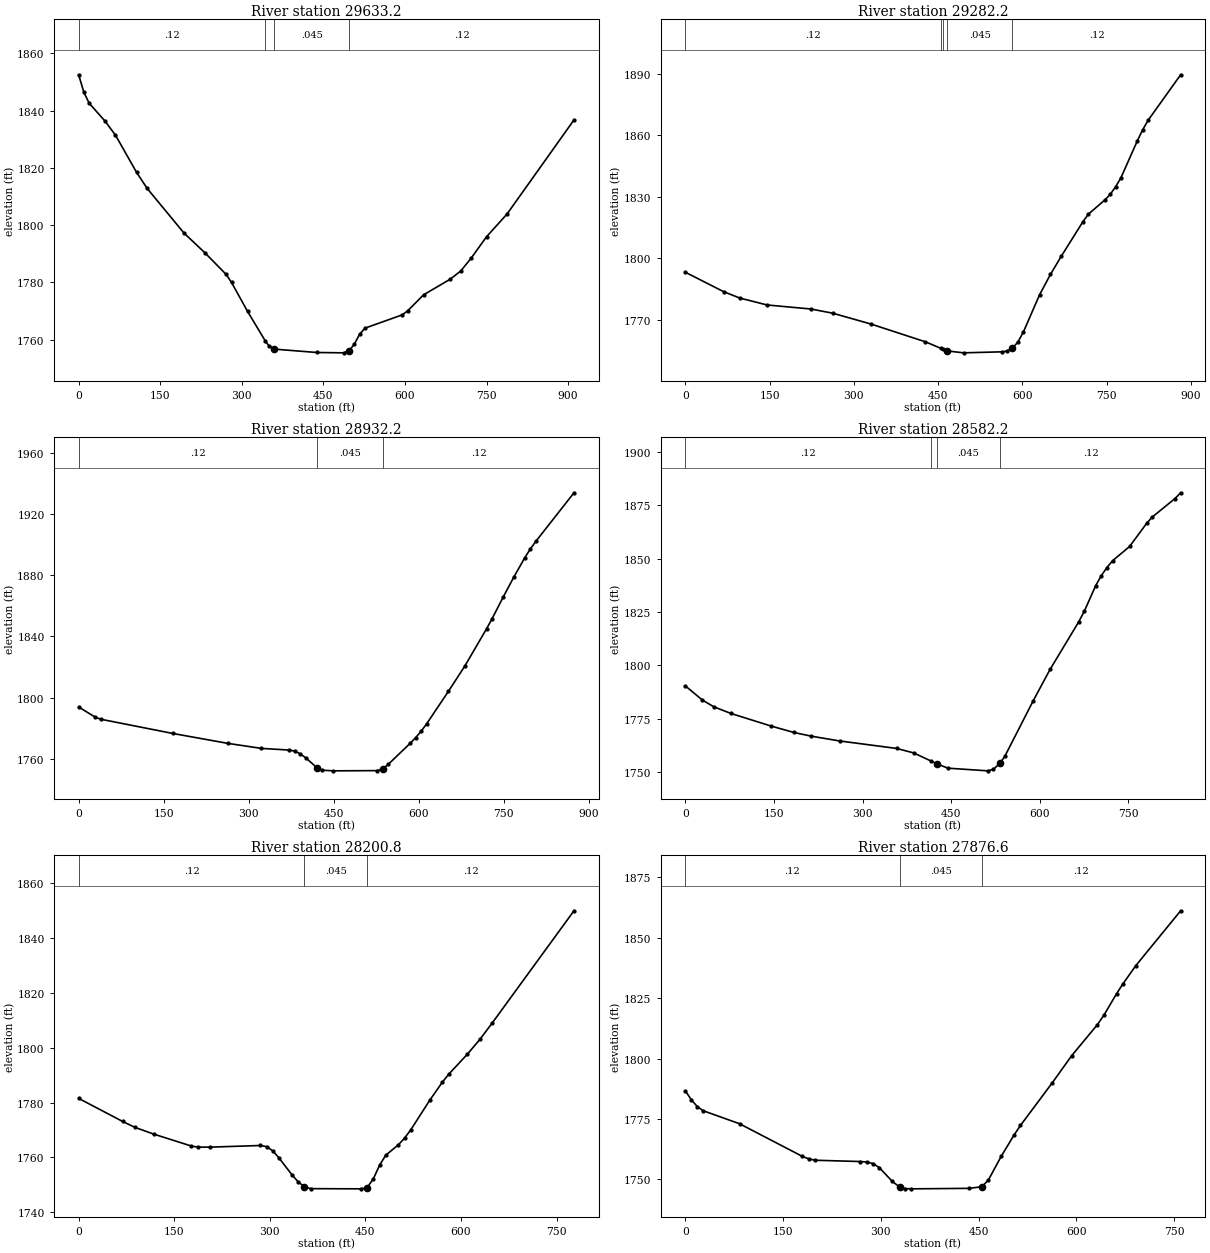
Type RM Length L Ch R = 1 ,29633.2 ,349.7,351,355.4
XS GIS Cut Line= 4
     1811025.666      188084.525     1811082.589      188339.759
     1811468.005      188534.203     1811599.254       188707.79
#Sta/Elev= 30
       0 1852.54     9.7  1846.4    19.4  1842.6    48.4 1836.38    67.8 1831.42
   106.5 1818.46   125.9 1812.84   193.7 1797.23   232.4 1790.28   271.3 1782.75
   281.1 1779.97   310.6 1769.83  342.891759.618   349.8 1757.82   359.6 1756.65
   438.1 1755.47   487.2 1755.35     497 1756.03   506.8 1758.32   516.6 1761.81
   526.4 1763.97   595.1 1768.63   604.9 1770.02   634.3 1775.63   683.4 1781.11
   702.6 1783.96   721.6  1788.4     750 1795.92   787.8 1803.89   910.8 1836.76
#Mann= 4 ,-1 , 0
       0     .12       0  342.89     .08       0   359.6    .045       0
     497     .12       0
Bank Sta=359.6,497
XS Rating Curve= 0 ,0
Exp/Cntr=0.3,0.1

Type RM Length L Ch R = 1 ,29282.2 ,347.2,350,349.8
XS GIS Cut Line= 3
     1810698.641      188509.889     1811132.422       188749.24
     1811454.506      188962.455
#Sta/Elev= 30
       0 1793.15      68 1783.67    97.1 1780.51   145.7 1777.13   223.4 1775.17
   262.3 1773.12   330.3 1767.83   427.4 1759.12  455.551755.854  459.361755.426
   466.3 1754.66   495.4 1753.73     563 1754.22   572.7 1754.56   582.3 1755.99
     592 1759.02   601.7 1763.88   630.6 1782.12   649.9 1792.04   669.2 1800.96
   707.9 1817.92   717.5 1821.55   746.5  1828.4   756.2 1831.16   765.8 1834.88
   775.5 1839.38   804.4 1857.27   814.1 1862.78   823.8 1867.45   881.7 1889.69
#Mann= 5 ,-1 , 0
       0     .12       0  455.55     .06       0  459.36     .08       0
   466.3    .045       0   582.3     .12       0
Bank Sta=466.3,582.3
XS Rating Curve= 0 ,0
Exp/Cntr=0.3,0.1

Type RM Length L Ch R = 1 ,28932.2 ,351.8,350,348.2
XS GIS Cut Line= 3
     1810531.093       188773.53     1810939.759      189041.439
     1811261.881      189252.612
#Sta/Elev= 30
       0 1793.93    29.3 1787.29    39.1 1785.92   166.1 1776.64   263.9 1770.12
   322.5 1766.88   371.4  1765.8   381.2  1765.1   390.9 1763.35   400.7 1760.68
   420.2 1754.35     430 1752.63   449.6 1752.23   527.2 1752.37   536.8 1753.65
   546.4 1756.53     585 1770.26   594.6 1773.93   604.2 1778.09   613.8 1782.88
   652.4 1804.19   681.2 1820.61   719.8 1845.12   729.4  1851.6   748.6 1865.45
   767.9 1878.89   787.2 1891.47   796.8  1897.1   806.4    1902   873.8 1933.79
#Mann= 3 ,-1 , 0
       0     .12       0   420.2    .045       0   536.8     .12       0
Bank Sta=420.2,536.8
XS Rating Curve= 0 ,0
Exp/Cntr=0.3,0.1

Type RM Length L Ch R = 1 ,28582.2 ,385,381.3,377.2
XS GIS Cut Line= 3
     1810365.397      189108.629      1810756.59      189339.576
     1811087.386      189534.866
#Sta/Elev= 30
       0 1790.34      29 1783.67    48.3 1780.51    77.3 1777.38     145  1771.5
   183.6 1768.48   212.6 1766.76     261 1764.49   357.6 1760.98   386.6 1758.87
  415.551755.106   425.3 1753.79   444.6 1751.71   511.9 1750.46   521.5 1751.16
  533.231754.201   540.7 1757.22   588.7 1783.27   617.5 1798.12   665.6 1820.26
   675.2 1825.27   694.4 1837.26     704 1842.01   713.6 1845.88   723.2 1849.06
     752 1855.76   780.8 1866.61   790.4 1869.58   828.8 1878.25   838.4 1880.96
#Mann= 4 ,-1 , 0
       0     .12       0  415.55     .08       0   425.3    .045       0
  533.23     .12       0
Bank Sta=425.3,533.23
XS Rating Curve= 0 ,0
Exp/Cntr=0.3,0.1

Type RM Length L Ch R = 1 ,28200.8 ,314.9,324.3,334
XS GIS Cut Line= 2
     1810223.026      189511.595     1810929.711      189834.957
#Sta/Elev= 30
       0 1781.53    68.9 1773.13    88.5 1770.94     118 1768.48   177.1 1764.12
   186.9 1763.76   206.6 1763.74   285.3 1764.34   295.1 1763.91     305 1762.32
   314.8 1759.67   334.5 1753.71   344.3 1751.11   354.2 1749.27     364 1748.59
   442.7 1748.52   452.5 1748.91   462.4 1752.16   472.2 1757.15     482 1760.81
   501.7  1764.6   511.5 1767.04   521.4 1770.16   550.9 1780.84   570.6  1787.4
   580.4 1790.27   609.9 1797.64   629.6 1803.06   649.3 1809.16   777.2 1849.99
#Mann= 3 ,-1 , 0
       0     .12       0   354.2    .045       0   452.5     .12       0
Bank Sta=354.2,452.5
XS Rating Curve= 0 ,0
Exp/Cntr=0.3,0.1

Type RM Length L Ch R = 1 ,27876.6 ,357.1,369.3,381.4
XS GIS Cut Line= 3
     1810120.396      189762.469     1810228.422      189787.675
     1810731.972      190197.262
#Sta/Elev= 30
       0  1786.7     9.2 1783.02    18.5 1780.11    27.7 1778.42    83.2 1773.07
   179.8 1759.53   189.6 1758.51   199.4 1757.96   268.3 1757.43   278.1 1757.24
     288 1756.58   297.8 1754.87   317.5 1749.23  328.711746.904   337.1 1746.21
     347 1746.13   435.5 1746.33   455.1 1747.01     465 1749.78   484.6 1759.54
   504.3 1768.35   514.2 1772.35   563.3  1790.1   592.8 1801.22   632.2 1814.04
     642 1817.87   661.7 1826.87   671.5 1830.97   691.2 1838.49     760 1861.18
#Mann= 3 ,-1 , 0
       0     .12       0  328.71    .045       0   455.1     .12       0
Bank Sta=328.71,455.1
XS Rating Curve= 0 ,0
Exp/Cntr=0.3,0.1

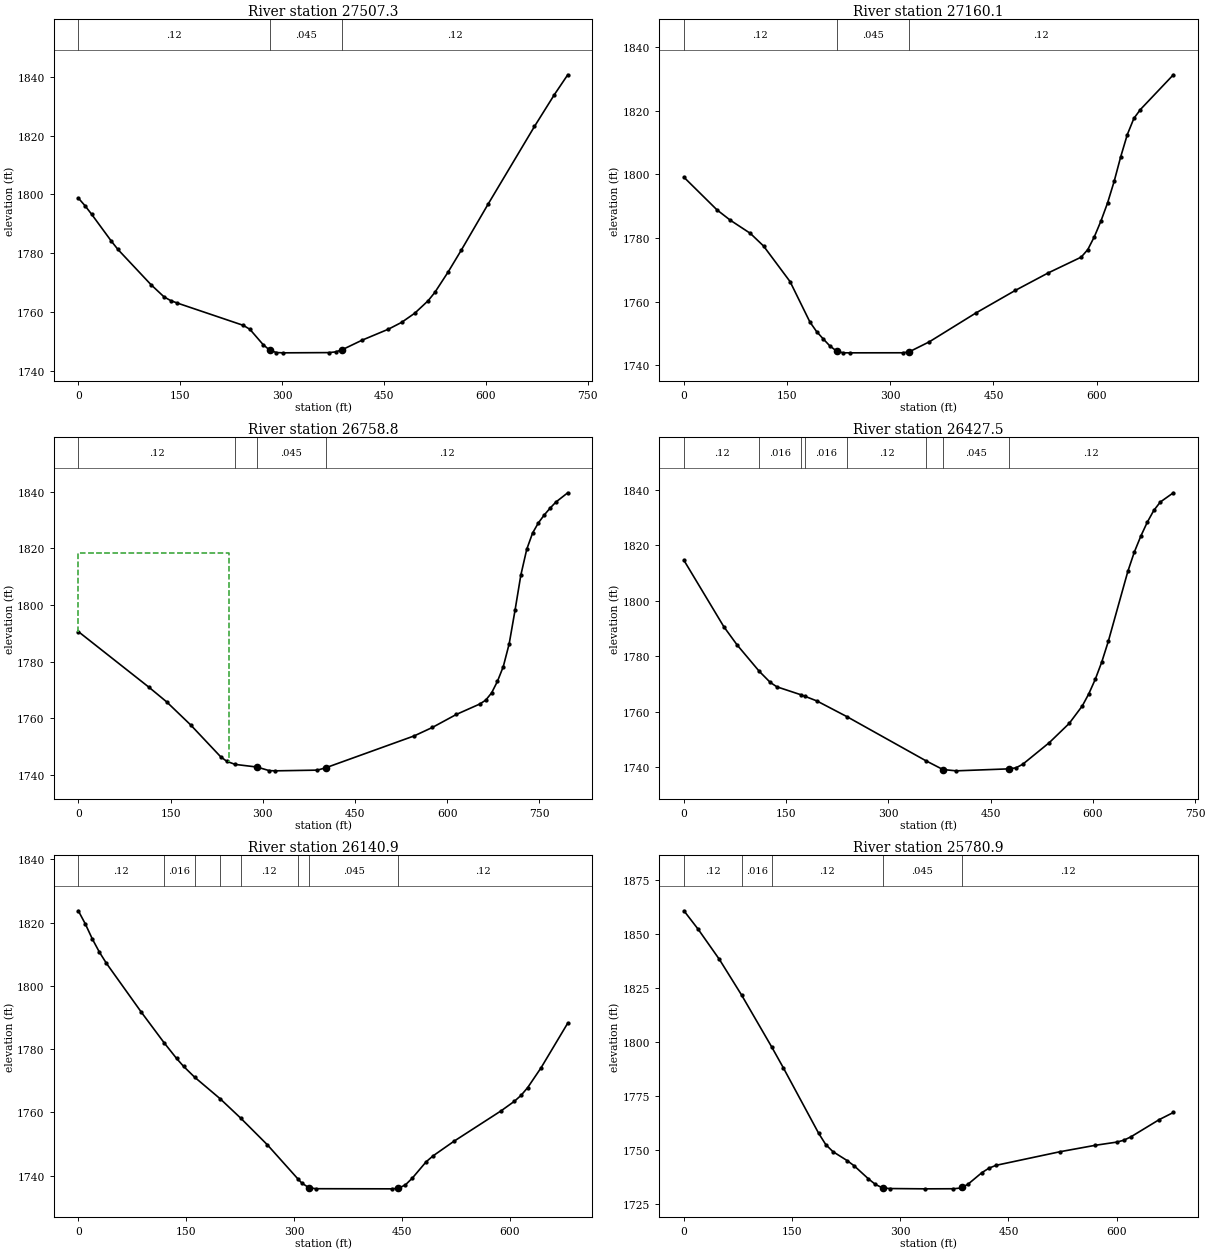
Type RM Length L Ch R = 1 ,27507.3 ,350.7,347.2,343.3
XS GIS Cut Line= 3
     1810000.329      189930.001     1810270.089       190357.12
     1810439.147      190490.416
#Sta/Elev= 30
       0 1798.76     9.7  1796.2    19.4 1793.31    48.6 1784.09    58.3 1781.26
   106.9 1769.28   126.3 1765.08     136 1763.84   145.7    1763   242.9  1755.4
   252.6 1754.05     272 1748.85   281.7 1746.96   291.4 1746.15   301.2 1746.04
   369.2 1746.12   378.9 1746.37   388.6 1747.12   417.7 1750.35   456.6 1754.11
     476 1756.43   495.5 1759.58     515  1763.8   524.8 1766.61   544.3 1773.54
   563.9 1781.07     603  1796.6   671.5 1823.15   700.9 1834.02   720.5 1840.76
#Mann= 3 ,-1 , 0
       0     .12       0   281.7    .045       0   388.6     .12       0
Bank Sta=281.7,388.6
XS Rating Curve= 0 ,0
Exp/Cntr=0.3,0.1

Type RM Length L Ch R = 1 ,27160.1 ,434.3,401.3,368.6
XS GIS Cut Line= 3
     1809720.733      190187.183     1809999.255       190544.62
     1810152.033      190752.953
#Sta/Elev= 30
       0  1799.1    48.2 1788.82    67.5 1785.59    96.4 1781.49   115.7 1777.51
   154.3 1766.31   183.2  1753.6   192.8 1750.64   202.5 1748.31   212.1 1746.12
   221.8 1744.51   231.4 1743.95     241 1743.94   318.2 1743.96   327.8 1744.29
   356.7  1747.4   424.2 1756.43   481.8 1763.56   529.7 1769.06   577.5    1774
   587.1 1776.38   596.7 1780.44   606.2 1785.34   615.8    1791   625.4 1797.78
   634.9 1805.48   644.5 1812.47   654.1 1817.59   663.6 1820.38   711.5 1831.29
#Mann= 3 ,-1 , 0
       0     .12       0   221.8    .045       0   327.8     .12       0
Bank Sta=221.8,327.8
XS Rating Curve= 0 ,0
Exp/Cntr=0.3,0.1

Type RM Length L Ch R = 1 ,26758.8 ,358.5,331.3,304
XS GIS Cut Line= 4
       1809390.2      190580.346     1809488.839      190697.398
     1809950.644      190714.759     1810103.422      190811.981
#Sta/Elev= 30
       0 1790.59   114.8 1770.98   143.5 1765.84   182.6  1757.7   231.7 1746.41
   241.6 1744.83  255.011743.744   290.7 1742.81   310.4 1741.56   320.2 1741.47
     389 1741.72   402.41742.536   546.4 1753.79   575.9 1756.76   615.2 1761.38
   653.3 1765.05   662.9 1766.42   672.4 1768.96   681.9 1773.03   691.4 1778.22
     701 1786.26   710.5 1798.05     720 1810.53   729.6 1819.62   739.1 1825.35
   748.6 1828.96   758.2 1831.75   767.7 1834.16   777.2 1836.31   796.3 1839.55
#Mann= 4 ,-1 , 0
       0     .12       0  255.01     .06       0   290.7    .045       0
   402.4     .12       0
#XS Ineff= 2 , 0
          245.56 1818.25
Permanent Ineff=
       F       F
Bank Sta=290.7,402.4
XS Rating Curve= 0 ,0
Exp/Cntr=0.3,0.1

Type RM Length L Ch R = 1 ,26427.5 ,282,286.6,291.2
XS GIS Cut Line= 3
     1809502.315       191259.51     1809947.172      190895.314
     1810079.116      190839.759
#Sta/Elev= 30
       0 1814.53    58.5 1790.62      78 1784.04  110.371774.571   126.7 1770.52
   136.4 1768.94  171.861766.061  177.631765.519   194.9 1763.87  239.531758.141
  354.741742.328     380 1739.13   399.5 1738.66   477.5 1739.38   487.2 1739.76
     497 1741.01     536 1748.81   565.2 1755.73   584.5 1762.06     594 1766.41
   603.6  1771.7   613.1 1777.92   622.6 1785.29   651.3 1810.54   660.8  1817.5
   670.4 1823.28   679.9  1828.3   689.4 1832.52     699 1835.56   718.1 1838.88
#Mann= 8 ,-1 , 0
       0     .12       0  110.37    .016       0  171.86     .12       0
  177.63    .016       0  239.53     .12       0  354.74     .08       0
     380    .045       0   477.5     .12       0
Bank Sta=380,477.5
XS Rating Curve= 0 ,0
Exp/Cntr=0.3,0.1

Type RM Length L Ch R = 1 ,26140.9 ,369.7,360,350.3
XS GIS Cut Line= 4
     1809758.819      191488.639     1809884.672      191291.148
     1810152.033      191121.009     1810194.666      190998.438
#Sta/Elev= 30
       0 1823.74     9.8 1819.55    19.5 1814.82    29.3 1810.67      39 1807.16
    87.8 1791.63  119.551781.943   136.6 1777.07   146.4 1774.55   161.81771.123
   197.21764.319  225.641758.227     263 1749.74   305.31738.997     311 1737.62
   320.6  1736.2   330.2 1735.85   435.8 1735.81   445.4    1736   455.1 1737.07
   464.7 1739.21   483.9 1744.36   493.5 1746.23   522.3 1750.81   588.2 1760.48
   606.7  1763.5     616 1765.38   625.2 1767.84   643.8  1774.1   680.9 1788.21
#Mann= 8 ,-1 , 0
       0     .12       0  119.55    .016       0   161.8     .12       0
   197.2    .016       0  225.64     .12       0   305.3     .06       0
   320.6    .045       0   445.4     .12       0
Bank Sta=320.6,445.4
XS Rating Curve= 0 ,0
Exp/Cntr=0.3,0.1

Type RM Length L Ch R = 1 ,25780.9 ,283,280.9,278.8
XS GIS Cut Line= 2
     1810019.053      191714.238     1810479.512       191215.83
#Sta/Elev= 30
       0  1860.7    19.7 1852.18    49.2 1838.21   79.971821.745   122.11797.545
   137.7 1788.22   186.8 1757.89   196.7 1752.65   206.5 1749.44   226.2  1745.3
     236 1742.88   255.7 1736.88   265.5 1734.27   275.4 1732.67   285.2 1732.37
   334.4 1732.23   373.7 1732.27   383.5  1732.6  385.391732.913   393.4 1734.24
     413 1739.68   422.9 1741.78   432.7 1743.09   521.2 1749.36   570.4 1752.35
   599.9 1753.81   609.7 1754.67   619.6 1756.23   658.9 1764.19   678.6 1767.51
#Mann= 5 ,-1 , 0
       0     .12       0   79.97    .016       0   122.1     .12       0
   275.4    .045       0  385.39     .12       0
Bank Sta=275.4,385.39
XS Rating Curve= 0 ,0
Exp/Cntr=0.3,0.1

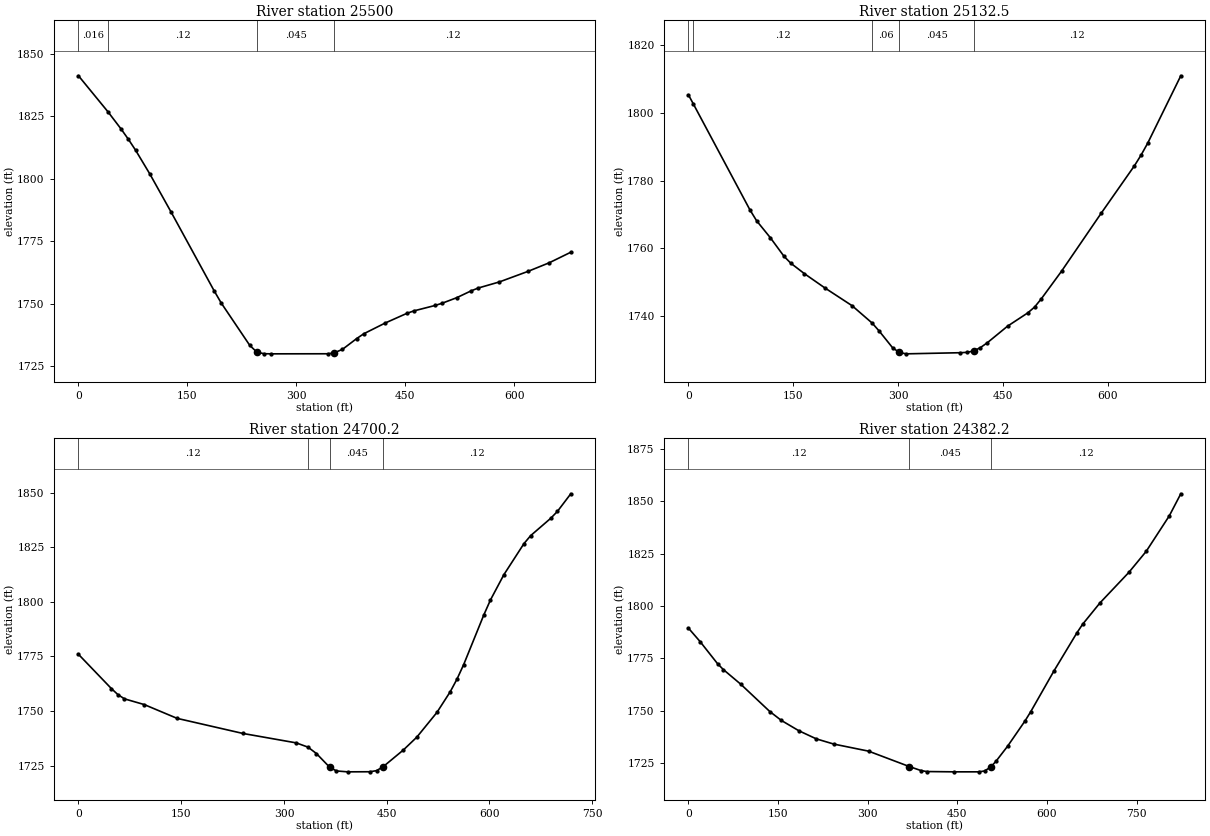
Type RM Length L Ch R = 1 ,25500   ,365,367.5,370.3
XS GIS Cut Line= 2
     1810261.876      191887.314     1810694.283      191364.938
#Sta/Elev= 30
       0 1841.22   40.771826.766      59 1819.82    68.8  1815.8    78.6 1811.49
    98.3 1801.95   127.8 1786.61   186.7 1755.32   196.6 1750.37   235.9 1733.43
   245.7 1730.72   255.5 1730.08   265.4 1730.03     344 1730.06  352.441730.456
   363.6 1731.82   383.3 1736.16   393.1 1738.08   422.6 1742.37   452.1 1746.19
   461.9  1747.2   491.4 1749.39   501.2  1750.3   520.9 1752.47   540.5 1755.17
   550.4 1756.33   579.8 1758.79   619.2 1763.01   648.6 1766.47   678.1 1770.66
#Mann= 4 ,-1 , 0
       0    .016       0   40.77     .12       0   245.7    .045       0
  352.44     .12       0
Bank Sta=245.7,352.44
XS Rating Curve= 0 ,0
Exp/Cntr=0.3,0.1

Type RM Length L Ch R = 1 ,25132.5 ,416.6,432.3,447.5
XS GIS Cut Line= 4
     1810446.267      192063.456     1810645.089       191982.12
     1810864.405      191750.205     1811021.951      191684.693
#Sta/Elev= 30
       0 1805.22    6.871802.605    87.9 1771.39    97.6 1768.14   117.2 1763.16
   136.7  1757.7   146.5 1755.65     166 1752.57   195.3 1748.37   234.2 1743.14
  262.911738.026   272.8 1735.72   292.2 1730.74   301.9 1729.37   311.5 1728.97
   388.9  1729.3   398.6 1729.41   408.3 1729.83   417.9 1730.82   427.6 1732.22
   456.6 1737.11   485.6 1741.03   495.3 1742.74     505 1745.18     534 1753.33
   590.9 1770.45   638.3 1784.38   647.8 1787.52   657.2    1791   704.6 1810.86
#Mann= 5 ,-1 , 0
       0    .016       0    6.87     .12       0  262.91     .06       0
   301.9    .045       0   408.3     .12       0
Bank Sta=301.9,408.3
XS Rating Curve= 0 ,0
Exp/Cntr=0.3,0.1

Type RM Length L Ch R = 1 ,24700.2 ,318.9,318,319.1
XS GIS Cut Line= 3
      1810597.26       192331.41     1810843.005      192287.675
     1811275.223      192105.124
#Sta/Elev= 30
       0 1775.96      48 1760.29    57.6  1757.5    67.2 1755.56      96 1752.95
     144 1746.63     240 1739.72     318 1735.39  335.111733.444   347.4 1730.52
   366.9 1724.19   376.7 1722.54   392.8 1722.13   425.6 1722.17   435.3 1722.69
   445.1 1724.55   474.4 1732.15     494 1738.03   523.3 1749.33   542.8 1758.83
   552.6 1764.58   562.4 1771.26   591.7 1793.93   601.5 1800.87     621  1812.4
   650.4 1826.68   660.2 1830.34   689.5 1838.28   699.2 1841.42   718.8 1849.51
#Mann= 4 ,-1 , 0
       0     .12       0  335.11     .06       0   366.9    .045       0
   445.1     .12       0
Bank Sta=366.9,445.1
XS Rating Curve= 0 ,0
Exp/Cntr=0.3,0.1

Type RM Length L Ch R = 1 ,24382.2 ,346.5,354.7,360.8
XS GIS Cut Line= 3
     1810664.439      192715.596     1811063.207      192535.507
     1811423.293       192395.41
#Sta/Elev= 30
       0 1789.44    19.4 1783.06    48.6 1772.53    58.3 1769.72    87.5 1762.72
   136.1 1749.71   155.6 1745.43   184.7 1740.55   213.9 1736.68   243.1  1734.2
   301.4 1730.82   369.5 1723.49   388.9 1721.59   398.6  1721.1     445 1720.96
   485.8 1720.96   495.5 1721.37  505.991723.307   514.8 1726.06   534.1 1733.19
   563.1 1745.18   572.8 1749.64   611.4 1768.95   650.1 1787.24   659.7 1791.34
   688.7  1801.5     737 1816.03     766 1826.05   804.6 1842.95   823.9 1853.49
#Mann= 3 ,-1 , 0
       0     .12       0   369.5    .045       0  505.99     .12       0
Bank Sta=369.5,505.99
XS Rating Curve= 0 ,0
Exp/Cntr=0.3,0.1