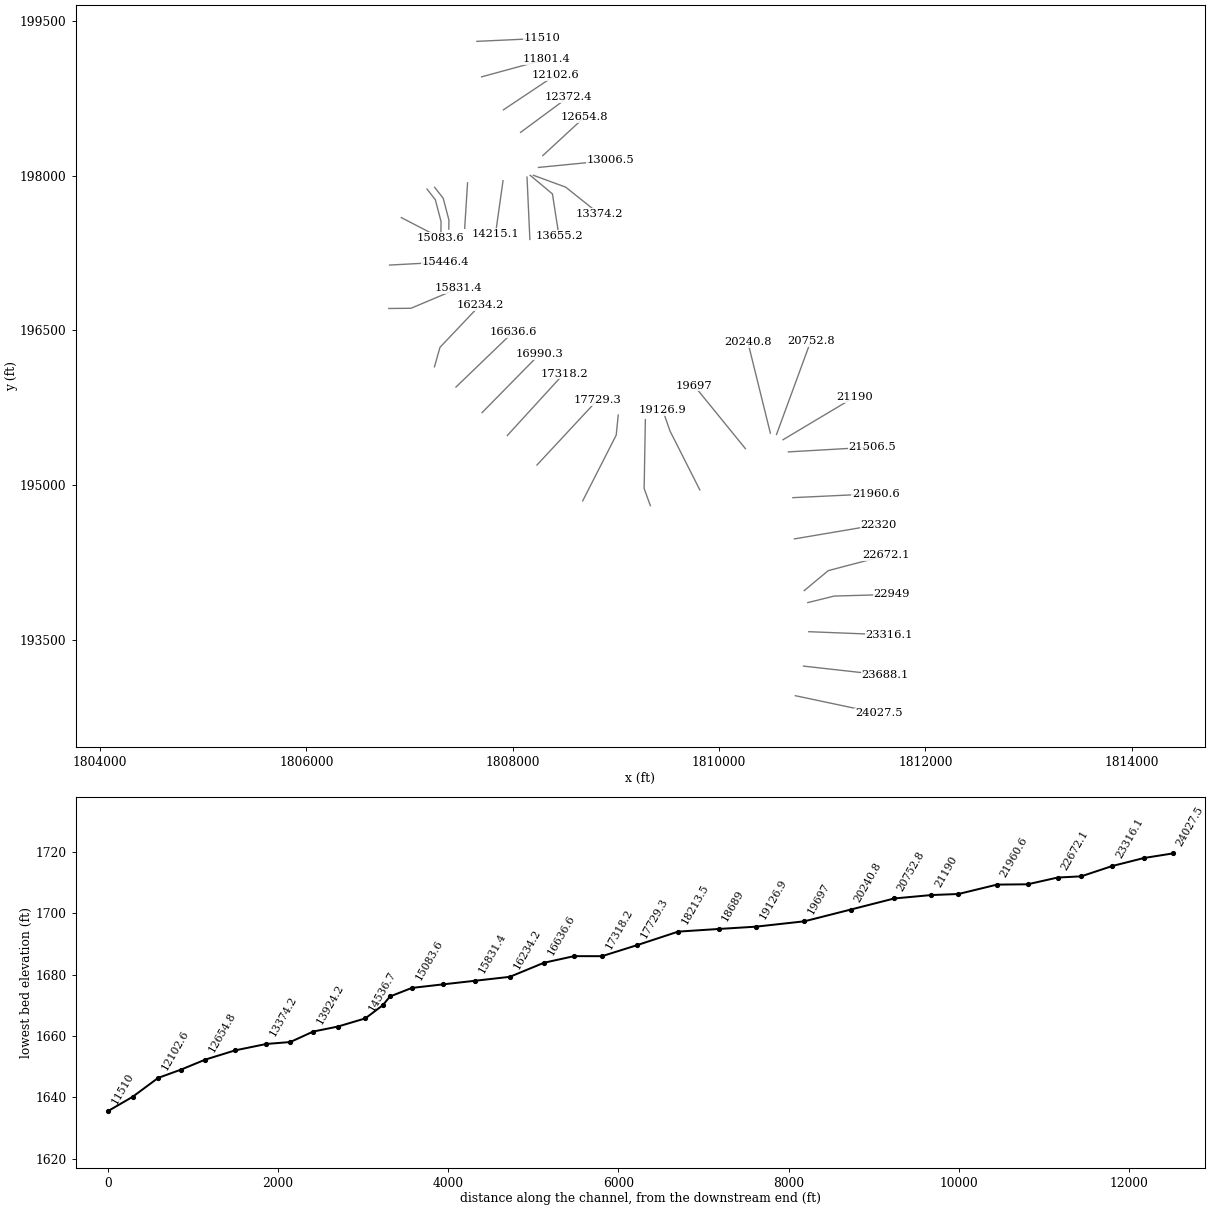
HEC-RAS study MIDFKRV2.prj: MIDFKRV2

--- MIDFKRV2.g01 (geometry) --- (continued)

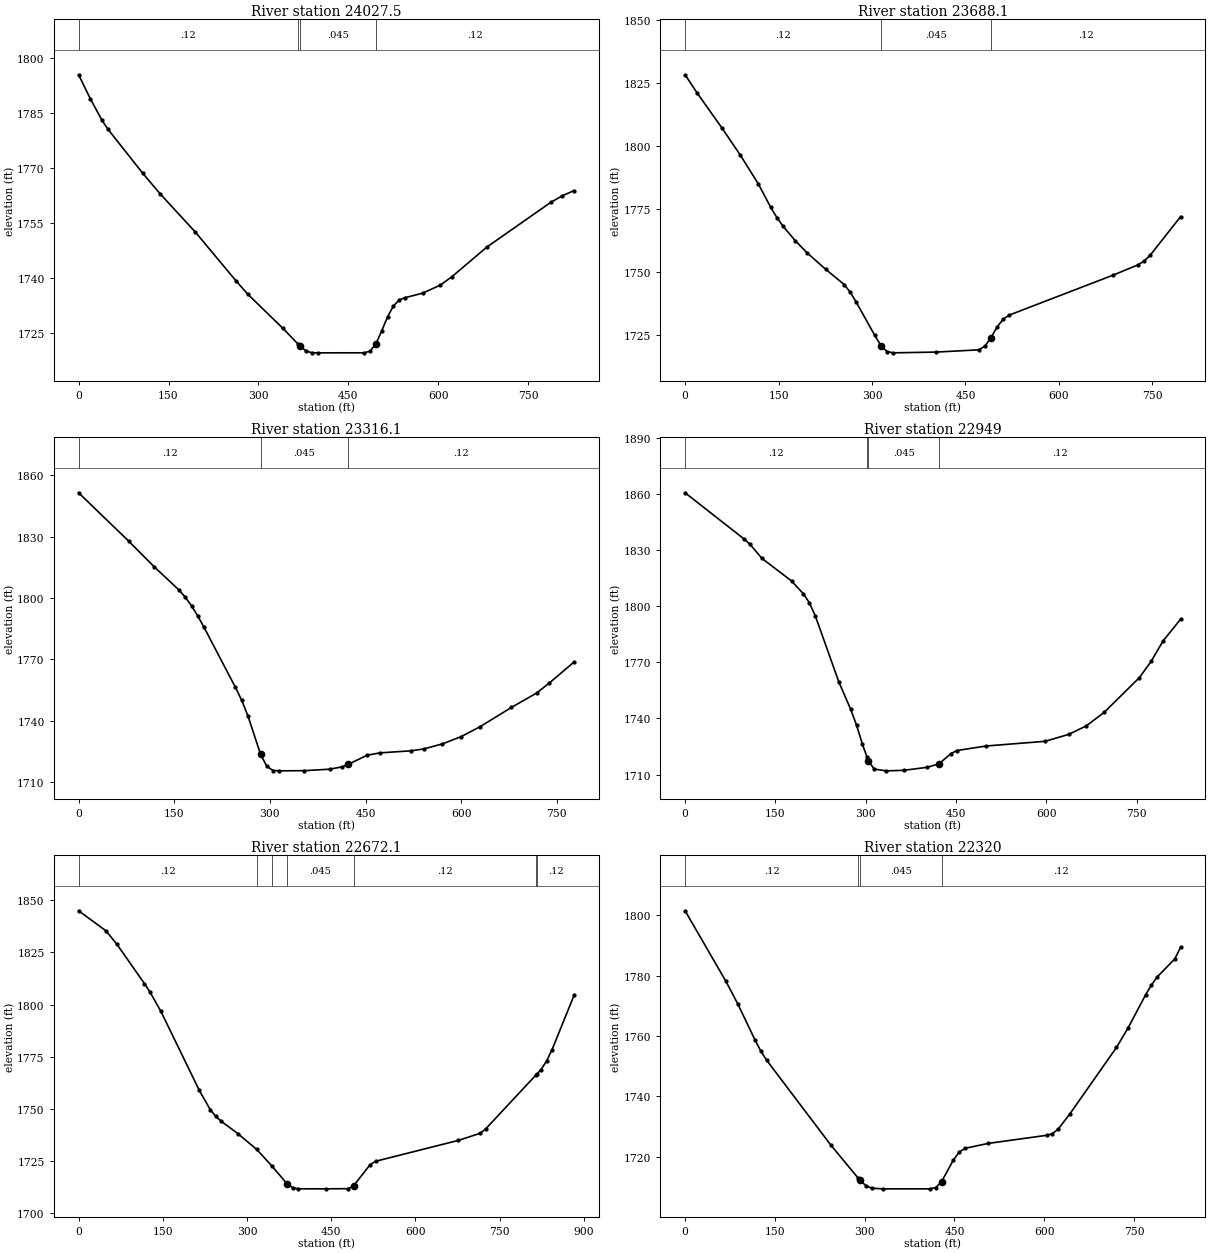
Type RM Length L Ch R = 1 ,24027.5 ,335.7,339.4,343
XS GIS Cut Line= 2
     1810739.963      192961.049     1811549.162      192789.872
#Sta/Elev= 30
       0 1795.34    19.5  1788.8    38.9 1782.95    48.6 1780.56     107 1768.47
   136.2 1762.84   194.6 1752.47   262.7 1739.12   282.2 1735.51   340.6 1726.22
   365.41722.031   369.8 1721.29   379.5 1720.02   389.2 1719.51     399 1719.49
   476.8  1719.5   486.5 1719.96   496.3    1722     506 1725.53   515.7 1729.34
   525.5 1732.31   535.2 1733.92   544.9 1734.55   574.1 1735.76   603.3 1737.94
   622.8 1740.22   681.2 1748.32   788.2 1760.56   807.6 1762.36   827.1 1763.76
#Mann= 4 ,-1 , 0
       0     .12       0   365.4     .08       0   369.8    .045       0
   496.3     .12       0
Bank Sta=369.8,496.3
XS Rating Curve= 0 ,0
Exp/Cntr=0.3,0.1

Type RM Length L Ch R = 1 ,23688.1 ,369,372,374.9
XS GIS Cut Line= 2
     1810818.512      193247.811     1811608.869       193159.49
#Sta/Elev= 30
       0 1828.36    19.6 1821.04    58.9 1807.33    88.4 1796.57   117.8 1784.94
   137.5  1775.7   147.3 1771.69   157.1  1768.3   176.7 1762.54   196.4 1757.55
   225.8 1751.12   255.3  1745.1   265.1 1742.07   274.9    1738   304.4 1724.94
   314.2 1720.91     324 1718.52   333.8    1718   402.6  1718.3   471.3 1719.19
   481.1 1720.62   490.9 1724.04   500.7 1728.24   510.6  1731.4   520.4    1733
   687.3 1748.88   726.6 1752.89   736.4 1754.37   746.2 1756.68   795.3 1772.06
#Mann= 3 ,-1 , 0
       0     .12       0   314.2    .045       0   490.9     .12       0
Bank Sta=314.2,490.9
XS Rating Curve= 0 ,0
Exp/Cntr=0.3,0.1

Type RM Length L Ch R = 1 ,23316.1 ,364.3,367.1,369.8
XS GIS Cut Line= 2
     1810869.851      193581.227     1811646.553      193550.552
#Sta/Elev= 30
       0 1851.49    78.7 1827.77   118.1 1815.39   157.4 1803.93   167.3 1800.39
   177.1 1796.14     187 1791.14   196.8 1785.59     246 1756.22   255.8 1749.93
   265.7 1742.15   285.3 1723.58   295.2  1717.6     305 1715.56   314.9  1715.4
   354.2 1715.49   393.6  1716.2   413.2 1717.33   423.1 1718.62   452.6 1723.04
   472.3 1724.19   521.5 1725.21   541.2 1726.11   570.7 1728.59   600.2 1732.18
   629.7    1737   678.9 1746.43   718.3 1753.46     738  1758.3   777.3 1768.72
#Mann= 3 ,-1 , 0
       0     .12       0   285.3    .045       0   423.1     .12       0
Bank Sta=285.3,423.1
XS Rating Curve= 0 ,0
Exp/Cntr=0.3,0.1

Type RM Length L Ch R = 1 ,22949   ,268.2,276.9,285.4
XS GIS Cut Line= 3
      1810859.96      193863.187     1811117.311      193926.564
       1811674.9      193942.256
#Sta/Elev= 30
       0 1860.58    98.2 1835.82     108 1832.97   127.6 1825.52   176.7 1813.48
   196.3 1806.64   206.1 1801.95     216 1795.01   255.2 1759.59   274.8 1744.98
   284.6 1736.48   294.4 1726.32   301.81719.554   304.2 1717.36     314 1712.98
   333.5 1712.02   362.9 1712.29     402  1713.9   421.6 1715.78   441.2 1721.15
     451 1722.86   499.9 1725.29   597.8  1727.8   636.9 1731.49   666.3 1736.06
   695.6  1743.2   754.4 1761.85   773.9 1770.56   793.5 1781.36   822.8 1793.08
#Mann= 4 ,-1 , 0
       0     .12       0   301.8     .08       0   304.2    .045       0
   421.6     .12       0
Bank Sta=304.2,421.6
XS Rating Curve= 0 ,0
Exp/Cntr=0.3,0.1

Type RM Length L Ch R = 1 ,22672.1 ,355.5,352.2,348.8
XS GIS Cut Line= 3
     1810825.273      193979.208     1811058.343      194172.865
     1811619.254       194320.25
#Sta/Elev= 30
       0 1844.98    48.9 1835.33    68.4 1828.85   117.3 1810.05   127.1 1806.06
   146.6 1796.73     215 1758.86   234.6 1749.57   244.4 1746.37   254.2 1744.01
   283.5 1738.16  317.371730.521  343.861722.739   371.8 1713.92   381.7 1712.14
   391.5 1711.64   440.6 1711.63     480 1711.72   489.8 1713.08   519.3 1723.17
   529.1 1724.84   676.6 1734.86   715.9  1738.3   725.7 1740.48  815.051766.262
   817.11766.846     824 1768.81   833.8 1772.92   843.7 1778.44     883 1804.57
#Mann= 7 ,-1 , 0
       0     .12       0  317.37    .016       0  343.86     .12       0
   371.8    .045       0   489.8     .12       0  815.05    .016       0
   817.1     .12       0
Bank Sta=371.8,489.8
XS Rating Curve= 0 ,0
Exp/Cntr=0.3,0.1

Type RM Length L Ch R = 1 ,22320   ,363.9,359.3,354.8
XS GIS Cut Line= 2
     1810730.747      194480.413     1811546.986      194618.648
#Sta/Elev= 30
       0 1801.47    68.2 1778.12    87.7 1770.77   116.9 1758.67   126.6 1754.98
   136.4 1751.96   243.5 1723.91  289.631712.857   292.2 1712.28   301.9 1710.51
   311.7 1709.63   331.1 1709.43   409.1 1709.43   418.8 1709.87   428.5  1711.8
     448  1718.9   457.8 1721.56   467.5 1722.83   506.5 1724.47   603.8 1727.14
   613.6 1727.68   623.3 1729.19   642.8 1734.23   720.7 1756.22   740.2 1762.73
   769.4 1773.67   779.2 1776.91   788.9 1779.61   818.1 1785.53   827.9 1789.41
#Mann= 4 ,-1 , 0
       0     .12       0  289.63     .08       0   292.2    .045       0
   428.5     .12       0
Bank Sta=292.2,428.5
XS Rating Curve= 0 ,0
Exp/Cntr=0.3,0.1

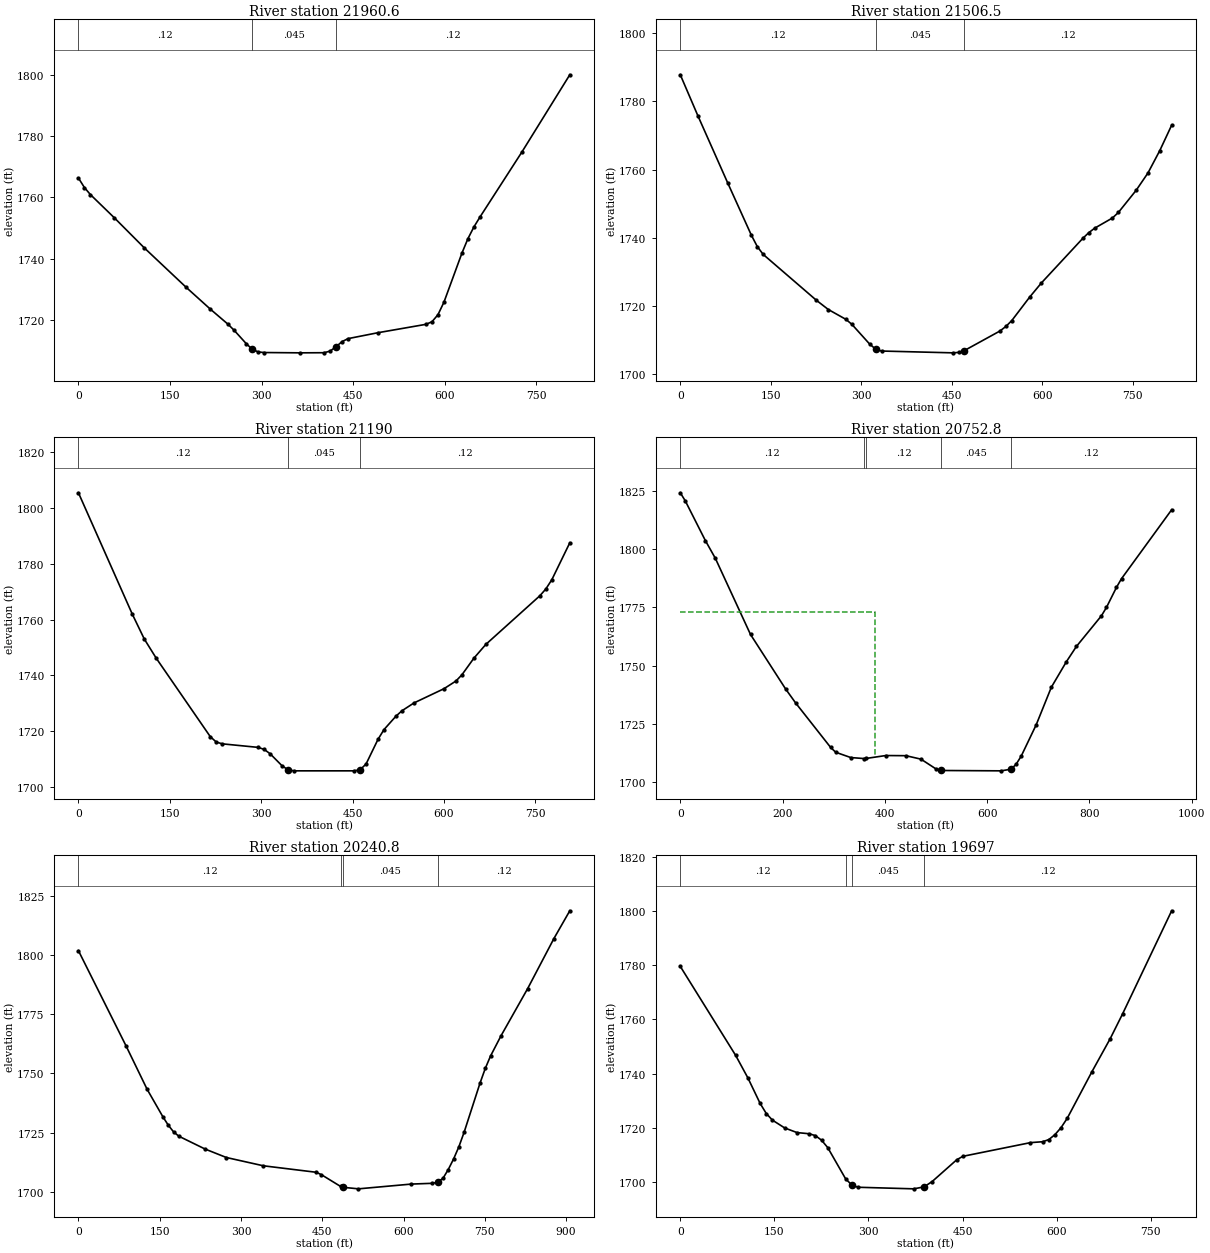
Type RM Length L Ch R = 1 ,21960.6 ,453.7,454.1,454.5
XS GIS Cut Line= 2
     1810715.396      194879.949     1811519.608      194917.692
#Sta/Elev= 30
       0 1766.28     9.8 1763.19    19.6 1760.89    58.9 1753.31     108 1743.51
   176.7 1730.64     216 1723.59   245.5 1718.58   255.3 1716.64   274.9 1712.34
   284.7 1710.51   294.6 1709.61   304.4 1709.43   363.3 1709.33   402.6 1709.37
   412.4  1709.9   422.2 1711.35     432 1712.99   441.8 1713.96   490.9 1715.89
   569.5 1718.62   579.3 1719.46   589.1 1721.75   598.9 1725.83   628.4 1741.83
   638.2 1746.53     648 1750.34   657.8 1753.53   726.6 1774.74   805.1 1799.91
#Mann= 3 ,-1 , 0
       0     .12       0   284.7    .045       0   422.2     .12       0
Bank Sta=284.7,422.2
XS Rating Curve= 0 ,0
Exp/Cntr=0.3,0.1

Type RM Length L Ch R = 1 ,21506.5 ,298.4,316.5,334.8
XS GIS Cut Line= 2
     1810672.522      195323.404     1811485.848       195370.08
#Sta/Elev= 30
       0 1787.76    29.4 1775.65    78.5 1756.11   117.8 1740.76   127.6 1737.43
   137.4 1735.12   225.8 1721.65   245.4 1718.97   274.8 1716.06   284.6  1714.6
   314.1 1708.81   323.9 1707.37   333.7  1706.8   451.5 1706.27   461.3 1706.39
   471.1 1706.95     530 1712.67   539.8    1714   549.6 1715.72   579.1 1722.57
   598.7 1726.75   667.4 1739.83   677.2 1741.48   687.1 1742.81   716.5 1745.79
   726.3  1747.4   755.8  1753.9   775.4 1758.98     795 1765.54   814.7 1772.99
#Mann= 3 ,-1 , 0
       0     .12       0   323.9    .045       0   471.1     .12       0
Bank Sta=323.9,471.1
XS Rating Curve= 0 ,0
Exp/Cntr=0.3,0.1

Type RM Length L Ch R = 1 ,21190   ,405.3,437.2,468.2
XS GIS Cut Line= 2
     1810620.534      195441.476     1811313.245      195854.822
#Sta/Elev= 30
       0 1805.28    88.5 1761.89   108.2    1753   127.9 1746.12   216.4 1718.17
   226.3 1716.22   236.1 1715.58   295.1 1714.31     305 1713.58   314.8 1712.02
   334.5 1707.69   344.3 1706.29   354.1 1705.93   452.5 1705.93   462.4 1706.32
   472.2 1708.36   491.9 1717.21   501.7 1720.68   521.4 1725.48   531.2  1727.4
   550.9 1730.19   600.1 1735.27   619.8 1738.02   629.6 1740.24   649.3 1746.19
   668.9 1751.11   757.5 1768.47   767.3 1770.89   777.2 1774.21   806.7  1787.4
#Mann= 3 ,-1 , 0
       0     .12       0   344.3    .045       0   462.4     .12       0
Bank Sta=344.3,462.4
XS Rating Curve= 0 ,0
Exp/Cntr=0.3,0.1

Type RM Length L Ch R = 1 ,20752.8 ,501.9,512,525.1
XS GIS Cut Line= 2
     1810556.811       195492.23     1810887.963      196394.226
#Sta/Elev= 30
       0 1824.18     9.8 1820.68      49 1803.68    68.6 1796.02   137.3 1763.36
   205.9 1739.98   225.5 1733.97   294.1 1714.84     304 1712.79   333.4 1710.52
  359.431710.092  363.471710.148     402 1711.39   441.2 1711.32   470.6 1709.84
     500 1705.64   509.8 1704.97   627.5 1704.82   647.1 1705.54   656.9 1707.71
   666.7 1711.15   696.1 1724.64   725.6 1740.71     755 1751.66   774.6 1758.21
   823.6 1771.39   833.4 1774.98     853 1783.59   862.8  1787.3   960.9  1816.9
#Mann= 5 ,-1 , 0
       0     .12       0  359.43     .06       0  363.47     .12       0
   509.8    .045       0   647.1     .12       0
#XS Ineff= 2 , 0
          381.57  1772.8
Permanent Ineff=
       F       F
Bank Sta=509.8,647.1
XS Rating Curve= 0 ,0
Exp/Cntr=0.3,0.1

Type RM Length L Ch R = 1 ,20240.8 ,521.5,543.8,564.4
XS GIS Cut Line= 2
     1810497.086      195505.099     1810279.486      196385.389
#Sta/Elev= 30
       0 1801.84    87.8 1761.64   126.8 1743.25     156 1731.59   165.8 1728.11
   175.5 1725.29   185.3 1723.44     234 1717.99     273 1714.44   341.3 1710.94
   438.8  1708.2   448.5 1707.17  483.931702.201   487.5 1701.87   516.8  1701.2
   614.3 1703.21   653.3 1703.54     663    1704   672.8 1705.65   682.5 1709.35
   692.3 1713.79     702 1718.91   711.8 1725.12     741 1745.79   750.8 1752.06
   760.5 1757.31     780 1765.92   828.8 1785.71   877.5 1806.96   906.8 1818.69
#Mann= 4 ,-1 , 0
       0     .12       0  483.93     .04       0   487.5    .045       0
     663     .12       0
Bank Sta=487.5,663
XS Rating Curve= 0 ,0
Exp/Cntr=0.3,0.1

Type RM Length L Ch R = 1 ,19697   ,577.1,570.1,562.3
XS GIS Cut Line= 2
     1810255.207      195354.806     1809760.783      195962.658
#Sta/Elev= 30
       0  1779.6    88.2 1746.74   107.7 1738.42   127.3 1728.95   137.1 1725.23
   146.9 1722.78   166.5 1719.88   186.1 1718.18   205.7 1717.74   215.5 1717.04
   225.3 1715.35   235.1 1712.62  263.691701.047   274.2 1698.65     284 1697.96
   372.2 1697.38  388.741698.107   401.6 1700.08   440.7 1708.11   450.5  1709.4
   558.3 1714.46   577.9  1714.8   587.7  1715.6   597.4 1717.42   607.2 1720.03
     617 1723.47   656.2 1740.61   685.6 1752.94   705.2 1762.04   783.5 1800.17
#Mann= 4 ,-1 , 0
       0     .12       0  263.69     .04       0   274.2    .045       0
  388.74     .12       0
Bank Sta=274.2,388.74
XS Rating Curve= 0 ,0
Exp/Cntr=0.3,0.1

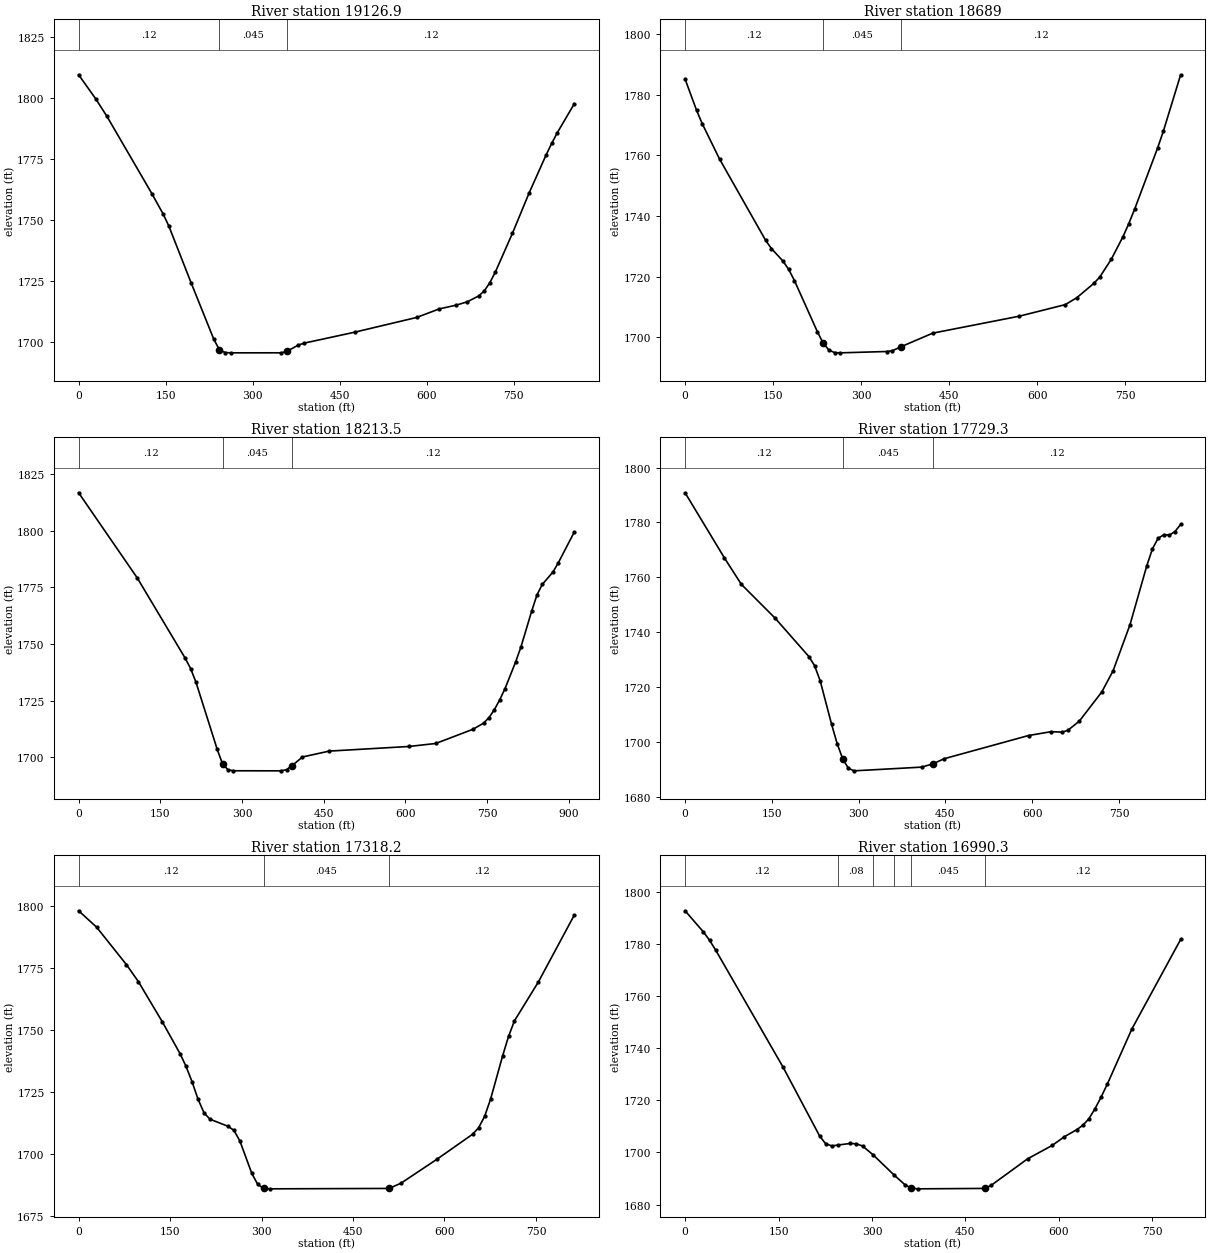
Type RM Length L Ch R = 1 ,19126.9 ,456.5,437.9,419.4
XS GIS Cut Line= 3
     1809812.985      194955.527     1809523.561      195527.259
     1809453.793      195728.588
#Sta/Elev= 30
       0 1809.43    29.1  1799.7    48.6 1792.49   126.2 1760.79   145.6 1752.46
   155.4 1747.54   194.2 1724.06     233 1701.15   242.7 1696.86   252.4 1695.76
   262.2 1695.63   349.5 1695.64   359.2 1696.28   378.7 1698.83   388.4 1699.59
   475.8 1704.09   582.6 1710.12   621.4 1713.61   650.5 1715.14   669.9 1716.53
   689.2 1718.89   698.9 1720.96   708.6 1724.33   718.3 1728.82   747.4 1744.49
   776.4 1761.13   805.5  1776.6   815.2 1781.36   824.8 1785.72   853.9 1797.48
#Mann= 3 ,-1 , 0
       0     .12       0   242.7    .045       0   359.2     .12       0
Bank Sta=242.7,359.2
XS Rating Curve= 0 ,0
Exp/Cntr=0.3,0.1

Type RM Length L Ch R = 1 ,18689   ,492.3,475.5,458.7
XS GIS Cut Line= 3
     1809333.885      194802.339     1809273.561      194968.231
     1809285.435      195636.169
#Sta/Elev= 30
       0 1785.11    19.6  1774.8    29.4 1770.34    58.8 1758.73   137.3 1731.95
   147.1 1729.27   166.7 1725.15   176.5 1722.41   186.3 1718.72   225.6 1701.78
   235.5 1698.01   245.3 1695.75   255.1 1694.95  264.85 1694.88   343.5 1695.32
   353.4 1695.59  368.251696.911   422.1 1701.37   569.5 1706.96   648.1 1710.78
   667.7 1713.06   697.2 1717.87     707 1719.92   726.7 1725.83   746.3 1733.16
   756.2 1737.45     766 1742.15   805.3 1762.38   815.1 1767.91   844.6 1786.54
#Mann= 3 ,-1 , 0
       0     .12       0   235.5    .045       0  368.25     .12       0
Bank Sta=235.5,368.25
XS Rating Curve= 0 ,0
Exp/Cntr=0.3,0.1

Type RM Length L Ch R = 1 ,18213.5 ,494.7,484.2,473.7
XS GIS Cut Line= 3
     1808678.109      194849.035     1809002.727      195485.592
     1809022.487      195680.047
#Sta/Elev= 30
       0 1816.65   107.7 1779.08   195.8 1743.65   205.6 1739.15   215.3 1733.23
   254.5 1703.49   264.3 1697.04   274.1 1694.52   283.9 1694.05     372 1694.02
   381.8 1694.54   391.5 1696.24   411.1 1700.13     460 1702.72   606.9 1704.77
   655.8 1706.09   724.3 1712.36   743.9  1715.1   753.6 1717.52   763.4 1720.98
   773.2 1725.28     783 1730.29   802.5 1742.05   812.3 1748.69   831.8 1764.33
   841.6 1771.55   851.4 1776.22   870.9 1781.66   880.7 1785.69     910 1799.25
#Mann= 3 ,-1 , 0
       0     .12       0   264.3    .045       0   391.5     .12       0
Bank Sta=264.3,391.5
XS Rating Curve= 0 ,0
Exp/Cntr=0.3,0.1

Type RM Length L Ch R = 1 ,17729.3 ,410.8,411.1,411.4
XS GIS Cut Line= 2
     1808234.824        195196.4     1808818.395      195823.436
#Sta/Elev= 30
       0 1790.81    68.1 1767.05    97.3 1757.47   155.7 1745.15   214.2 1731.14
   223.9 1727.85   233.6  1722.3   253.1 1706.63   262.8 1699.54   272.6 1693.87
   282.3 1690.54     292  1689.6   408.8 1690.95   428.3 1692.13   447.8 1694.01
   593.8 1702.46   632.7 1703.85   652.2  1703.7   661.9 1704.38   681.4 1707.68
   720.3 1718.31   739.8    1726     769 1742.75   798.2 1764.32   807.9 1770.43
   817.6 1774.22   827.4 1775.54   837.1 1775.41   846.8  1776.7   856.6  1779.3
#Mann= 3 ,-1 , 0
       0     .12       0   272.6    .045       0   428.3     .12       0
Bank Sta=272.6,428.3
XS Rating Curve= 0 ,0
Exp/Cntr=0.3,0.1

Type RM Length L Ch R = 1 ,17318.2 ,329.1,327.9,326.6
XS GIS Cut Line= 2
     1807947.367      195482.288     1808495.843       196081.99
#Sta/Elev= 30
       0 1798.07    29.4 1791.48    78.3 1776.41    97.9 1769.56   137.1 1753.37
   166.5 1740.42   176.2 1735.34     186 1729.16   195.8 1722.18   205.6 1716.65
   215.4 1714.08   244.8 1711.24   254.6 1709.62   264.4 1705.34     284 1692.25
   293.7 1687.82   303.5 1686.16   313.3 1686.02   509.2 1686.18   528.7  1688.3
   587.5 1697.92   646.2 1708.04     656 1710.63   665.8 1715.21   675.6 1722.16
   695.2 1739.47     705 1747.42   714.8 1753.75   753.9 1769.35   812.7 1796.25
#Mann= 3 ,-1 , 0
       0     .12       0   303.5    .045       0   509.2     .12       0
Bank Sta=303.5,509.2
XS Rating Curve= 0 ,0
Exp/Cntr=0.3,0.1

Type RM Length L Ch R = 1 ,16990.3 ,354.7,353.6,352.4
XS GIS Cut Line= 2
      1807702.92       195704.22      1808260.89      196271.438
#Sta/Elev= 30
       0  1792.9    29.5 1784.74    39.3 1781.55    49.1 1777.78   157.2 1732.84
   216.1 1706.29   225.9 1703.29   235.8 1702.53  245.531702.868   265.2 1703.48
     275 1703.33   284.9 1702.49  302.371698.983  335.171691.427   353.6 1687.47
   363.4 1686.33   373.3 1686.03   481.3 1686.19   491.1 1687.32   550.1  1697.6
   589.4 1702.71     609 1706.07   628.7 1708.75   638.5 1710.45   648.3 1712.96
   658.1 1716.81     668 1721.33   677.8 1726.24   717.1 1747.37   795.6 1781.87
#Mann= 6 ,-1 , 0
       0     .12       0  245.53     .08       0  302.37     .12       0
  335.17     .08       0   363.4    .045       0   481.3     .12       0
Bank Sta=363.4,481.3
XS Rating Curve= 0 ,0
Exp/Cntr=0.3,0.1

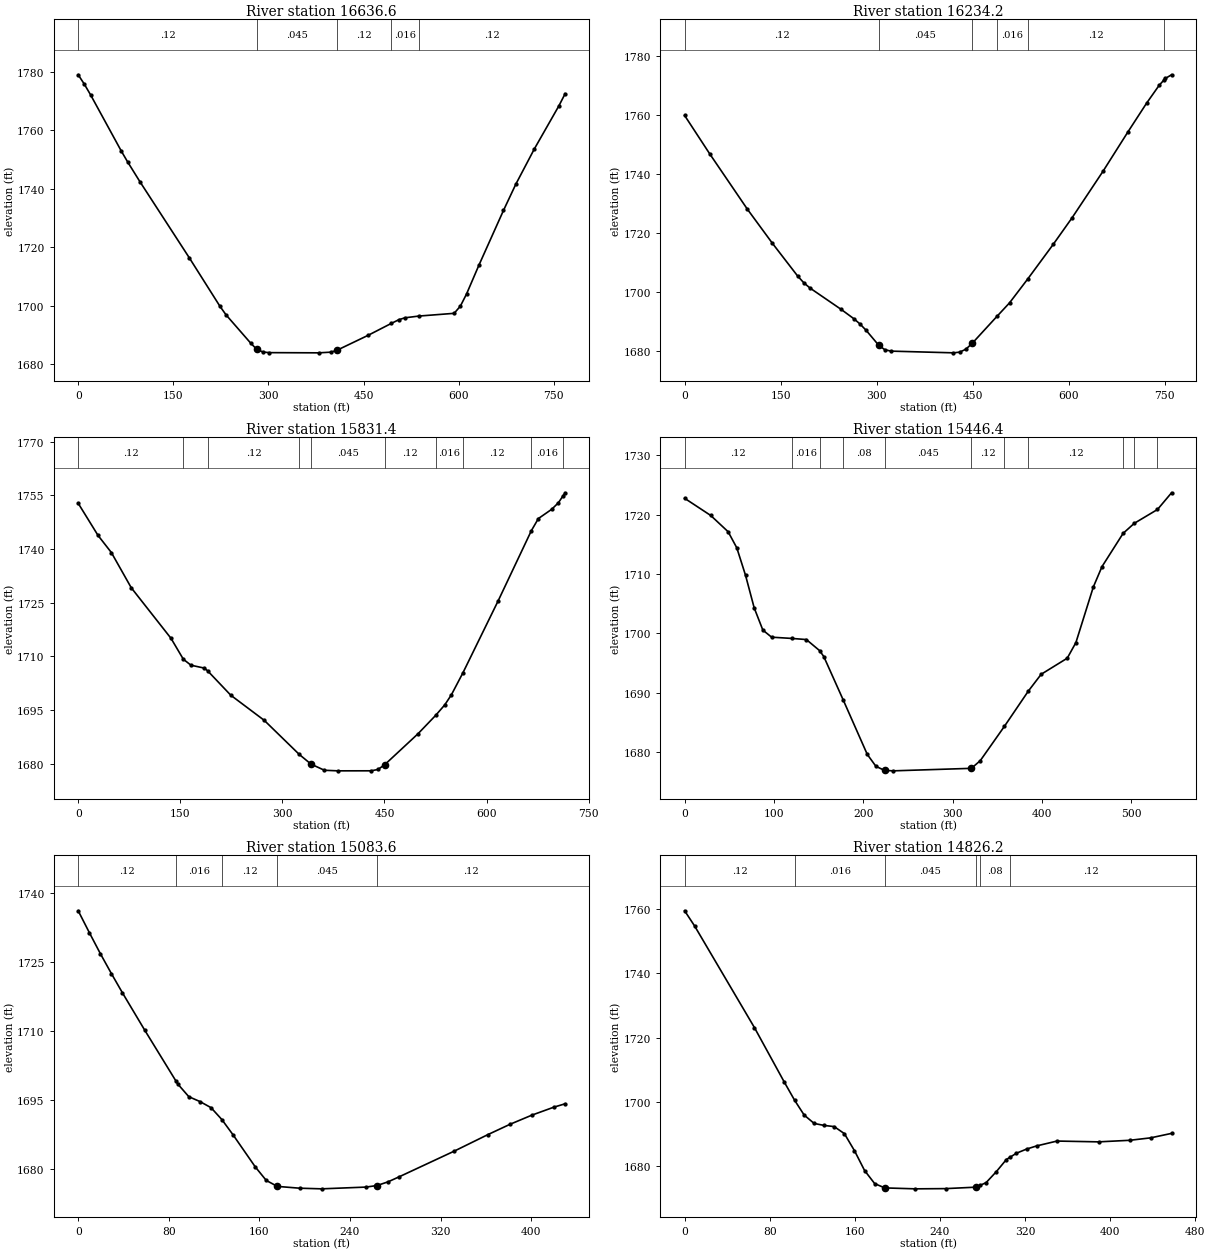
Type RM Length L Ch R = 1 ,16636.6 ,401,402.5,403.9
XS GIS Cut Line= 2
     1807449.422      195951.581     1808002.735      196483.844
#Sta/Elev= 30
       0 1778.89     9.7 1775.67    19.4 1772.08      68 1752.81    77.8 1749.17
    97.2  1742.4   174.9 1716.45   223.5 1699.79   233.2 1696.84   272.1 1687.17
   281.8 1685.03   291.6 1684.15   301.3 1683.95     379 1683.88   398.5 1684.11
   408.2 1684.78   456.8 1689.83  493.551693.918   505.4 1695.18   515.1 1695.85
  537.36 1696.45   592.8 1697.38   602.6 1699.83   612.3 1703.96   631.7 1713.75
   670.6 1732.54     690 1741.48   719.2 1753.53     758 1768.28   767.8 1772.42
#Mann= 5 ,-1 , 0
       0     .12       0   281.8    .045       0   408.2     .12       0
  493.55    .016       0  537.36     .12       0
Bank Sta=281.8,408.2
XS Rating Curve= 0 ,0
Exp/Cntr=0.3,0.1

Type RM Length L Ch R = 1 ,16234.2 ,418.2,402.8,387.5
XS GIS Cut Line= 3
     1807240.793       196147.61     1807294.394      196336.286
     1807683.283      196746.009
#Sta/Elev= 30
       0 1759.86    39.2 1746.84    98.1 1728.04   137.3 1716.44   176.5  1705.4
   186.3 1703.06   196.1 1701.26   244.8 1694.01   264.3  1690.9   274.1 1689.08
   283.8  1686.9   303.3 1681.87     313 1680.33   322.8 1679.87   420.2 1679.29
   429.9 1679.53   439.6 1680.53   449.4 1682.51  488.511691.757   507.8 1696.26
  535.94 1704.28     576 1716.09   605.2 1725.03   653.9 1740.93   692.9 1754.31
   722.1 1764.08   741.6 1770.09  749.041771.892   751.3 1772.44     761 1773.68
#Mann= 6 ,-1 , 0
       0     .12       0   303.3    .045       0   449.4     .12       0
  488.51    .016       0  535.94     .12       0  749.04    .016       0
Bank Sta=303.3,449.4
XS Rating Curve= 0 ,0
Exp/Cntr=0.3,0.1

Type RM Length L Ch R = 1 ,15831.4 ,397.9,384.9,371.9
XS GIS Cut Line= 3
     1806798.755      196712.677     1807013.144      196714.759
      1807474.95      196909.203
#Sta/Elev= 30
       0 1752.75    29.2 1743.76    48.7 1739.01      78 1729.15   136.4 1715.03
  154.491709.199   165.7 1707.53   185.2 1706.73  190.161705.968   224.2 1699.15
   273.4 1692.13  324.881682.607   342.1 1679.91   361.8 1678.19   381.4 1678.03
   430.6 1678.04   440.4 1678.41   450.2 1679.71   499.3 1688.38  525.291693.527
   538.6 1696.44   548.4 1699.27  565.251705.375   617.2 1725.55   665.91745.109
   676.2 1748.49   695.8 1751.08   705.6  1752.9  712.691754.898   715.5 1755.69
#Mann= 10 ,-1 , 0
       0     .12       0  154.49    .016       0  190.16     .12       0
  324.88     .08       0   342.1    .045       0   450.2     .12       0
  525.29    .016       0  565.25     .12       0   665.9    .016       0
  712.69     .12       0
Bank Sta=342.1,450.2
XS Rating Curve= 0 ,0
Exp/Cntr=0.3,0.1

Type RM Length L Ch R = 1 ,15446.4 ,382.8,362.8,342.8
XS GIS Cut Line= 2
     1806805.506      197133.404      1807349.95      197162.675
#Sta/Elev= 30
       0 1722.73    29.2 1719.84    48.7  1717.1    58.4 1714.39    68.2 1709.76
    77.9 1704.27    87.6 1700.53    97.4 1699.34  120.261699.128   136.3 1698.94
  151.131697.076   155.8 1696.08  177.751688.705   204.5  1679.6   214.2 1677.59
   223.9  1676.9   233.7 1676.83  321.081677.252     331 1678.54  357.941684.299
  384.811690.257   399.2 1693.09   428.4  1695.8   438.1 1698.43   457.6 1707.79
   467.3 1711.22  490.971716.826  503.461718.515  529.451720.847   545.2 1723.66
#Mann= 11 ,-1 , 0
       0     .12       0  120.26    .016       0  151.13     .12       0
  177.75     .08       0   223.9    .045       0  321.08     .12       0
  357.94     .08       0  384.81     .12       0  490.97     .08       0
  503.46    .016       0  529.45     .12       0
Bank Sta=223.9,321.08
XS Rating Curve= 0 ,0
Exp/Cntr=0.3,0.1

Type RM Length L Ch R = 1 ,15083.6 ,288.9,257.4,222
XS GIS Cut Line= 2
     1806919.394      197593.231     1807301.425      197395.835
#Sta/Elev= 28
       0  1736.1     9.8 1731.37    19.6 1726.77    29.3 1722.46    39.1 1718.26
    58.6 1710.22   86.551699.014      88 1698.44    97.7  1695.7   107.5 1694.65
   117.3 1693.32  126.831690.746   136.8  1687.4   156.4 1680.44   166.1  1677.5
   175.9 1676.21   195.5 1675.82     215 1675.68   254.1 1676.06   263.9  1676.4
   273.6  1677.2   283.4 1678.29   332.3  1683.9   361.6 1687.44   381.2 1689.69
   400.7  1691.7   420.2 1693.44     430 1694.16
#Mann= 5 ,-1 , 0
       0     .12       0   86.55    .016       0  126.83     .12       0
   175.9    .045       0   263.9     .12       0
Bank Sta=175.9,263.9
XS Rating Curve= 0 ,0
Exp/Cntr=0.3,0.1

Type RM Length L Ch R = 1 ,14826.2 ,81.5,84.6,95.7
XS GIS Cut Line= 4
     1807168.249      197869.941     1807249.255      197766.842
     1807304.811      197555.036     1807303.336       197447.37
#Sta/Elev= 30
       0 1759.48     9.4 1754.74    65.6 1723.12    93.6 1706.19  103.461700.444
   112.4 1695.86   121.8 1693.25   131.1 1692.64   140.6 1692.27   150.2 1690.08
   159.7 1684.76   169.2 1678.59   178.7 1674.51   188.2 1673.18   216.8 1672.89
   245.4 1672.96   273.9 1673.41  277.511673.942   283.4 1674.81     293 1678.22
   302.5 1682.02  305.621682.667     312 1683.99   321.5 1685.27     331 1686.26
   350.1 1687.77   389.2 1687.52   418.6 1688.01   438.2 1688.77   457.8 1690.16
#Mann= 6 ,-1 , 0
       0     .12       0  103.46    .016       0   188.2    .045       0
   273.9     .12       0  277.51     .08       0  305.62     .12       0
Bank Sta=188.2,273.9
XS Rating Curve= 0 ,0
Exp/Cntr=0.3,0.1

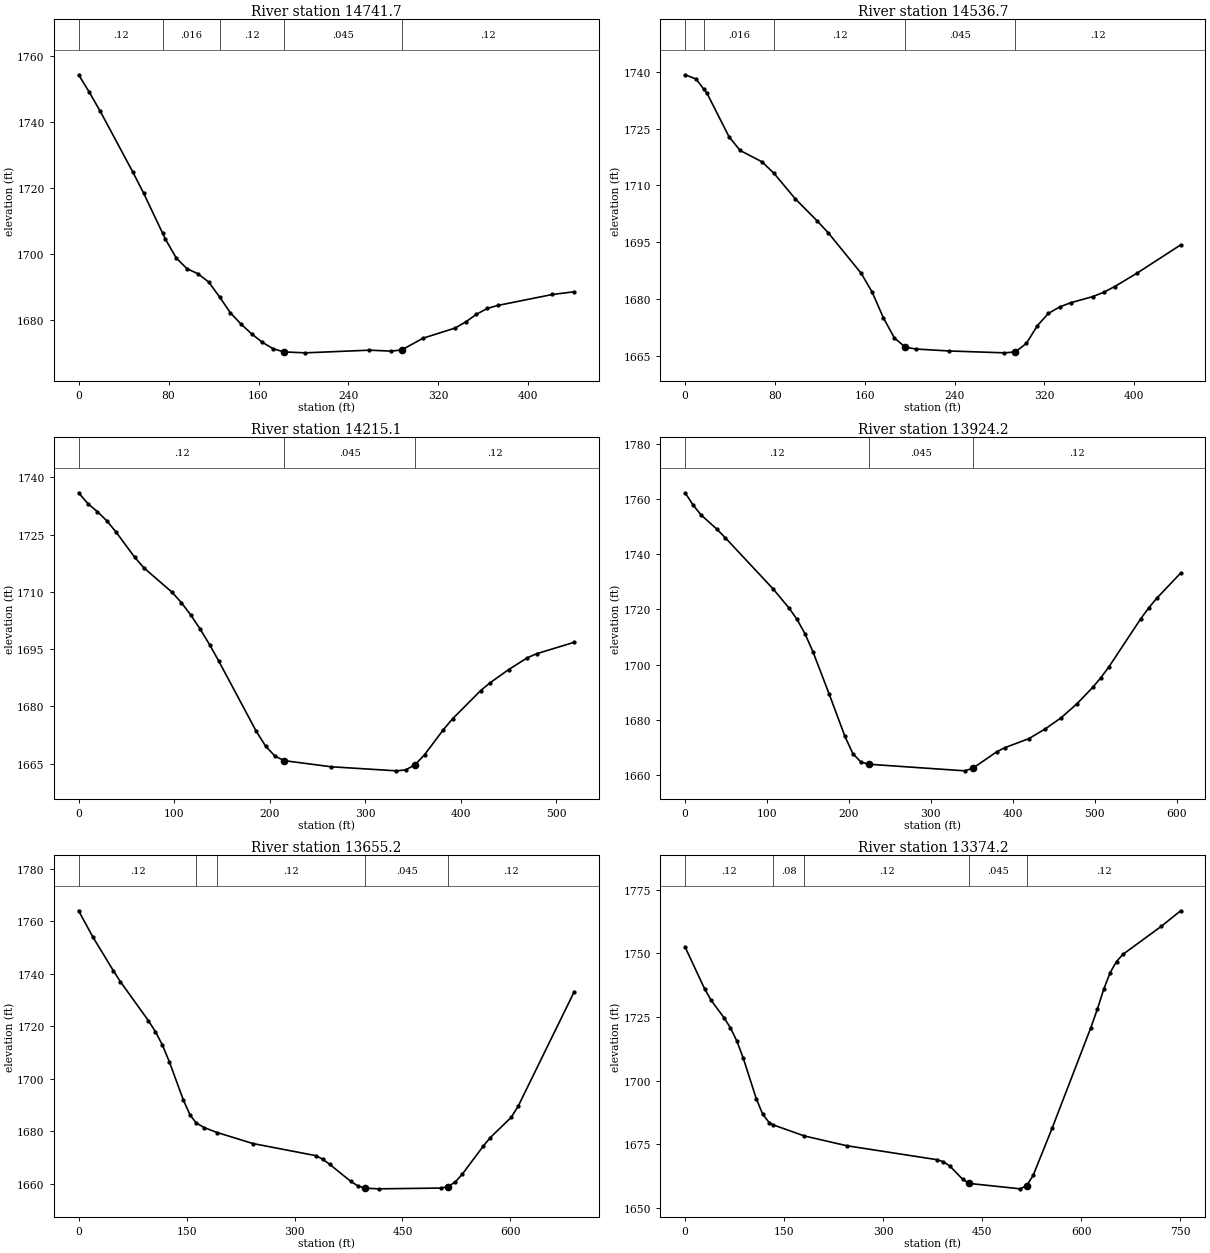
Type RM Length L Ch R = 1 ,14741.7 ,219.4,205,184.9
XS GIS Cut Line= 4
     1807242.259      197886.858     1807325.644      197780.731
       1807381.2      197568.925      1807380.01      197482.089
#Sta/Elev= 30
       0 1754.35     9.6    1749    19.3 1743.24    48.2 1724.86    57.8 1718.46
    74.81706.247    77.1 1704.58    86.8  1698.8    96.4 1695.53     106 1694.05
   115.7 1691.51  125.52 1686.91     135 1682.17   144.5 1678.73     154 1675.76
   163.5 1673.21     173 1671.28   182.6 1670.31   201.6 1670.03   258.7 1670.84
   277.8 1670.55   287.3  1670.9   306.3 1674.46   334.9 1677.55   344.4 1679.42
   353.9 1681.73   363.6 1683.52   373.2 1684.43   421.5 1687.73   440.8 1688.55
#Mann= 5 ,-1 , 0
       0     .12       0    74.8    .016       0  125.52     .12       0
   182.6    .045       0   287.3     .12       0
Bank Sta=182.6,287.3
XS Rating Curve= 0 ,0
Exp/Cntr=0.3,0.1

Type RM Length L Ch R = 1 ,14536.7 ,324.9,321.6,319.1
XS GIS Cut Line= 2
     1807561.755      197930.036     1807533.839      197489.575
#Sta/Elev= 30
       0 1739.21     9.8 1738.09    16.81735.361    19.6 1734.27    39.2 1722.81
      49 1719.22    68.6  1716.2   79.311713.136    98.1 1706.46   117.7  1700.6
   127.5 1697.47   156.9 1686.75   166.7 1681.75   176.5 1675.09   186.4  1669.7
   196.2 1667.23     206 1666.76   235.4 1666.25   284.4 1665.76   294.2    1666
     304 1668.26   313.8 1672.93   323.6 1676.18   333.5 1677.86   343.3 1678.98
   362.9 1680.59   372.7 1681.73   382.5 1683.24   402.1 1686.72   441.4 1694.27
#Mann= 5 ,-1 , 0
       0     .12       0    16.8    .016       0   79.31     .12       0
   196.2    .045       0   294.2     .12       0
Bank Sta=196.2,294.2
XS Rating Curve= 0 ,0
Exp/Cntr=0.3,0.1

Type RM Length L Ch R = 1 ,14215.1 ,283.1,290.9,298.1
XS GIS Cut Line= 2
     1807905.505       197950.87     1807832.994      197436.988
#Sta/Elev= 30
       0 1735.97     9.8 1733.09    19.6 1731.04    29.4 1728.66    39.2 1725.67
    58.8 1719.05    68.5 1716.26    97.9 1709.89   107.7 1707.15   117.5 1703.92
   127.3 1700.24   137.1  1696.2   146.9  1691.8     186 1673.48   195.8 1669.59
   205.6 1666.96   215.4 1665.77   264.4 1664.17   332.9  1663.1   342.7 1663.36
   352.5 1664.74   362.3 1667.32   381.9 1673.85   391.7 1676.76     421 1684.12
   430.8 1686.15   450.4 1689.64     470 1692.74   479.8  1693.8     519 1696.79
#Mann= 3 ,-1 , 0
       0     .12       0   215.4    .045       0   352.5     .12       0
Bank Sta=215.4,352.5
XS Rating Curve= 0 ,0
Exp/Cntr=0.3,0.1

Type RM Length L Ch R = 1 ,13924.2 ,265,268.9,272.6
XS GIS Cut Line= 2
     1808138.144      197985.592     1808165.922      197381.425
#Sta/Elev= 30
       0 1762.28     9.8 1757.84    19.5 1754.24      39 1749.03    48.8 1746.05
   107.3 1727.47   126.8  1720.5   136.6  1716.4   146.3 1711.18   156.1 1704.61
   175.6  1689.5   195.1 1673.95   204.8 1667.69   214.6 1664.65   224.4 1663.86
   341.4 1661.47   351.2 1662.42   380.4 1668.38   390.2 1669.86   419.5 1673.14
     439 1676.56   458.5 1680.62     478  1685.7   497.5 1691.74   507.3  1695.2
     517 1699.04     556 1716.56   565.8 1720.52   575.5 1723.99   604.8 1733.17
#Mann= 3 ,-1 , 0
       0     .12       0   224.4    .045       0   351.2     .12       0
Bank Sta=224.4,351.2
XS Rating Curve= 0 ,0
Exp/Cntr=0.3,0.1

Type RM Length L Ch R = 1 ,13655.2 ,252.9,281.1,309.1
XS GIS Cut Line= 3
     1808169.394      198002.953     1808384.672      197822.398
     1808447.172       197419.62
#Sta/Elev= 30
       0 1764.07    19.4 1754.26    48.4 1741.15    58.1 1737.02    96.9  1722.2
   106.6 1718.04   116.3 1712.96     126 1706.54   145.3 1692.08     155 1686.14
  163.441683.173   174.4 1681.41  192.631679.523   242.2 1675.33   329.5 1670.72
   339.2 1669.35   348.9  1667.4     378 1660.94   387.7 1659.23   397.4 1658.34
   416.8 1658.06   504.2 1658.36   513.9 1658.94   523.6 1660.76   533.3 1663.72
   562.4 1674.39   572.1 1677.62   601.2 1685.33   610.9 1689.63   688.6 1733.17
#Mann= 5 ,-1 , 0
       0     .12       0  163.44     .08       0  192.63     .12       0
   397.4    .045       0   513.9     .12       0
Bank Sta=397.4,513.9
XS Rating Curve= 0 ,0
Exp/Cntr=0.3,0.1

Type RM Length L Ch R = 1 ,13374.2 ,338.8,367.7,396.5
XS GIS Cut Line= 3
     1808200.644      198002.953     1808513.144       197888.37
     1808839.533      197627.953
#Sta/Elev= 30
       0 1752.54    29.4  1736.2    39.2 1731.67    58.7 1724.81    68.5 1720.83
    78.3 1715.62    88.1 1708.83   107.7 1692.96   117.5 1686.82   127.3 1683.49
  133.331682.601  180.481678.239   244.7 1674.39   381.4  1668.9   391.1 1668.09
   400.8 1666.43   420.2 1661.22     430 1659.56   507.6 1657.43   517.3 1658.69
     527 1662.69   556.2 1681.55   614.4 1720.83   624.2 1728.01   633.9 1735.91
   643.6 1742.46   653.3 1746.84     663 1749.66   721.3 1760.72   750.4  1766.8
#Mann= 5 ,-1 , 0
       0     .12       0  133.33     .08       0  180.48     .12       0
     430    .045       0   517.3     .12       0
Bank Sta=430,517.3
XS Rating Curve= 0 ,0
Exp/Cntr=0.3,0.1

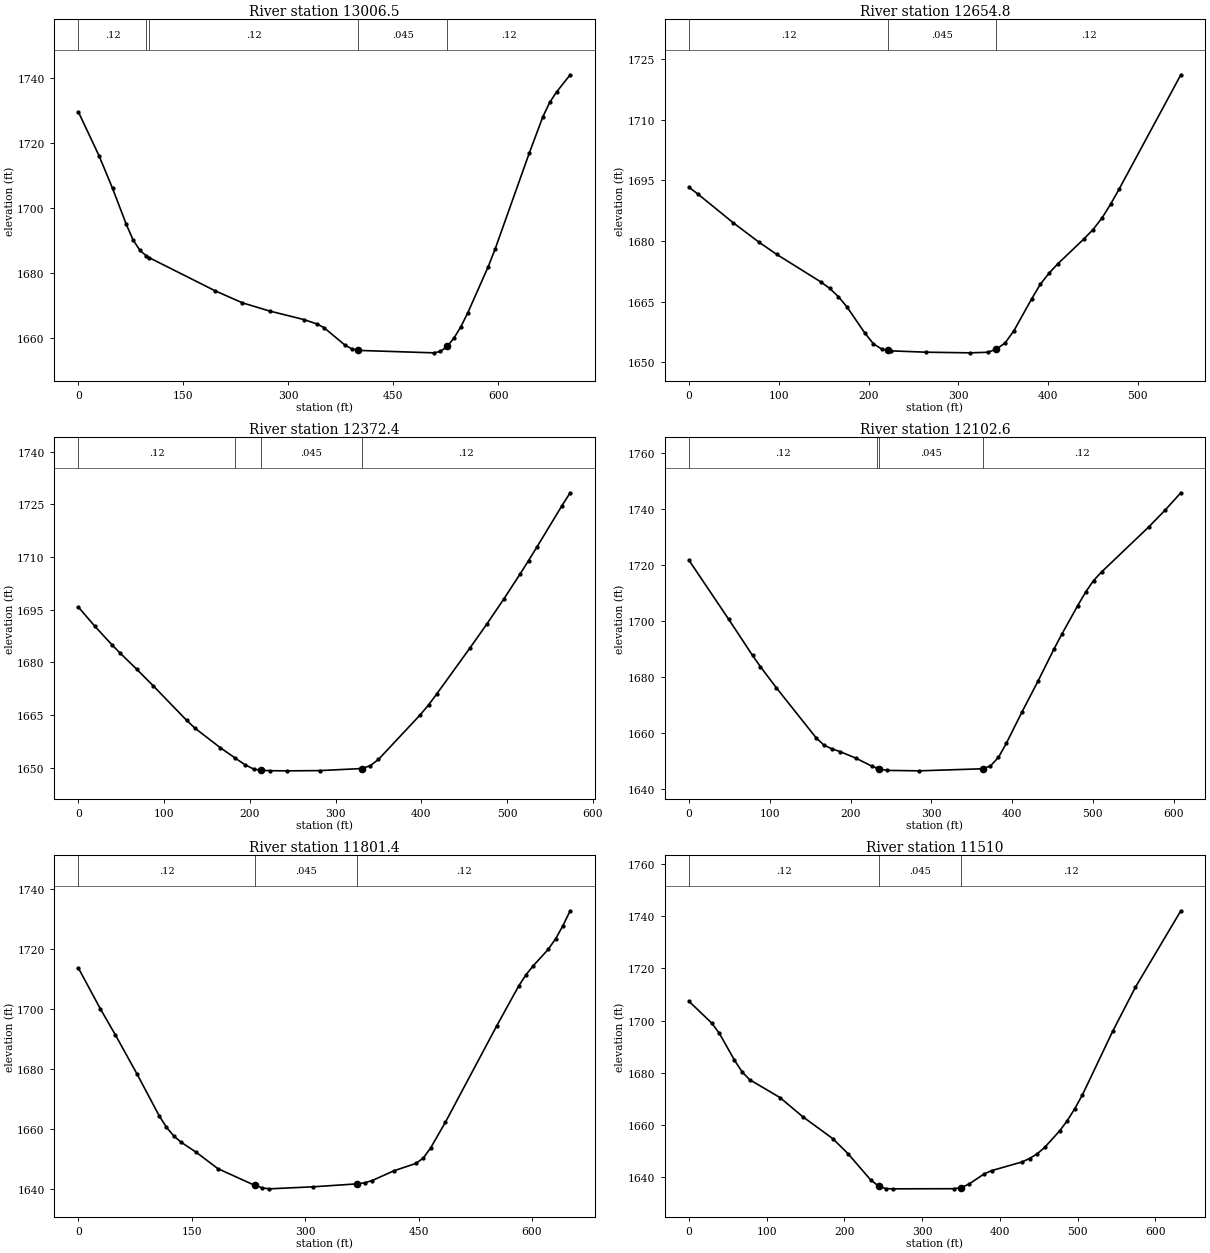
Type RM Length L Ch R = 1 ,13006.5 ,326.9,351.7,376.3
XS GIS Cut Line= 2
     1808249.255      198079.342     1808948.784      198147.923
#Sta/Elev= 30
       0 1729.47    29.3 1716.09    48.8 1705.96    68.3 1694.95    78.1  1690.1
    87.9 1686.89   97.211685.153  101.241684.627   195.2 1674.46   234.3 1670.74
   273.3 1668.21   322.2 1665.59   341.7 1664.18   351.4 1663.02   380.7 1657.77
   390.5 1656.59   400.2 1656.09   507.6 1655.34   517.4 1655.76   527.2 1657.32
   536.9 1659.95   546.7  1663.4   556.4 1667.61   585.7 1681.85   595.5 1687.23
   644.3 1716.77   663.8    1728   673.6 1732.42   683.4 1735.65   702.9 1740.95
#Mann= 5 ,-1 , 0
       0     .12       0   97.21     .06       0  101.24     .12       0
   400.2    .045       0   527.2     .12       0
Bank Sta=400.2,527.2
XS Rating Curve= 0 ,0
Exp/Cntr=0.3,0.1

Type RM Length L Ch R = 1 ,12654.8 ,286.7,282.5,278.3
XS GIS Cut Line= 2
     1808290.922      198193.925       1808693.7      198565.453
#Sta/Elev= 30
       0 1693.29     9.8 1691.65    48.9 1684.58    78.3 1679.65    97.8 1676.68
   146.8 1669.88   156.6 1668.29   166.4 1666.24   176.1 1663.65   195.7 1657.27
   205.5 1654.53   215.3 1653.18   221.91652.931   225.1 1652.81   264.2 1652.48
   313.1 1652.32   332.7 1652.46   342.5 1653.22   352.3 1654.81     362 1657.79
   381.6 1665.62   391.4  1669.3   401.2 1672.05     411 1674.38   440.3 1680.59
   450.1 1682.83   459.9 1685.63   469.7  1689.1   479.5 1692.98     548 1721.17
#Mann= 3 ,-1 , 0
       0     .12       0   221.9    .045       0   342.5     .12       0
Bank Sta=221.9,342.5
XS Rating Curve= 0 ,0
Exp/Cntr=0.3,0.1

Type RM Length L Ch R = 1 ,12372.4 ,271.5,269.7,267.8
XS GIS Cut Line= 2
     1808075.951      198419.194      1808537.45      198759.898
#Sta/Elev= 30
       0 1695.71    19.4 1690.21    38.9 1685.04    48.6 1682.63    68.1    1678
    87.5 1673.24   126.4 1663.43   136.1  1661.2   165.3 1655.72   183.11652.677
   194.4 1650.81   204.2 1649.63  212.551649.243   223.6 1649.13   243.1 1649.09
     282 1649.16   330.6 1649.75   340.3 1650.54     350 1652.35   398.6 1665.02
   408.4 1667.85   418.1 1671.04     457 1684.19   476.4 1690.91   495.9 1697.93
   515.3  1705.2     525 1708.97   534.8 1712.84   563.9 1724.58   573.6 1728.29
#Mann= 4 ,-1 , 0
       0     .12       0   183.1     .08       0  212.55    .045       0
   330.6     .12       0
Bank Sta=212.55,330.6
XS Rating Curve= 0 ,0
Exp/Cntr=0.3,0.1

Type RM Length L Ch R = 1 ,12102.6 ,313.4,301.2,288.3
XS GIS Cut Line= 2
     1807909.313      198637.436     1808415.922      198975.175
#Sta/Elev= 30
       0 1721.71    49.1 1700.61    78.6 1687.68    88.4 1683.64     108 1676.13
   157.1 1658.27     167 1655.59   176.8 1654.26   186.6  1653.3   206.2 1650.96
   225.9 1648.12  232.671647.346   235.7    1647   245.5 1646.54   284.8 1646.38
   363.4 1647.12   373.2 1648.14     383 1651.18   392.8 1656.22   412.5 1667.62
   432.1 1678.53   451.7 1689.91   461.6 1695.32   481.2 1705.52     491 1710.35
   500.8 1714.49   510.7 1717.55   569.6 1733.81   589.2 1739.64   608.9 1745.92
#Mann= 4 ,-1 , 0
       0     .12       0  232.67     .08       0   235.7    .045       0
   363.4     .12       0
Bank Sta=235.7,363.4
XS Rating Curve= 0 ,0
Exp/Cntr=0.3,0.1

Type RM Length L Ch R = 1 ,11801.4 ,299.5,291.4,283.5
XS GIS Cut Line= 2
      1807697.92      198957.054     1808325.644      199127.953
#Sta/Elev= 30
       0 1713.68    29.1 1700.08    48.6 1691.58    77.7 1678.34   106.8 1664.54
   116.5 1660.69   126.2 1657.79   135.9 1655.71   155.4 1652.46   184.5 1646.92
     233 1641.39   242.8 1640.54   252.5  1640.2   310.7 1640.88     369 1641.86
   378.7 1642.22   388.4 1642.94   417.5 1646.22   446.7 1648.68   456.4  1650.5
   466.1 1653.87   485.5 1662.38   553.5  1694.5   582.6  1707.8   592.3 1711.53
     602 1714.54   621.4  1719.9   631.2  1723.4   640.9 1727.76   650.6 1732.78
#Mann= 3 ,-1 , 0
       0     .12       0     233    .045       0     369     .12       0
Bank Sta=233,369
XS Rating Curve= 0 ,0
Exp/Cntr=0.3,0.1

Type RM Length L Ch R = 1 ,11510   ,283.3,280,276.6
XS GIS Cut Line= 2
     1807652.192       199300.98     1808284.497      199330.118
#Sta/Elev= 30
       0 1707.38    29.2 1699.07      39 1695.11    58.4 1684.87    68.2 1680.37
    77.9 1677.38   116.9 1670.54   146.1 1663.23     185 1654.76   204.5 1649.03
   233.7 1638.96   244.31636.491   253.2 1635.61   262.9 1635.52   340.8 1635.57
   350.6 1635.98   360.3 1637.35   379.8 1641.24   389.5 1642.51   428.5 1645.82
   438.2 1647.14     448 1648.94   457.7 1651.38   477.2 1657.82   486.9  1661.7
   496.6 1666.32   506.4  1671.6   545.3 1695.94   574.6 1712.85     633 1742.13
#Mann= 3 ,-1 , 0
       0     .12       0   244.3    .045       0   350.6     .12       0
Bank Sta=244.3,350.6
XS Rating Curve= 0 ,0
Exp/Cntr=0.3,0.1