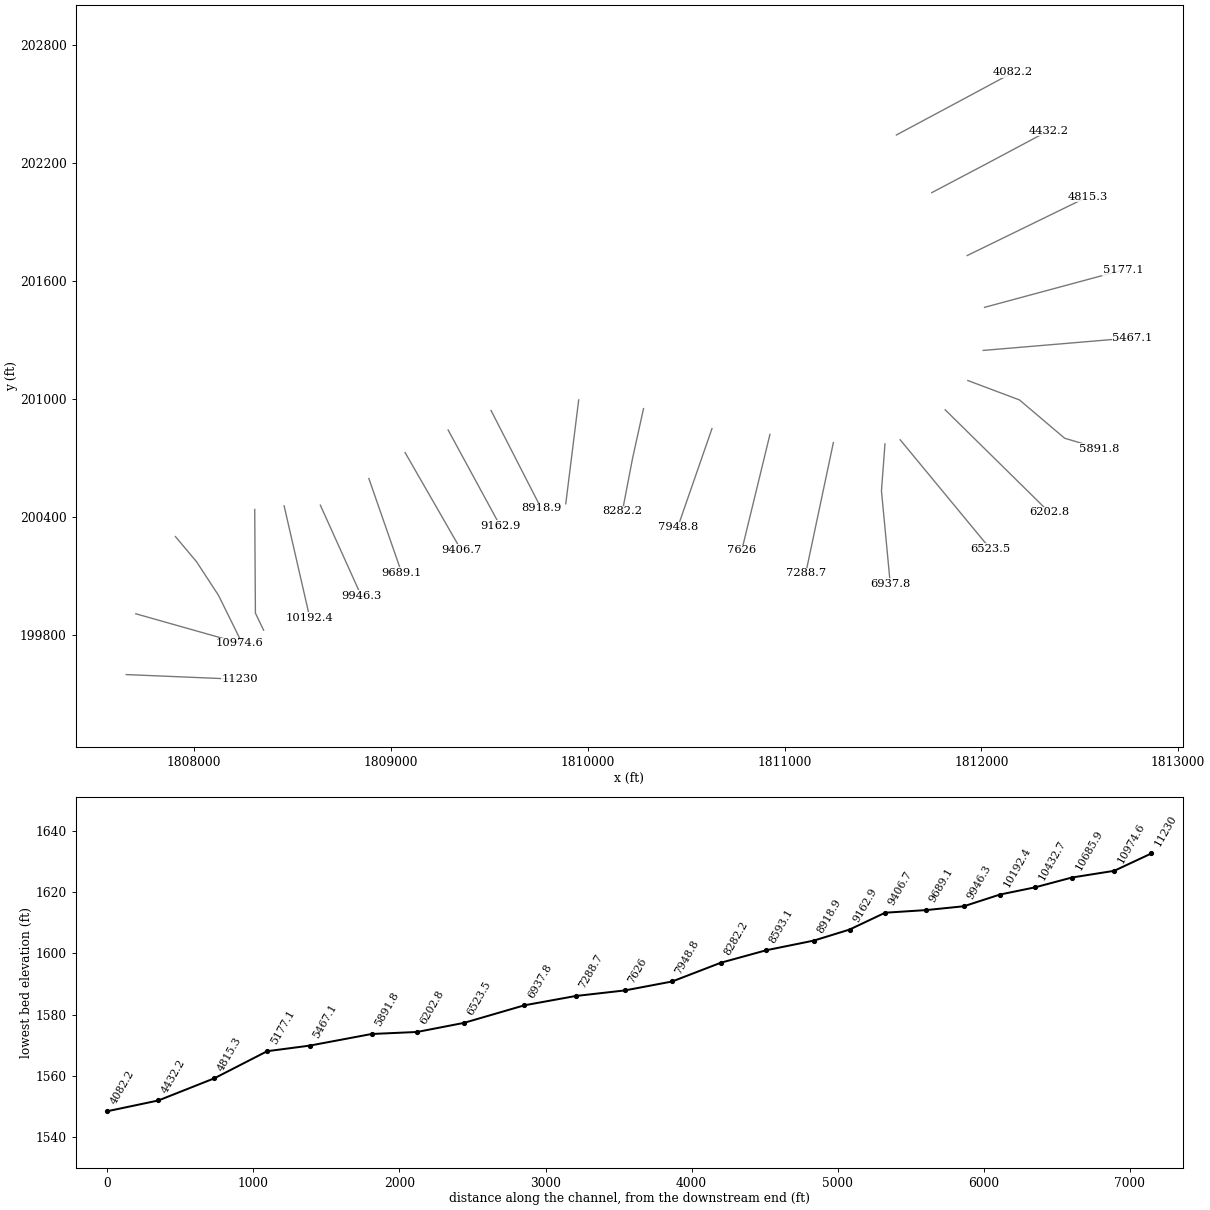
HEC-RAS study MIDFKRV2.prj: MIDFKRV2

--- MIDFKRV2.g01 (geometry) --- (continued)

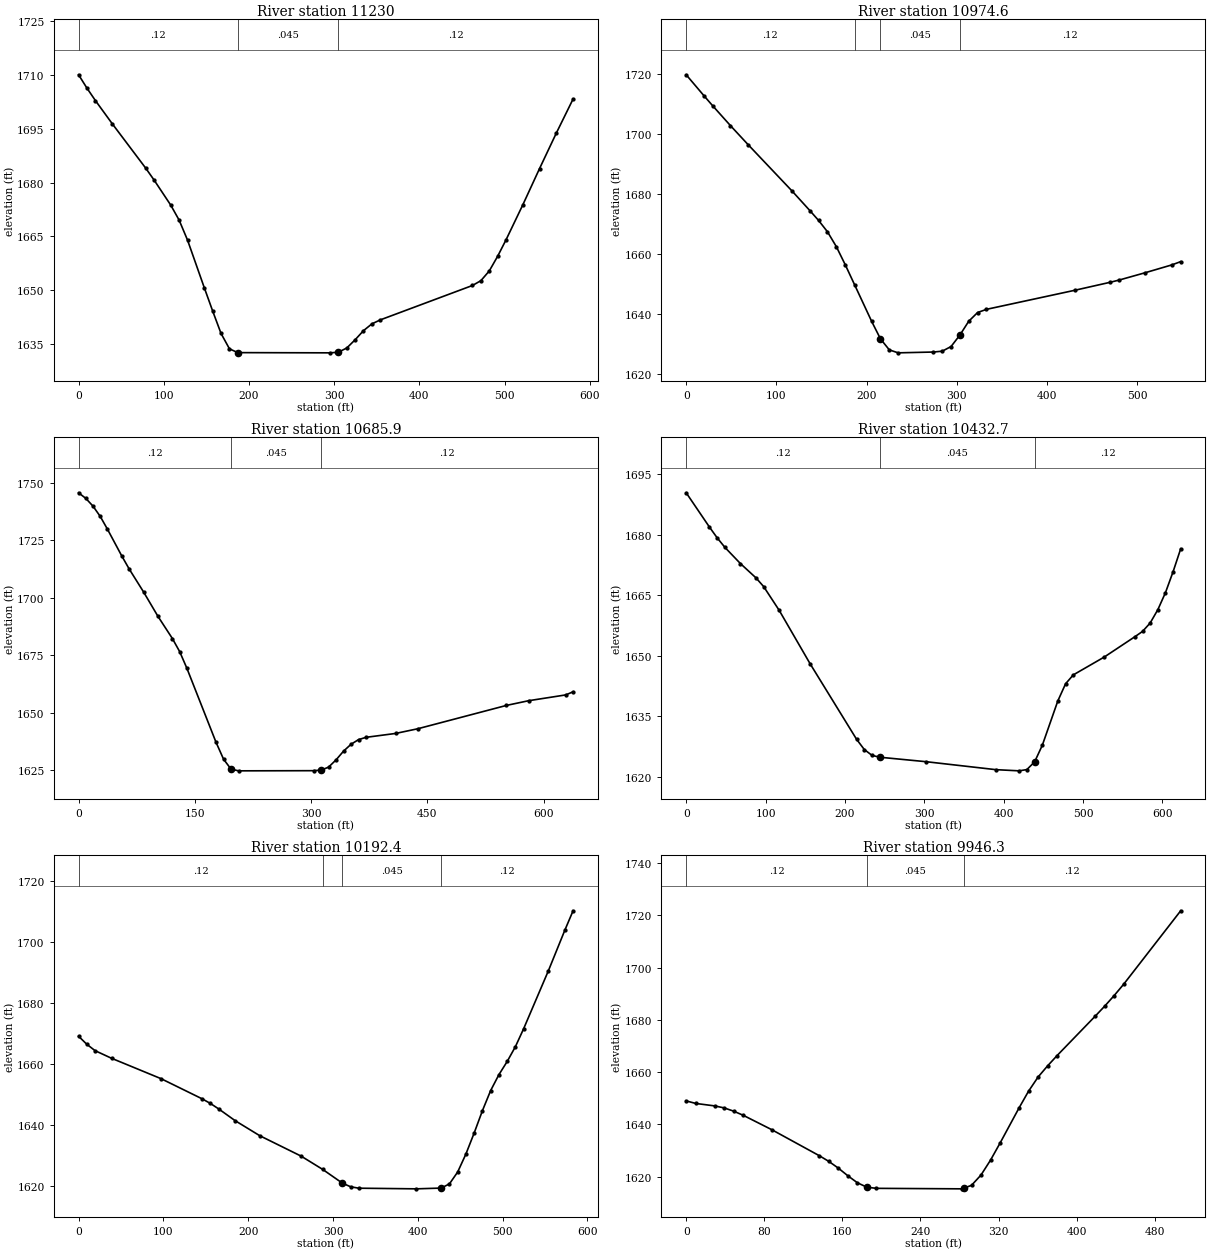
Type RM Length L Ch R = 1 ,11230   ,264.3,255.5,246.6
XS GIS Cut Line= 2
     1807655.505      199600.175     1808235.366       199575.87
#Sta/Elev= 30
       0 1710.01     9.8  1706.3    19.7 1702.85    39.4 1696.42    78.7 1684.05
    88.5 1680.75   108.2 1673.72     118 1669.56   127.9 1663.98   147.6  1650.7
   157.4 1644.24   167.2 1638.01   177.1 1633.72   186.9 1632.67   295.1 1632.61
   304.9 1632.78   314.8 1633.96   324.6 1636.25   334.4 1638.78   344.3 1640.68
   354.1 1641.78   462.3 1651.36   472.2  1652.7     482 1655.39   491.8 1659.46
   501.7 1664.06   521.4  1673.8     541 1683.88   560.7 1693.76   580.4 1703.26
#Mann= 3 ,-1 , 0
       0     .12       0   186.9    .045       0   304.9     .12       0
Bank Sta=186.9,304.9
XS Rating Curve= 0 ,0
Exp/Cntr=0.3,0.1

Type RM Length L Ch R = 1 ,10974.6 ,315.7,288.7,261.5
XS GIS Cut Line= 2
     1807704.116      199909.203     1808231.894      199759.898
#Sta/Elev= 29
       0 1719.79    19.6 1712.83    29.4 1709.43      49 1702.84    68.6 1696.48
   117.5 1680.95   137.1 1674.46   146.9 1671.13   156.7 1667.36   166.5 1662.42
   176.3 1656.43   186.71649.724   205.7 1637.45   215.5 1631.59   225.3 1627.92
   235.1 1626.93   274.2  1627.2     284 1627.48   293.8 1629.04   303.6 1632.87
   313.4 1637.48   323.2 1640.39     333 1641.45     431 1647.82   470.1 1650.48
   479.9 1651.21   509.3  1653.7   538.7  1656.3   548.5 1657.39
#Mann= 4 ,-1 , 0
       0     .12       0   186.7     .08       0   215.5    .045       0
   303.6     .12       0
Bank Sta=215.5,303.6
XS Rating Curve= 0 ,0
Exp/Cntr=0.3,0.1

Type RM Length L Ch R = 1 ,10685.9 ,274.9,253.2,231.5
XS GIS Cut Line= 4
     1807905.505      200301.564     1808013.144      200173.092
     1808124.255      200002.953     1808242.311       199763.37
#Sta/Elev= 30
       0 1745.65     9.3 1743.22    18.6 1739.84    27.9 1735.39    37.2 1729.84
    55.9 1718.07    65.2 1712.56    83.8 1702.54   102.4 1691.92     121 1682.28
   130.4 1676.59   139.7 1669.36   177.3 1637.17     187 1629.83   196.6 1625.52
   206.3 1624.75   303.1 1624.82   312.8 1625.07   322.4 1626.34   332.1  1629.5
   341.8 1633.31   351.5 1636.31   361.1 1638.32   370.8 1639.32     409 1641.01
   437.6 1643.05     552  1653.2   580.7 1655.25   628.4 1657.76   637.9 1659.12
#Mann= 3 ,-1 , 0
       0     .12       0   196.6    .045       0   312.8     .12       0
Bank Sta=196.6,312.8
XS Rating Curve= 0 ,0
Exp/Cntr=0.3,0.1

Type RM Length L Ch R = 1 ,10432.7 ,233.3,240.3,248.6
XS GIS Cut Line= 3
     1808308.335      200439.418     1808311.755      199912.675
     1808353.422       199825.87
#Sta/Elev= 30
       0 1690.37    29.3 1681.88      39 1679.22    48.8 1676.85    68.3 1672.85
    87.8 1669.33    97.6 1667.15   117.1 1661.29   156.1 1648.05   214.6 1629.37
   224.4 1626.81   234.1 1625.37   243.9 1624.91   302.4  1623.8   390.2 1621.83
   419.4 1621.54   429.2 1621.85     439 1623.77   448.7 1627.89   468.2 1638.84
     478  1643.1   487.7 1645.29   526.8 1649.72   565.3 1654.74   574.9 1656.05
   584.5 1658.12   594.2 1661.43   603.8 1665.64   613.4 1670.82     623  1676.5
#Mann= 3 ,-1 , 0
       0     .12       0   243.9    .045       0     439     .12       0
Bank Sta=243.9,439
XS Rating Curve= 0 ,0
Exp/Cntr=0.3,0.1

Type RM Length L Ch R = 1 ,10192.4 ,237.1,246.1,253.9
XS GIS Cut Line= 2
     1808457.589      200457.814     1808587.998      199889.363
#Sta/Elev= 30
       0 1669.24     9.7 1666.61    19.4 1664.52    38.9 1662.01    97.2 1655.33
   145.8  1648.7   155.5 1647.19   165.2 1645.41   184.7 1641.54   213.8  1636.6
   262.4 1629.93  287.831625.576     311 1621.08   320.8 1619.87   330.5  1619.4
   398.5 1619.19   427.7 1619.44   437.4 1620.82   447.1 1624.71   456.8  1630.6
   466.6 1637.54   476.3 1644.84     486 1651.43   495.7 1656.62   505.5 1660.97
   515.2 1665.83   524.9 1671.71   554.1 1690.73   573.5 1704.03   583.2 1710.39
#Mann= 4 ,-1 , 0
       0     .12       0  287.83     .06       0     311    .045       0
   427.7     .12       0
Bank Sta=311,427.7
XS Rating Curve= 0 ,0
Exp/Cntr=0.3,0.1

Type RM Length L Ch R = 1 ,9946.3  ,260.6,257.2,253.8
XS GIS Cut Line= 2
     1808641.616      200461.286      1808849.95      199999.481
#Sta/Elev= 30
       0 1649.02     9.7 1648.05    29.2  1647.1      39 1646.33    48.7 1645.08
    58.5  1643.5    87.7    1638   136.4 1628.05   146.1 1625.88   155.9 1623.29
   165.6 1620.38   175.4  1617.7   185.1 1616.01   194.9 1615.57   282.5 1615.38
  284.351615.633   292.3 1616.72     302 1620.65   311.8 1626.37   321.5 1632.85
     341 1646.33   350.7 1652.71   360.5 1658.15   370.2  1662.4     380 1666.37
   418.9 1681.38   428.7 1685.24   438.4 1689.29   448.2 1693.65   506.6 1721.74
#Mann= 3 ,-1 , 0
       0     .12       0   185.1    .045       0  284.35     .12       0
Bank Sta=185.1,284.35
XS Rating Curve= 0 ,0
Exp/Cntr=0.3,0.1

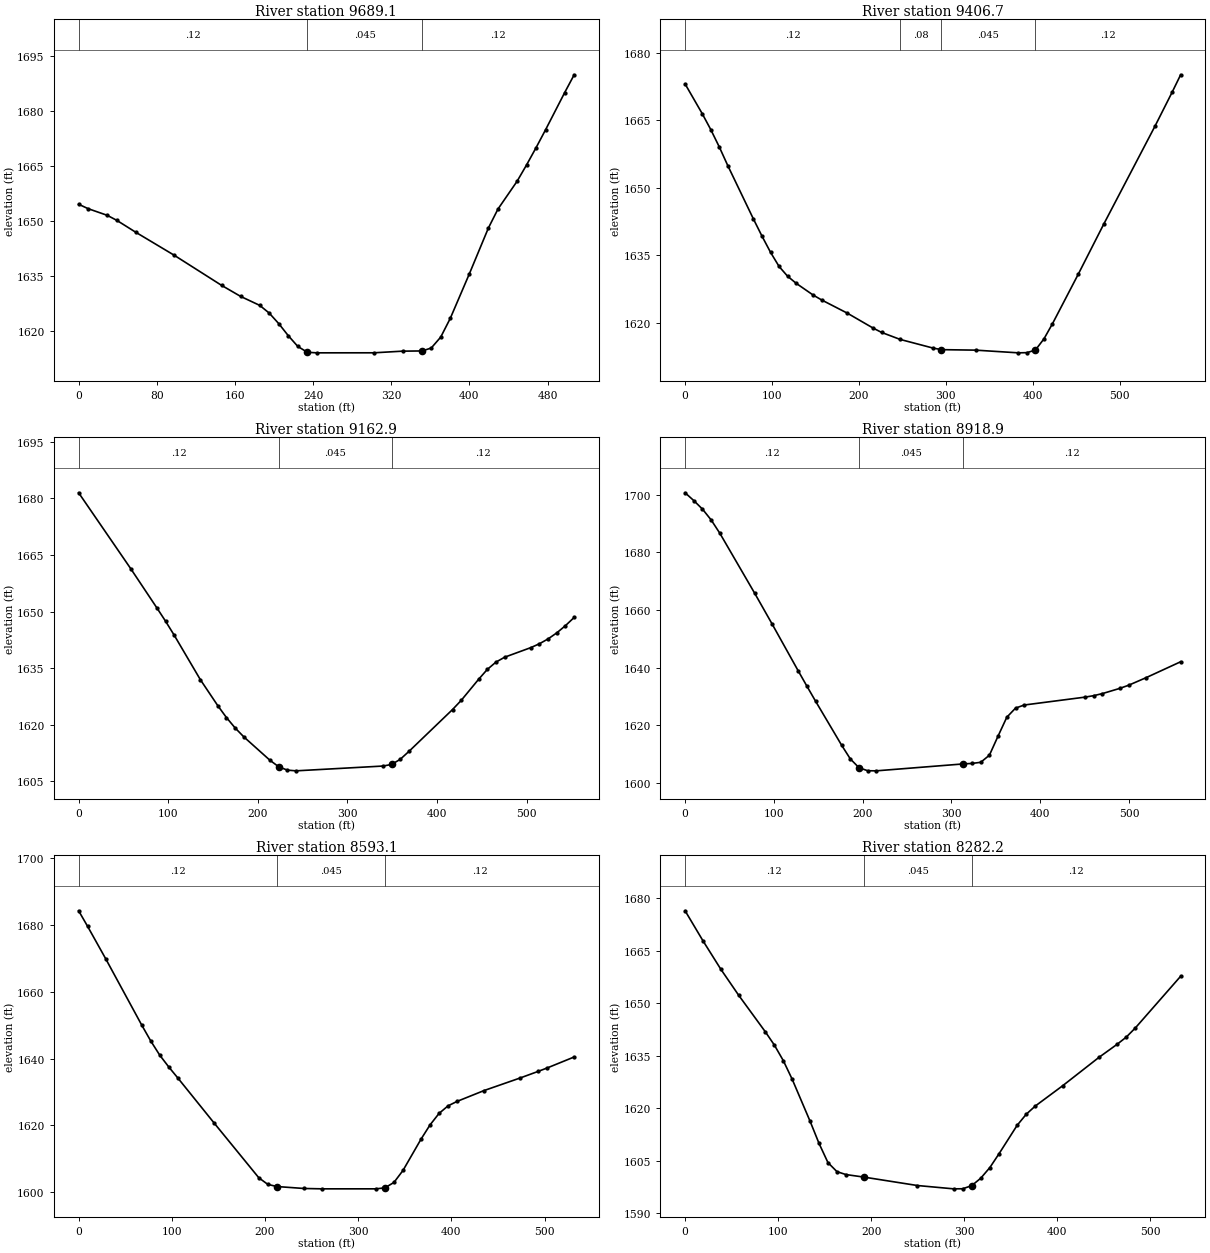
Type RM Length L Ch R = 1 ,9689.1  ,275.3,282.3,289.4
XS GIS Cut Line= 2
     1808888.144      200596.703     1809054.811      200117.536
#Sta/Elev= 30
       0 1654.67     9.8 1653.46    29.3 1651.65      39 1650.29    58.5 1647.03
    97.6  1640.8   146.3 1632.55   165.9 1629.52   185.4 1627.08   195.1 1624.98
   204.9 1622.09   214.6 1618.82   224.4 1615.87   234.2 1614.28   243.9 1614.13
   302.4 1614.14   331.7 1614.59  351.751614.648     361 1615.45   370.7 1618.43
   380.5 1623.56     400 1635.69   419.5  1648.2   429.3 1653.37   448.8 1660.92
   458.5 1665.37   468.3 1670.11   478.1 1675.04   497.6 1685.15   507.3    1690
#Mann= 3 ,-1 , 0
       0     .12       0   234.2    .045       0  351.75     .12       0
Bank Sta=234.2,351.75
XS Rating Curve= 0 ,0
Exp/Cntr=0.3,0.1

Type RM Length L Ch R = 1 ,9406.7  ,244.8,243.8,242.9
XS GIS Cut Line= 2
     1809072.172      200728.648     1809356.043      200234.377
#Sta/Elev= 30
       0 1673.04    19.6 1666.47    29.5 1662.91    39.3 1659.05    49.1 1654.89
    78.6 1643.02    88.4 1639.23    98.3 1635.61   108.1 1632.47   117.9  1630.3
   127.8 1628.72   147.4  1626.1   157.2 1625.01   186.7 1622.08   216.2 1618.78
     226 1617.81  247.311616.256     285 1614.34   294.8 1613.98   334.1 1613.87
   383.3 1613.27   393.1 1613.31   402.9 1613.88   412.8 1616.38   422.6 1619.75
   452.1  1630.7   481.5 1641.86   540.5 1663.66   560.2  1671.2     570 1675.08
#Mann= 4 ,-1 , 0
       0     .12       0  247.31     .08       0   294.8    .045       0
   402.9     .12       0
Bank Sta=294.8,402.9
XS Rating Curve= 0 ,0
Exp/Cntr=0.3,0.1

Type RM Length L Ch R = 1 ,9162.9  ,245.1,244,242.4
XS GIS Cut Line= 2
     1809290.922      200843.231     1809554.811       200357.12
#Sta/Elev= 30
       0 1681.47    58.2 1661.34    87.3 1650.97      97 1647.44   106.7 1643.71
   135.8 1631.96   155.3 1625.05     165 1621.89   174.7 1619.13   184.4 1616.77
   213.5 1610.58   223.2 1608.87   232.9 1607.96   242.6 1607.77   339.6 1609.04
   349.3 1609.46     359 1610.83   368.8 1612.95   417.3 1624.01     427 1626.44
   446.4 1632.02   456.1 1634.64   465.8 1636.59   475.5 1637.89   504.6 1640.42
   514.3 1641.45     524 1642.74   533.7 1644.34   543.4 1646.26   553.1 1648.43
#Mann= 3 ,-1 , 0
       0     .12       0   223.2    .045       0   349.3     .12       0
Bank Sta=223.2,349.3
XS Rating Curve= 0 ,0
Exp/Cntr=0.3,0.1

Type RM Length L Ch R = 1 ,8918.9  ,348.1,325.9,303.6
XS GIS Cut Line= 2
      1809508.93      200942.563     1809763.408      200445.725
#Sta/Elev= 30
       0 1700.64     9.8 1697.93    19.6 1694.96    29.4  1691.2    39.2 1686.56
    78.4 1665.78    97.9 1655.18   127.3 1638.93   137.1 1633.61   146.9 1628.38
   176.3 1613.08   186.1 1608.32   195.9 1605.27   205.7 1604.21   215.4 1604.18
   313.4 1606.58   323.2 1606.75     333 1607.14   342.8 1609.61   352.6 1616.28
   362.4 1622.78   372.2 1625.93   381.9 1627.01   450.5 1629.75   460.3 1630.26
   470.1 1630.98   489.7 1632.79   499.5 1633.86     519 1636.46   558.2 1642.02
#Mann= 3 ,-1 , 0
       0     .12       0   195.9    .045       0   313.4     .12       0
Bank Sta=195.9,313.4
XS Rating Curve= 0 ,0
Exp/Cntr=0.3,0.1

Type RM Length L Ch R = 1 ,8593.1  ,314.3,310.9,308.3
XS GIS Cut Line= 2
     1809954.116      200996.009     1809888.524      200468.289
#Sta/Elev= 28
       0 1684.26     9.7 1679.56      29 1669.92    67.7 1650.05    77.4 1645.29
      87 1641.06    96.7 1637.52   106.4 1634.23     145 1620.87   193.4 1604.33
     203 1602.37   212.7 1601.72   241.7 1601.14   261.1 1601.03   319.1 1601.03
   328.7 1601.33   338.4 1602.95   348.1 1606.54   367.4 1615.88   377.1 1620.16
   386.8 1623.61   396.4 1625.86   406.1  1627.2   435.1 1630.45   473.8 1634.21
   493.1 1636.18   502.8 1637.21   531.8  1640.5
#Mann= 3 ,-1 , 0
       0     .12       0   212.7    .045       0   328.7     .12       0
Bank Sta=212.7,328.7
XS Rating Curve= 0 ,0
Exp/Cntr=0.3,0.1

Type RM Length L Ch R = 1 ,8282.2  ,337.8,333.4,327.9
XS GIS Cut Line= 3
     1810283.507      200952.097     1810227.714       200698.88
     1810176.157      200430.254
#Sta/Elev= 30
       0 1676.39    19.2 1667.82    38.4  1659.7    57.6 1652.26    86.4 1641.77
      96 1638.02   105.6 1633.58   115.2 1628.23   134.4 1616.26     144 1609.94
   153.6 1604.45   163.3 1601.87   172.9 1601.04   192.1 1600.32   249.7 1597.91
   288.6 1596.96   298.4 1596.98   308.1 1597.86   317.9    1600   327.7 1603.05
   337.4 1606.93     357  1615.1   366.8 1618.27   376.5 1620.61   405.8 1626.38
   444.9  1634.5   464.4 1638.23   474.2 1640.27     484 1642.89   532.8 1657.68
#Mann= 3 ,-1 , 0
       0     .12       0   192.1    .045       0   308.1     .12       0
Bank Sta=192.1,308.1
XS Rating Curve= 0 ,0
Exp/Cntr=0.3,0.1

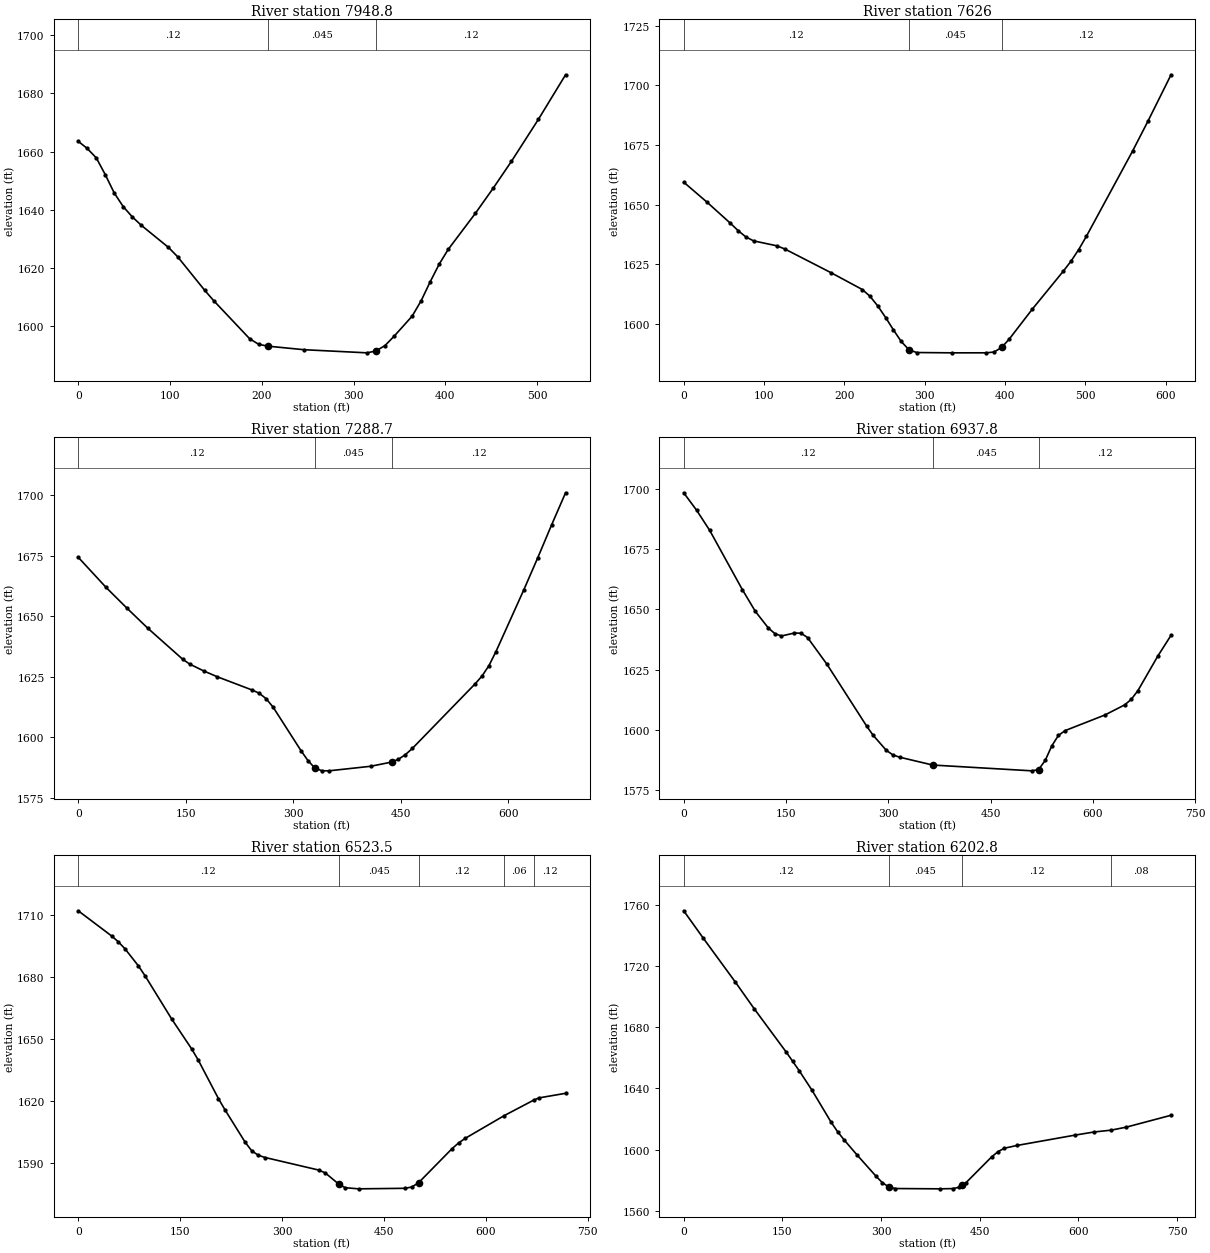
Type RM Length L Ch R = 1 ,7948.8  ,319.2,322.8,326.4
XS GIS Cut Line= 2
       1810631.2      200850.175     1810457.123        200348.6
#Sta/Elev= 30
       0 1663.54     9.8 1661.08    19.7 1657.83    29.5 1652.06    39.3 1645.74
    49.2 1641.01      59 1637.54    68.8 1634.65    98.3 1627.08   108.2  1623.9
   137.6  1612.4   147.5  1608.8   186.8 1595.67   196.6 1593.77   206.5 1593.14
   245.8 1591.92   314.6 1590.84   324.4 1591.49   334.3 1593.36   344.1 1596.54
   363.8 1603.46   373.6 1608.76   383.4 1615.24   393.3 1621.36   403.1 1626.41
   432.6 1638.76   452.3 1647.53   471.9 1656.63   501.4 1671.13   530.9  1686.4
#Mann= 3 ,-1 , 0
       0     .12       0   206.5    .045       0   324.4     .12       0
Bank Sta=206.5,324.4
XS Rating Curve= 0 ,0
Exp/Cntr=0.3,0.1

Type RM Length L Ch R = 1 ,7626    ,336.1,337.3,338.5
XS GIS Cut Line= 3
     1810925.846      200821.018     1810845.985       200492.18
     1810782.483      200231.543
#Sta/Elev= 30
       0 1659.44      29 1651.07      58 1642.27    67.7 1639.15    77.4  1636.5
      87 1634.84     116 1632.77   125.7 1631.47   183.7 1621.46   222.4 1614.45
     232  1611.6   241.7 1607.54   251.4 1602.73     261  1597.6   270.7 1592.74
   280.4 1589.23     290 1588.06   334.6 1587.93   376.7 1587.94   386.3 1588.27
   395.9  1590.2   405.5 1593.79   434.2 1606.32   472.5  1622.1   482.1 1626.28
   491.7 1631.17   501.3 1636.74   558.8 1672.44   577.9 1684.95   606.7 1704.43
#Mann= 3 ,-1 , 0
       0     .12       0   280.4    .045       0   395.9     .12       0
Bank Sta=280.4,395.9
XS Rating Curve= 0 ,0
Exp/Cntr=0.3,0.1

Type RM Length L Ch R = 1 ,7288.7  ,339,350.9,363.5
XS GIS Cut Line= 2
     1811248.066       200779.52     1811107.414      200114.355
#Sta/Elev= 30
       0 1674.31    38.8 1661.88      68 1653.29    97.1    1645   145.7 1632.21
   155.4 1630.22   174.8 1627.41   194.2 1624.94   242.8 1619.47   252.5 1618.15
   262.2  1615.9     272 1612.37   310.8 1594.44   320.5 1590.34   330.2 1587.24
   339.9 1586.15   349.6 1586.11   407.9 1587.99   437.1 1589.72   446.8  1590.9
   456.5 1592.81   466.2 1595.38   553.6    1622   563.3 1625.25     573 1629.56
   582.8 1635.36   621.6 1660.83     641 1674.04   660.4 1687.66   679.9 1700.95
#Mann= 3 ,-1 , 0
       0     .12       0   330.2    .045       0   437.1     .12       0
Bank Sta=330.2,437.1
XS Rating Curve= 0 ,0
Exp/Cntr=0.3,0.1

Type RM Length L Ch R = 1 ,6937.8  ,392.3,414.3,435.5
XS GIS Cut Line= 3
     1811510.181      200772.466     1811492.311      200534.203
     1811537.151      200060.583
#Sta/Elev= 30
       0 1698.28    19.1 1690.99    38.2 1682.67      86 1658.16   105.1 1649.14
   124.2 1642.24   133.8 1639.92   143.4 1638.95   162.5 1640.19     172 1640.09
   181.6 1638.32   210.3 1627.15   268.1 1601.71   277.8 1597.82   297.2 1591.56
   306.9 1589.66   316.6 1588.74   365.2 1585.48   510.8 1583.08   520.5 1583.62
   530.2  1587.4   539.9 1593.47   549.6 1597.75   559.3 1599.74   617.6  1606.2
   646.7  1610.4   656.4  1612.7   666.1  1616.3   695.2 1630.57   714.7 1639.23
#Mann= 3 ,-1 , 0
       0     .12       0   365.2    .045       0   520.5     .12       0
Bank Sta=365.2,520.5
XS Rating Curve= 0 ,0
Exp/Cntr=0.3,0.1

Type RM Length L Ch R = 1 ,6523.5  ,316.9,320.7,324.2
XS GIS Cut Line= 2
      1811587.41      200793.529     1812044.282       200240.31
#Sta/Elev= 30
       0 1712.05    49.1 1699.87      59 1697.03    68.8 1693.65    88.5 1685.42
    98.3 1680.61   137.6 1659.62   167.1 1645.09   176.9 1639.61   206.4 1621.08
   216.2 1615.55   245.7 1599.96   255.5 1595.74   265.4 1593.56   275.2 1592.52
   353.8 1586.46   363.7 1585.06   383.3  1579.7   393.1 1577.89   412.8 1577.34
   481.6  1577.6   491.4 1578.26   501.3 1580.37   550.4 1596.81   560.2 1599.62
   570.1 1601.87  627.191612.812   670.31620.273   678.2 1621.39   717.5 1623.62
#Mann= 5 ,-1 , 0
       0     .12       0   383.3    .045       0   501.3     .12       0
  627.19     .06       0   670.3     .12       0
Bank Sta=383.3,501.3
XS Rating Curve= 0 ,0
Exp/Cntr=0.3,0.1

Type RM Length L Ch R = 1 ,6202.8  ,308.1,311,314.1
XS GIS Cut Line= 2
     1811816.005      200946.031      1812343.82      200426.041
#Sta/Elev= 30
       0 1756.14    29.2 1738.57      78 1709.86   107.2  1692.1     156 1663.69
   165.7 1657.74   175.5 1651.67     195 1638.88   224.2 1617.89     234 1611.73
   243.7 1606.48   263.2 1596.71   292.5 1582.58   302.2 1578.33     312  1575.6
   321.7 1574.58     390 1574.38   409.5 1574.55   419.2 1575.46  423.131576.603
     429 1578.31     468  1595.2   477.7 1598.63   487.4 1600.92     507 1602.76
   594.7 1609.48   623.9 1611.54  649.811612.736   672.7 1614.69   740.9 1622.47
#Mann= 4 ,-1 , 0
       0     .12       0     312    .045       0  423.13     .12       0
  649.81     .08       0
Bank Sta=312,423.13
XS Rating Curve= 0 ,0
Exp/Cntr=0.3,0.1

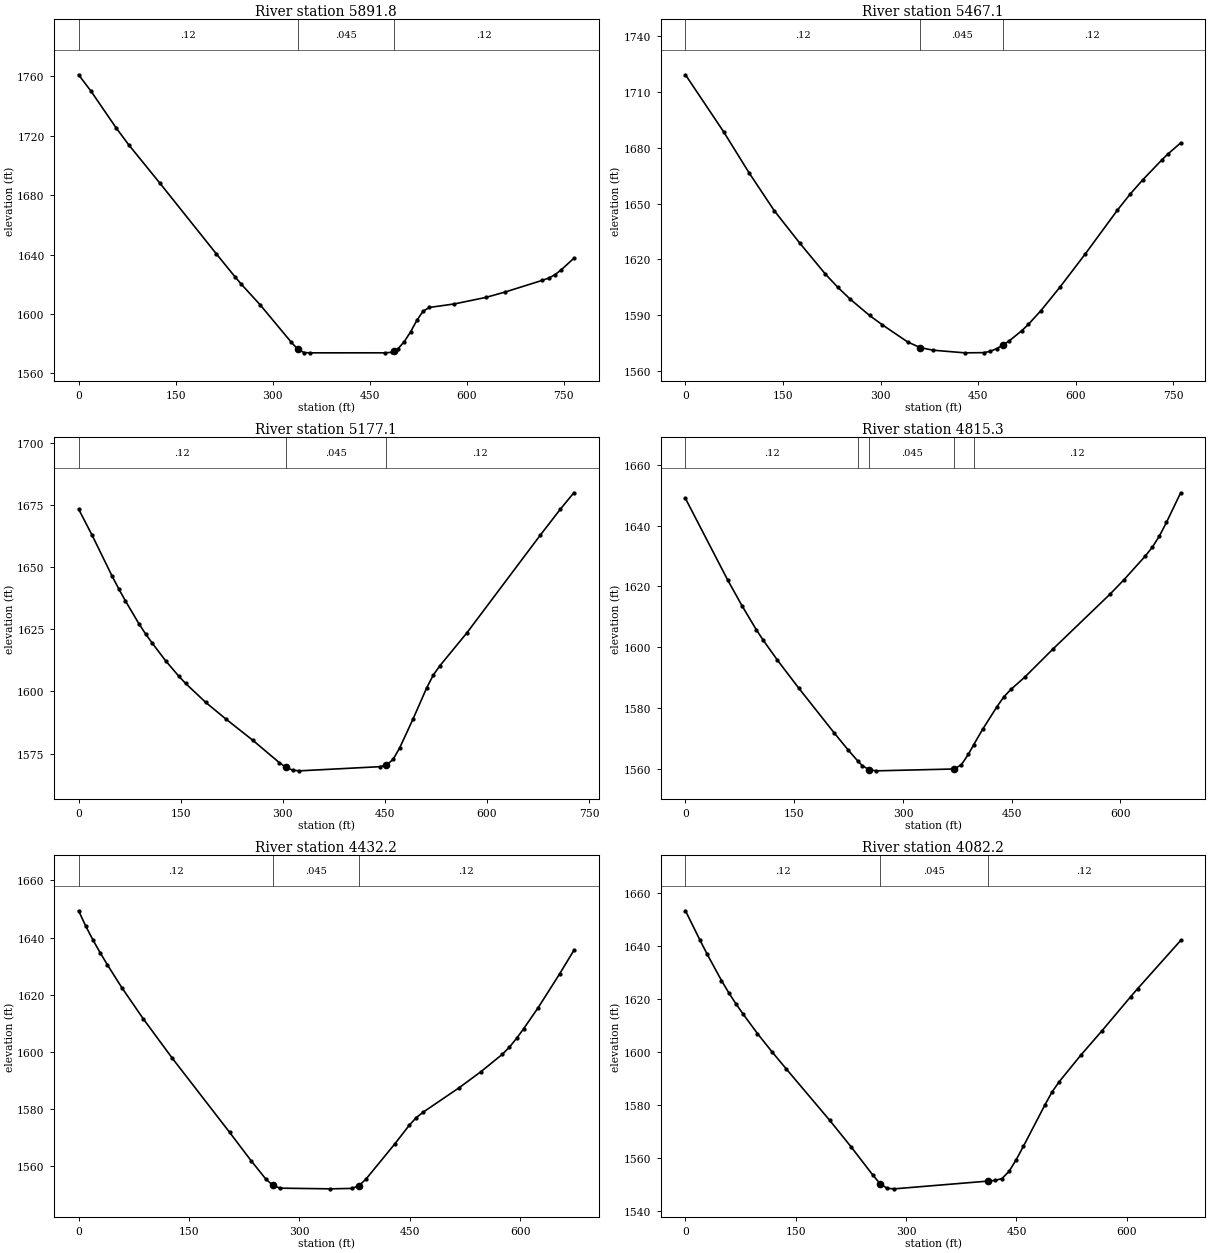
Type RM Length L Ch R = 1 ,5891.8  ,394.9,424.8,454.5
XS GIS Cut Line= 4
     1811931.137      201094.822       1812193.7      200996.009
     1812422.866      200801.564     1812599.733      200748.925
#Sta/Elev= 30
       0 1761.15    19.4 1749.95      58 1725.36    77.4 1713.99   125.8 1688.02
   212.8 1640.52   241.8 1624.97   251.5 1619.99   280.5 1606.18     329 1580.76
   338.7 1576.25   348.4 1573.91   358.1 1573.72   474.4 1573.73   484.1 1574.11
  488.07 1575.08   493.8 1576.48   503.5  1581.3   513.2 1587.81   522.9 1595.61
   532.6 1601.77   542.3 1604.32   581.1  1606.7   629.6 1611.08   658.8 1614.63
   717.1 1622.62   726.8 1624.12   736.5 1626.39   746.2 1629.69   765.6 1637.46
#Mann= 3 ,-1 , 0
       0     .12       0   338.7    .045       0  488.07     .12       0
Bank Sta=338.7,488.07
XS Rating Curve= 0 ,0
Exp/Cntr=0.3,0.1

Type RM Length L Ch R = 1 ,5467.1  ,283.2,290,296.7
XS GIS Cut Line= 2
     1812009.301      201247.794     1812767.736      201311.969
#Sta/Elev= 30
       0 1719.07    58.6 1688.54    97.6 1666.59   136.6 1646.13   175.6 1628.83
   214.7 1612.34   234.2 1605.06   253.7 1598.58     283 1589.96   302.5 1584.98
   341.5 1575.77  360.831572.736   380.6 1571.34   429.4 1569.92   458.6 1570.03
   468.4 1570.71   478.2 1572.13   487.9 1574.06   497.7 1576.33   517.2 1581.87
     527 1585.15   546.5 1592.59   575.7 1605.18   614.8 1623.08   663.6 1646.28
   683.1 1654.87   702.6  1662.6   731.9 1673.27   741.6 1676.58   761.2 1682.51
#Mann= 3 ,-1 , 0
       0     .12       0  360.83    .045       0   487.9     .12       0
Bank Sta=360.83,487.9
XS Rating Curve= 0 ,0
Exp/Cntr=0.3,0.1

Type RM Length L Ch R = 1 ,5177.1  ,354.3,361.8,369.2
XS GIS Cut Line= 2
     1812015.928      201466.763     1812718.522      201656.259
#Sta/Elev= 30
       0 1673.26    19.7 1662.86    49.2 1646.35      59 1641.25    68.8  1636.4
    88.5 1627.26    98.3 1623.18   108.2 1619.42   127.8 1612.36   147.5 1606.05
   157.3 1603.21   186.8 1595.62   216.3 1588.96   255.7 1580.45     295 1571.39
   304.8  1569.5   314.7 1568.36   324.5 1568.11   442.5 1569.78   452.4 1570.38
   462.2 1572.74     472 1577.44   491.7  1589.1   511.4 1601.39   521.2 1606.61
     531 1610.37   570.4  1623.5   678.5 1662.84     708 1673.28   727.7 1679.84
#Mann= 3 ,-1 , 0
       0     .12       0   304.8    .045       0   452.4     .12       0
Bank Sta=304.8,452.4
XS Rating Curve= 0 ,0
Exp/Cntr=0.3,0.1

Type RM Length L Ch R = 1 ,4815.3  ,381.9,383.1,384.4
XS GIS Cut Line= 2
     1811928.224      201730.182     1812541.978      202029.718
#Sta/Elev= 30
       0    1649    58.5 1622.02      78 1613.66    97.6  1605.8   107.3 1602.29
   126.8 1595.75   156.1 1586.57   204.9 1571.84   224.4 1566.15  237.591562.535
   243.9 1560.98   253.7  1559.6   263.4 1559.27   370.7 1559.88   380.5 1561.27
   390.2  1564.7  397.721567.946   409.8 1572.93   429.3 1580.26     439 1583.61
   448.8 1586.08   468.3 1590.21   507.3  1599.5   585.4 1617.43   604.9 1622.24
   634.2 1630.02   643.9 1632.93   653.7 1636.64   663.4  1641.1     683 1650.87
#Mann= 5 ,-1 , 0
       0     .12       0  237.59     .08       0   253.7    .045       0
   370.7     .12       0  397.72     .12       0
Bank Sta=253.7,370.7
XS Rating Curve= 0 ,0
Exp/Cntr=0.3,0.1

Type RM Length L Ch R = 1 ,4432.2  ,349.7,350,350
XS GIS Cut Line= 3
     1811747.812      202049.749     1812033.068      202200.194
     1812341.948      202365.013
#Sta/Elev= 30
       0 1649.38     9.8 1643.96    19.6  1639.1    29.3 1634.69    39.1 1630.47
    58.6 1622.51      88 1611.49     127 1597.85   205.2 1571.78   234.5 1561.81
   254.1 1555.53   263.9 1553.24   273.6 1552.28     342 1552.04   371.1 1552.19
   380.8 1553.12   390.6 1555.54   429.5 1567.79   448.9 1574.23   458.6 1576.97
   468.4 1578.95     517 1587.46   546.2 1593.01   575.4 1599.11   585.1 1601.64
   594.8 1604.69   604.5 1608.11     624 1615.39   653.2 1627.24   672.6  1635.5
#Mann= 3 ,-1 , 0
       0     .12       0   263.9    .045       0   380.8     .12       0
Bank Sta=263.9,380.8
XS Rating Curve= 0 ,0
Exp/Cntr=0.3,0.1

Type RM Length L Ch R = 1 ,4082.2  ,347.5,350,348.5
XS GIS Cut Line= 3
     1811568.195      202342.973     1811870.445      202504.687
      1812161.38      202661.226
#Sta/Elev= 30
       0 1653.41    19.6 1642.42    29.4  1637.1      49  1627.1    58.8 1622.52
    68.6 1618.33    78.4 1614.45    97.9  1607.1   117.5 1600.27   137.1 1593.74
   195.9 1574.44   225.3 1564.33   254.6 1553.77   264.4 1550.53   274.2 1548.72
     284 1548.53   410.8 1551.44   420.5  1551.7   430.2 1552.38     440 1555.14
   449.7 1559.55   459.4 1564.56   488.6 1580.14   498.3 1585.04     508  1588.9
   537.1 1598.83   566.3 1608.16   605.2 1620.99   614.9 1624.09   673.2 1642.21
#Mann= 3 ,-1 , 0
       0     .12       0   264.4    .045       0   410.8     .12       0
Bank Sta=264.4,410.8
XS Rating Curve= 0 ,0
Exp/Cntr=0.3,0.1