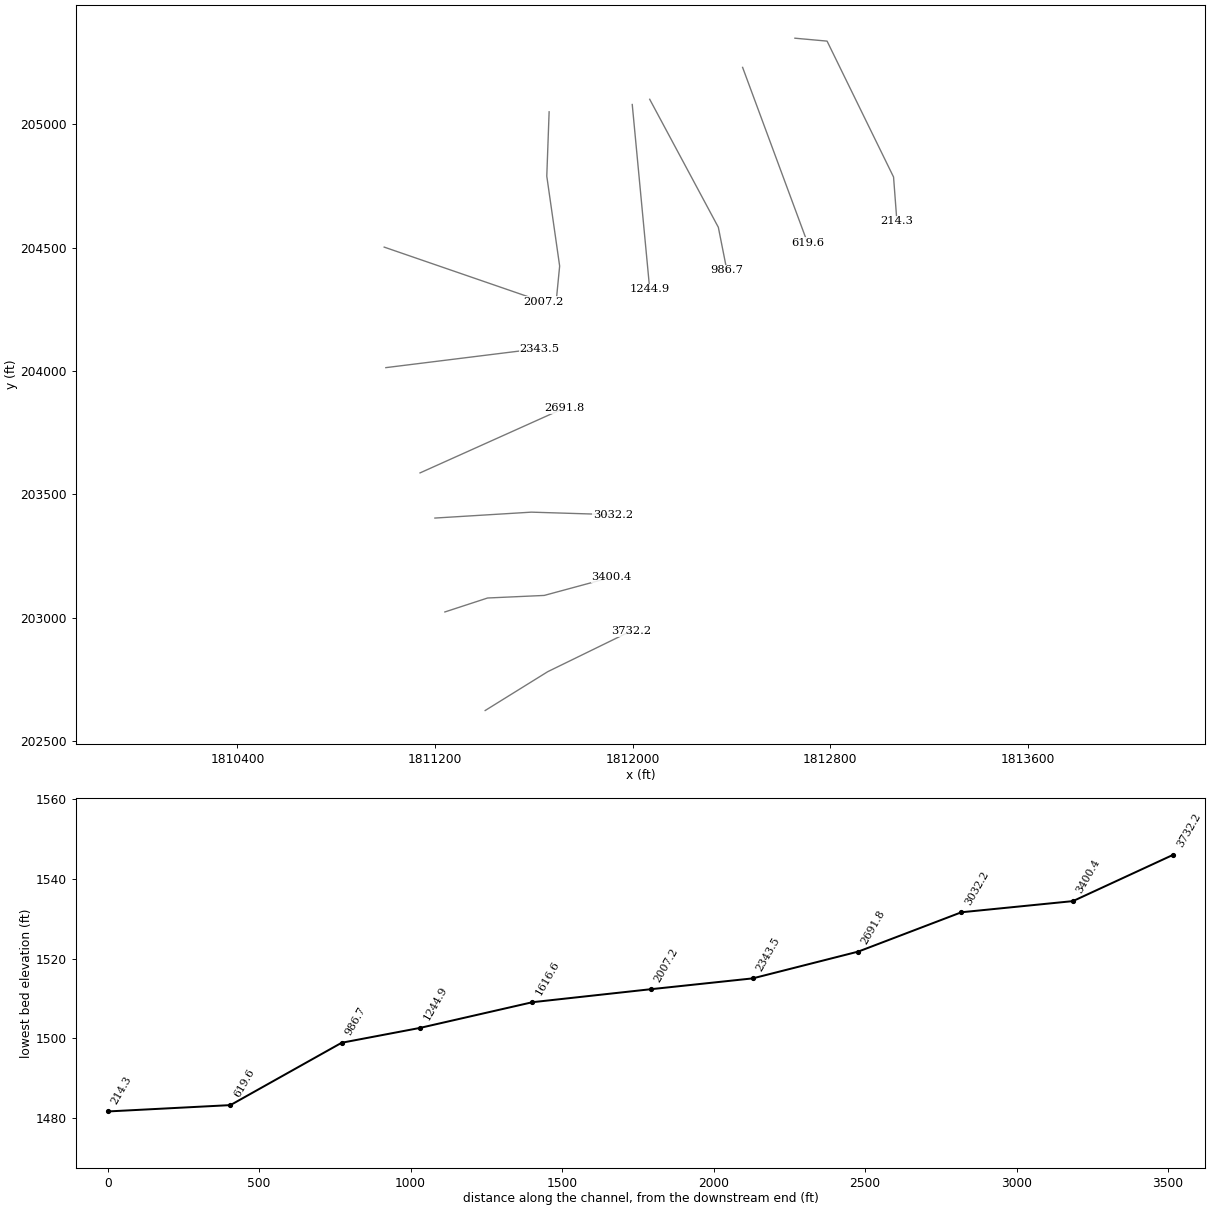
HEC-RAS study MIDFKRV2.prj: MIDFKRV2

--- MIDFKRV2.g01 (geometry) --- (continued)

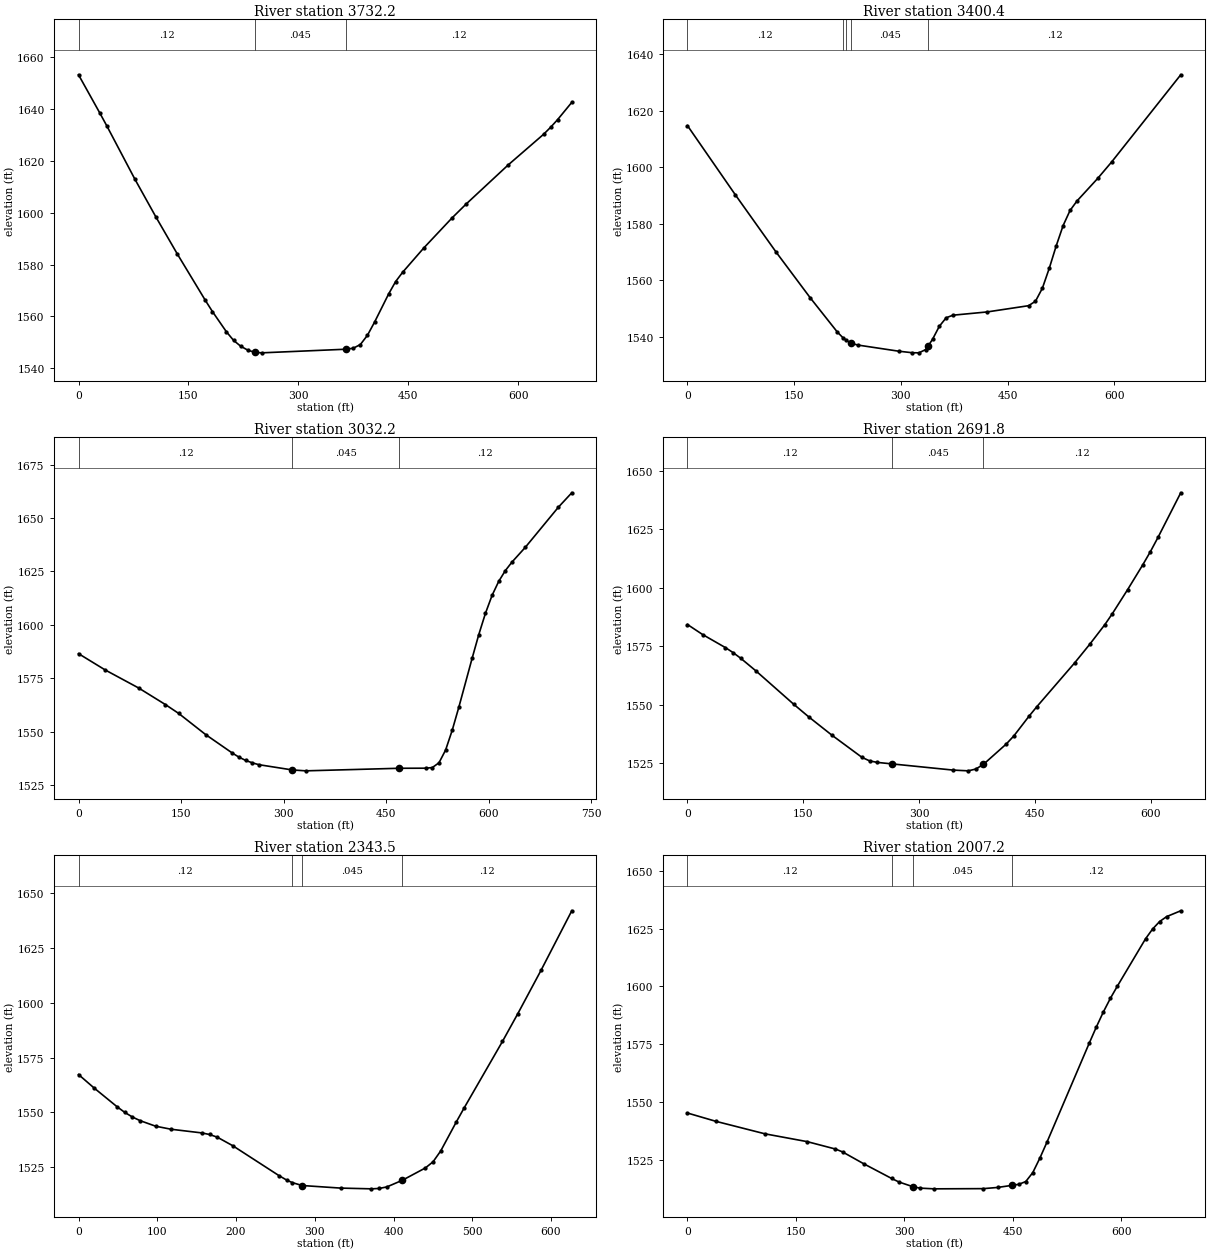
Type RM Length L Ch R = 1 ,3732.2  ,351.9,331.8,315.2
XS GIS Cut Line= 3
      1811402.63      202623.003     1811655.783      202780.423
      1811992.59      202945.215
#Sta/Elev= 30
       0 1653.06    28.8 1638.47    38.5 1633.44    76.9 1612.87   105.8 1598.21
   134.6 1584.16   173.1 1566.18   182.7  1561.9   201.9 1554.06   211.6 1550.79
   221.2 1548.56   230.8 1547.06   240.4 1546.18     250 1545.99   365.4 1547.39
     375 1547.78   384.6 1549.19   394.2 1552.72   403.9 1557.78   423.1 1568.62
   432.7 1573.43   442.3 1577.02   471.2 1586.39   509.6 1597.91   528.8 1603.25
   586.5 1618.39   634.6 1630.14   644.2 1632.84   653.8 1635.81   673.1 1642.44
#Mann= 3 ,-1 , 0
       0     .12       0   240.4    .045       0   365.4     .12       0
Bank Sta=240.4,365.4
XS Rating Curve= 0 ,0
Exp/Cntr=0.3,0.1

Type RM Length L Ch R = 1 ,3400.4  ,366.4,368.2,366
XS GIS Cut Line= 4
     1811239.532      203022.729      1811412.45      203079.342
     1811641.616      203089.759     1811913.751      203163.462
#Sta/Elev= 30
       0  1614.7      67 1590.34   124.5 1570.01   172.4 1553.87   210.6 1541.73
  218.211539.788  222.971538.843   229.7 1537.78   239.3 1537.13   296.6 1534.96
   315.8 1534.41   325.3 1534.37   334.9 1535.54  338.511536.908   344.4 1539.14
     354 1543.77   363.6 1546.77   373.1 1547.68   421.1 1548.83   479.4 1551.04
   489.1 1552.61   498.8 1557.21   508.6 1564.35   518.3 1572.23     528 1579.39
   537.7 1584.71   547.5 1588.08   576.6 1596.05   596.1 1601.84   693.3 1632.69
#Mann= 5 ,-1 , 0
       0     .12       0  218.21     .06       0  222.97     .08       0
   229.7    .045       0  338.51     .12       0
Bank Sta=229.7,338.51
XS Rating Curve= 0 ,0
Exp/Cntr=0.3,0.1

Type RM Length L Ch R = 1 ,3032.2  ,326.7,340.4,357.2
XS GIS Cut Line= 3
     1811199.198      203403.586     1811589.783      203427.539
     1811919.989       203417.32
#Sta/Elev= 30
       0 1586.47    39.1 1578.82      88 1570.38   127.2 1562.61   146.7 1558.44
   185.9 1548.59     225 1539.92   234.8 1537.98   244.6 1536.46   254.4 1535.31
   264.1 1534.45     313 1531.99   332.6 1531.58     469 1532.78   507.9 1532.82
   517.6 1533.11   527.4 1535.35   537.1 1541.33   546.8 1550.63   556.5 1561.46
   575.9 1584.31   585.6 1595.38   595.4 1605.39   605.1 1613.78   614.8 1620.33
   624.5 1625.38   634.2 1629.36   653.7 1636.27   702.2 1655.11   721.7 1661.82
#Mann= 3 ,-1 , 0
       0     .12       0     313    .045       0     469     .12       0
Bank Sta=313,469
XS Rating Curve= 0 ,0
Exp/Cntr=0.3,0.1

Type RM Length L Ch R = 1 ,2691.8  ,359.6,348.3,337.1
XS GIS Cut Line= 2
     1811139.057      203586.728     1811721.534      203848.968
#Sta/Elev= 30
       0 1584.26    19.6 1579.98    49.1  1574.4      59 1572.27    68.8 1569.88
    88.4 1564.51   137.6 1550.18   157.2 1544.75   186.7 1537.06     226 1527.49
   235.9 1525.99   245.7 1525.35   265.3 1524.69     344 1522.06   363.6 1521.74
   373.4 1522.51   383.3 1524.52   412.8 1533.19   422.6 1536.64   442.2 1545.04
   452.1 1549.03   501.2 1567.79   520.9  1575.8   540.5 1584.21   550.3 1588.94
     570 1599.17   589.6 1609.76   599.5 1615.41   609.3 1621.46   638.8 1640.55
#Mann= 3 ,-1 , 0
       0     .12       0   265.3    .045       0   383.3     .12       0
Bank Sta=265.3,383.3
XS Rating Curve= 0 ,0
Exp/Cntr=0.3,0.1

Type RM Length L Ch R = 1 ,2343.5  ,352.8,336.3,319.3
XS GIS Cut Line= 2
     1811000.599      204013.675     1811622.255      204091.048
#Sta/Elev= 30
       0 1567.23    19.6 1561.14    48.9 1552.54    58.7 1549.95    68.5 1547.82
    78.3 1546.16    97.9 1543.64   117.5 1542.25   156.6 1540.57   166.4 1539.85
   176.2 1538.63   195.8 1534.74   254.5 1521.09   264.3 1519.05  271.251517.915
   283.9 1516.56   332.8 1515.38     372 1515.04   381.7 1515.21   391.5 1515.91
   411.1 1518.93   440.5 1524.58   450.3 1527.42     460 1532.37   479.6 1545.48
   489.4 1551.79   538.4 1582.36   557.9 1595.04   587.3 1614.78   626.4 1641.99
#Mann= 4 ,-1 , 0
       0     .12       0  271.25     .08       0   283.9    .045       0
   411.1     .12       0
Bank Sta=283.9,411.1
XS Rating Curve= 0 ,0
Exp/Cntr=0.3,0.1

Type RM Length L Ch R = 1 ,2007.2  ,432.7,390.7,348.7
XS GIS Cut Line= 2
     1810993.909      204502.509     1811639.012      204279.863
#Sta/Elev= 30
       0 1545.17      39  1541.6   107.2 1536.16   165.7 1532.77   204.7 1529.57
   214.5 1528.33   243.7 1523.21   282.51516.814   292.5  1515.3     312 1513.24
   321.7 1512.64   341.2 1512.33   409.5 1512.42     429 1512.93   448.5 1513.82
   458.2 1514.27     468 1515.49   477.7 1519.37   487.5 1525.64   497.2 1532.47
   555.7 1575.36   565.4 1582.28   575.2 1588.87     585 1594.83   594.7 1600.13
   633.7 1620.65   643.4 1624.86   653.2 1628.13     663 1630.27   682.4 1632.78
#Mann= 4 ,-1 , 0
       0     .12       0   282.5     .08       0     312    .045       0
   448.5     .12       0
Bank Sta=312,448.5
XS Rating Curve= 0 ,0
Exp/Cntr=0.3,0.1

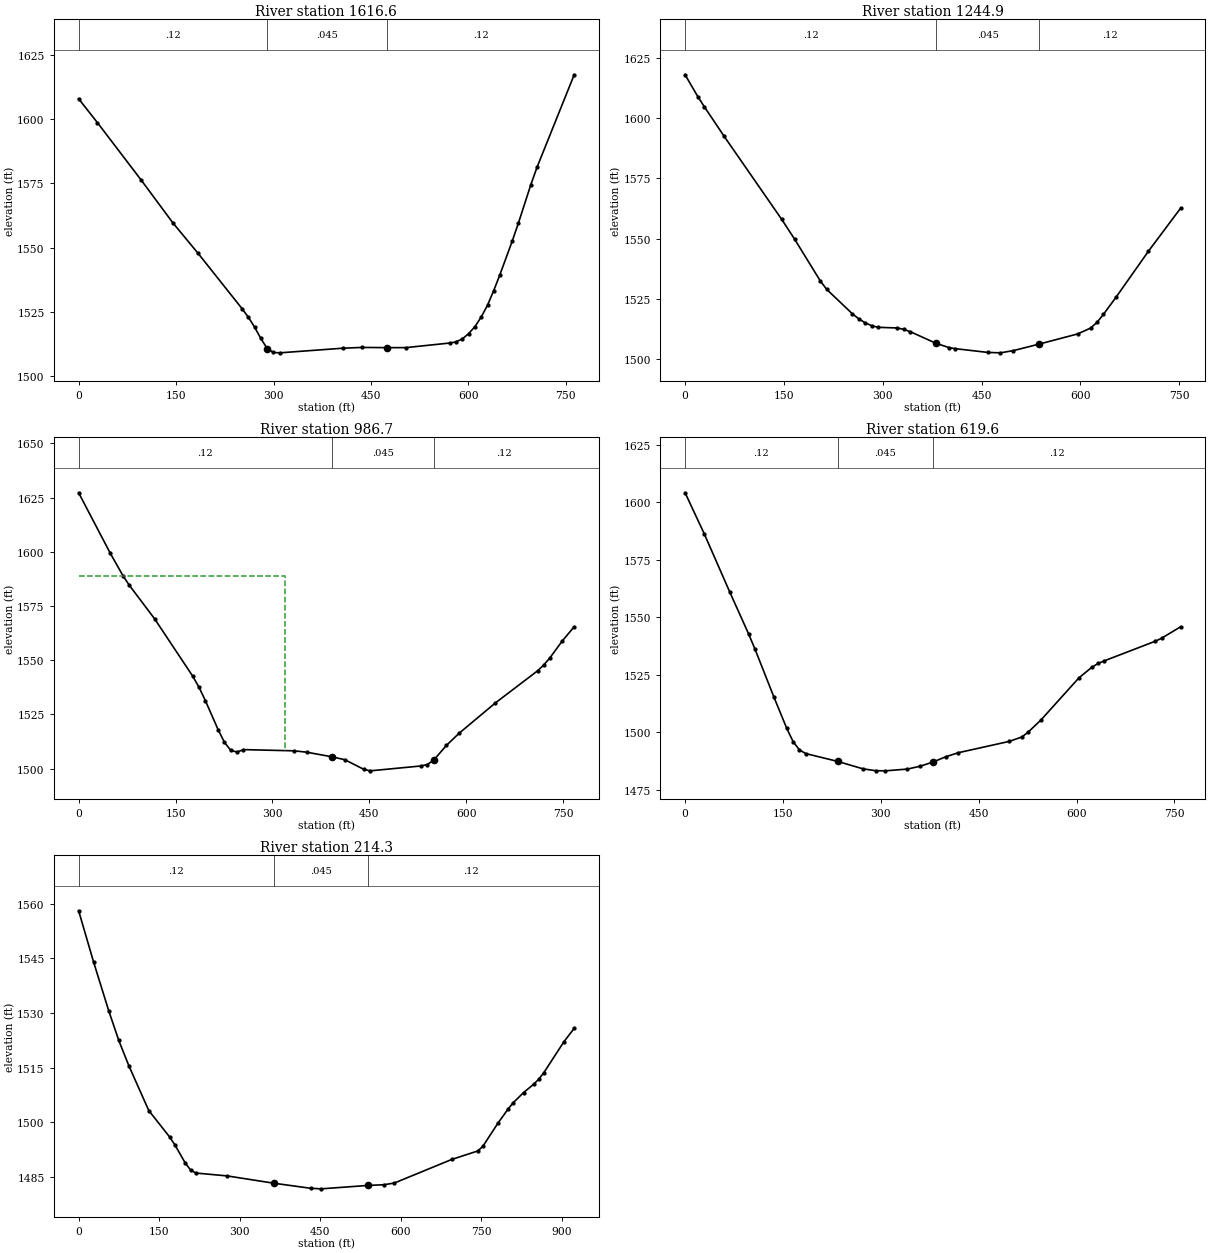
Type RM Length L Ch R = 1 ,1616.6  ,373.2,371.7,370
XS GIS Cut Line= 4
     1811661.521      205051.196     1811652.033       204790.28
     1811704.116      204425.696     1811691.095      204292.884
#Sta/Elev= 30
       0 1607.83      29 1598.52    96.7 1576.09     145 1559.62   183.7 1547.81
   251.4  1526.3   261.1 1522.98   270.8  1519.1   280.5 1514.66   290.2 1510.76
   299.9 1509.23   309.6 1509.08   406.5 1510.88   435.5 1511.18   474.3  1511.1
   503.4  1511.1   571.2 1512.89   580.9 1513.34   590.6 1514.48   600.3 1516.54
     610 1519.26   619.7    1523   629.4  1527.6   638.9 1533.22   648.4  1539.4
   667.5 1552.54     677 1559.54   696.1 1574.44   705.6  1581.2   762.8 1617.15
#Mann= 3 ,-1 , 0
       0     .12       0   290.2    .045       0   474.3     .12       0
Bank Sta=290.2,474.3
XS Rating Curve= 0 ,0
Exp/Cntr=0.3,0.1

Type RM Length L Ch R = 1 ,1244.9  ,243.4,258.2,273.1
XS GIS Cut Line= 2
     1811997.951       205080.91       1812068.7      204331.946
#Sta/Elev= 30
       0 1617.87    19.5 1608.75    29.3 1604.59    58.6 1592.64   146.6 1557.98
   166.1 1549.82   205.2 1532.47   214.9 1528.97     254  1518.8   263.8 1516.71
   273.6 1515.05   283.3 1513.88   293.1 1513.22   322.4 1512.94   332.2 1512.34
     342 1511.38     381 1506.59   400.6 1504.82   410.3 1504.37   459.2 1502.82
   478.7 1502.64   498.3 1503.56   537.4 1506.26     596 1510.48   615.5 1512.89
   625.3 1515.26   635.1 1518.58   654.6 1525.83   703.4 1544.75   752.3  1562.6
#Mann= 3 ,-1 , 0
       0     .12       0     381    .045       0   537.4     .12       0
Bank Sta=381,537.4
XS Rating Curve= 0 ,0
Exp/Cntr=0.3,0.1

Type RM Length L Ch R = 1 ,986.7   ,372.3,367.1,360.9
XS GIS Cut Line= 3
     1812068.654      205102.048     1812346.477      204582.814
     1812381.124      204407.849
#Sta/Elev= 30
       0 1627.18    49.1 1599.23    68.7 1588.89    78.5 1584.51   117.8 1568.97
   176.7 1542.56   186.5 1537.42   196.3 1531.25   215.9 1517.97   225.7  1512.1
   235.6 1508.34   245.4 1507.61   255.2 1508.72   333.7 1508.16   353.3 1507.52
   392.6 1505.38   412.2 1504.05   441.7 1499.59   451.5 1498.93     530 1501.18
   539.8 1501.84   549.6 1503.82   569.3 1510.63   588.9 1516.22   645.2 1530.25
   710.9 1545.14   720.3 1547.82   729.7 1551.06   748.5 1558.74   767.2 1565.39
#Mann= 3 ,-1 , 0
       0     .12       0   392.6    .045       0   549.6     .12       0
#XS Ineff= 2 , 0
          319.28  1588.6
Permanent Ineff=
       F       F
Bank Sta=392.6,549.6
XS Rating Curve= 0 ,0
Exp/Cntr=0.3,0.1

Type RM Length L Ch R = 1 ,619.6   ,401.3,405.3,409.7
XS GIS Cut Line= 2
     1812444.668      205231.466     1812707.884      204519.027
#Sta/Elev= 30
       0 1604.09    29.2 1586.37    68.2 1561.15    97.4 1542.75   107.1  1536.2
   136.3 1515.24   155.8 1501.77   165.5 1496.05   175.3 1492.41     185 1490.82
   233.7 1487.44   272.6  1484.2   292.1 1483.39   306.9 1483.33   340.8  1484.1
   360.3 1485.34   379.8 1487.14   399.2 1489.41   418.7  1491.2   496.6  1496.1
   516.1 1498.03   525.8 1500.14   545.3 1505.38   603.7 1523.74   623.2 1528.26
   632.9 1529.95   642.7 1531.13   720.6 1539.61   730.3 1540.92   759.5  1545.9
#Mann= 3 ,-1 , 0
       0     .12       0   233.7    .045       0   379.8     .12       0
Bank Sta=233.7,379.8
XS Rating Curve= 0 ,0
Exp/Cntr=0.3,0.1

Type RM Length L Ch R = 1 ,214.3   ,223.2,214.3,205.4
XS GIS Cut Line= 4
      1812656.42      205349.855     1812786.582      205338.023
     1813055.679      204786.807     1813069.182      204607.895
#Sta/Elev= 30
       0 1558.06      28 1543.94      56 1530.65    74.7 1522.53    93.4 1515.59
   130.7 1503.24   169.6 1495.97   179.4 1493.81   198.8  1488.8   208.6 1486.93
   218.3 1486.08   276.7 1485.29   364.4 1483.27   432.5 1481.89     452 1481.74
   539.6 1482.68   568.8 1482.86   588.3 1483.33   695.4 1489.81   744.1 1492.15
   753.5 1493.46   781.9 1499.86   800.8 1503.74   810.2 1505.41   829.1 1508.15
     848 1510.45   857.4 1511.82   866.8 1513.58   904.6 1522.16   923.5 1525.78
#Mann= 3 , 0 , 0
       0     .12       0   364.4    .045       0   539.6     .12       0
Bank Sta=364.4,539.6
XS Rating Curve= 0 ,0
Exp/Cntr=0.3,0.1

Chan Stop Cuts=-1
Use User Specified Reach Order=0
Composite Channel Slope=5